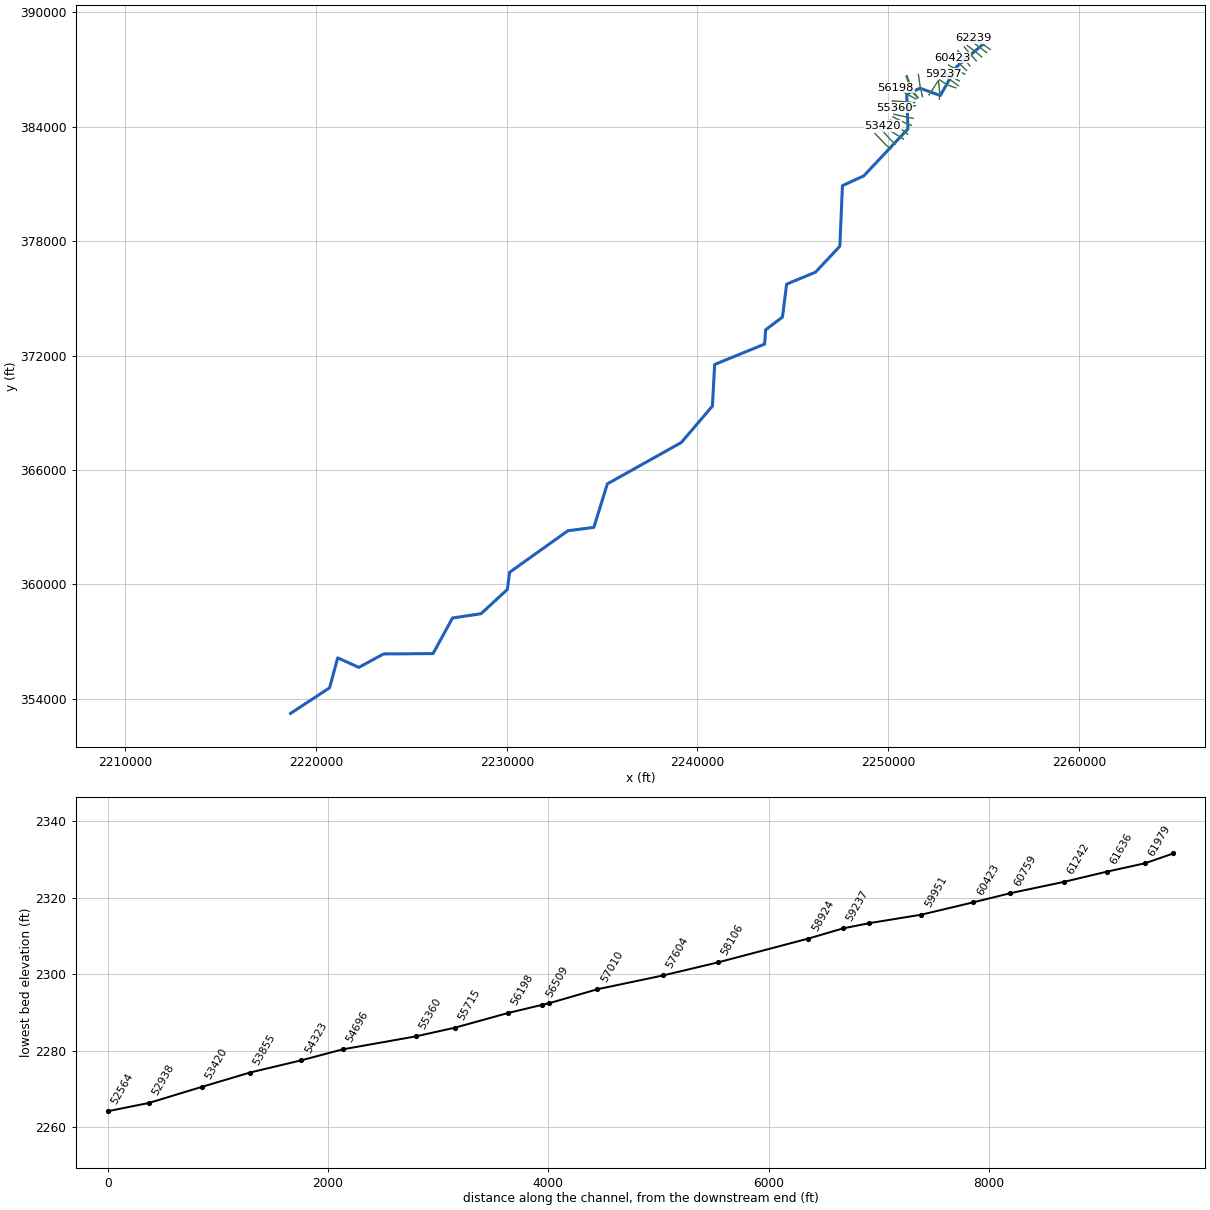
--- MFANTNYCK.prj (project) ---

Proj Title=MFANTNYCK
Current Plan=p01
Default Exp/Contr=0.3,0.1
English Units
Geom File=g01
Flow File=f01
Plan File=p01
Y Axis Title=Elevation
X Axis Title(PF)=Main Channel Distance
X Axis Title(XS)=Station
BEGIN DESCRIPTION:
Stream Name- Middle Fork Anthonys Creek
Flood Zone: Zone A
Greenbrier County, WV
County-Wide Study
WVDHSEM-2018-3, Flood Risk Project
HEC-RAS Version: 5.0.7
General Notes:
For the Hydrology Regression was used.
END DESCRIPTION:
DSS Export Rating Curves= 0
DSS Export Rating Curve Sorted= 0
DSS Export Volume Flow Curves= 0
DXF Filename=A2c.
DXF OffsetX= 0
DXF OffsetY= 0
DXF ScaleX= 1
DXF ScaleY= 10

--- MFANTNYCK.p01 (plan) ---

Plan Title=Floodplain
Program Version=5.07
Short Identifier=Floodplain
Geom File=g01
Flow File=f01
Subcritical Flow
K Sum by GR= 0
Std Step Tol= 0.01
Critical Tol= 0.01
Num of Std Step Trials= 20
Max Error Tol= 0.3
Flow Tol Ratio= 0.001
Split Flow NTrial= 30
Split Flow Tol= 0.02
Split Flow Ratio= 0.02
Log Output Level= 0
Friction Slope Method= 1
Unsteady Friction Slope Method= 2
Unsteady Bridges Friction Slope Method= 1
Parabolic Critical Depth
Global Vel Dist= 0 , 0 , 0
Global Log Level= 0
CheckData=True
Encroach Param=-1 ,0,0, 0
Computation Interval=1MIN
Output Interval=1HOUR
Instantaneous Interval=1HOUR
Mapping Interval=1HOUR
Computation Time Step Use Courant=        0
Computation Time Step Use Time Series=    0
Computation Time Step Count To Double=0
Computation Time Step Max Doubling=0
Computation Time Step Max Halving=0
Computation Time Step Residence Courant=0
Run HTab= 0
Run UNet= 0
Run Sediment= 0
Run PostProcess= 0
Run WQNet= 0
Run RASMapper= 0
UNET Theta= 1
UNET Theta Warmup= 1
UNET ZTol= 0.02
UNET ZSATol= 0.02
UNET MxIter= 20
UNET Max Iter WO Improvement= 0
UNET MaxInSteps= 0
UNET DtIC= 0
UNET DtMin= 0
UNET MaxCRTS= 20
UNET WFStab= 2
UNET SFStab= 1
UNET WFX= 1
UNET SFX= 1
UNET 1D Methodology=Finite Difference
UNET DSS MLevel= 4
UNET Pardiso=0
UNET DZMax Abort= 100
UNET Use Existing IB Tables=-1
UNET Froude Reduction=False
UNET Froude Limit= 0.8
UNET Froude Power= 4
UNET D1 Cores= 0
UNET D2 Coriolis=0
UNET D2 Cores= 0
UNET D2 Theta= 1
UNET D2 Theta Warmup= 1
UNET D2 Z Tol= 0.01
UNET D2 Volume Tol= 0.01
UNET D2 Max Iterations= 20
UNET D2 Equation= 0
UNET D2 RampUpFraction=0.1
UNET D2 TimeSlices= 1
UNET D2 BCVolumeCheck=0
UNET D1D2 MaxIter= 0
UNET D1D2 ZTol=0.01
UNET D1D2 QTol=0.1
UNET D1D2 MinQTol=1
Write IC File= 0
Write IC File at Fixed DateTime=0
Write IC File at Sim End=0
Echo Input=False
Echo Parameters=False
Echo Output=False
Write Detailed= 0
HDF Write Warmup=0
HDF Write Time Slices=0
HDF Flush=0
HDF Face Node Velocities=0
HDF Compression= 1
HDF Chunk Size= 1
HDF Spatial Parts= 1
HDF Use Max Rows=0
HDF Fixed Rows= 1
Calibration Method= 0
Calibration Iterations= 20
Calibration Max Change=0.05
Calibration Tolerance=0.2
Calibration Maximum=1.5
Calibration Minimum=0.5
Calibration Optimization Method= 1
WQ AD Non Conservative
WQ ULTIMATE=-1
WQ Max Comp Step=1HOUR
WQ Output Interval=15MIN
WQ Output Selected Increments= 0
WQ Output face flow=0
WQ Output face velocity=0
WQ Output face area=0
WQ Output face dispersion=0
WQ Output cell volume=0
WQ Output cell surface area=0
WQ Output cell continuity=0
WQ Output cumulative cell continuity=0
WQ Output face conc=0
WQ Output face dconc_dx=0
WQ Output face courant=0
WQ Output face peclet=0
WQ Output face adv mass=0
WQ Output face disp mass=0
WQ Output cell mass=0
WQ Output cell source sink temp=0
WQ Output nsm pathways=0
WQ Output nsm derived pathways=0
WQ Output MaxMinRange=-1
WQ Daily Max Min Mean=-1
WQ Daily Range=0
WQ Daily Time=0
WQ Create Restart=0
WQ Fixed Restart=0
WQ System Summary=0
WQ Write To DSS=0
WQ Use Fixed Temperature=0
Sorting and Armoring Iterations= 10
XS Update Threshold= 0.02
Bed Roughness Predictor= 0
Hydraulics Update Threshold= 0.02
Energy Slope Method= 1
Volume Change Method= 1
Sediment Retention Method= 0
XS Weighting Method= 0
Number of US Weighted Cross Sections= 1
Number of DS Weighted Cross Sections= 1
Upstream XS Weight=0
Main XS Weight=1
Downstream XS Weight=0
Number of DS XS's Weighted with US Boundary= 1
Upstream Boundary Weight= 1
Weight of XSs Associated with US Boundary= 0
Number of US XS's Weighted with DS Boundary= 1
Downstream Boundary Weight= 0.5
Weight of XSs Associated with DS Boundary= 0.5
Percentile Method= 0
Sediment Output Level= 3
Mass or Volume Output= 0
Output Increment Type= 1
Profile and TS Output Increment= 1
XS Output Flag= 0
XS Output Increment= 10
Write Gradation File= 0
Read Gradation Hotstart= 0
Write HDF5 File= 1
Write Binary Output= 1
Write DSS Sediment File= 0
SV Curve= 0
Specific Gage Flag= 0

--- MFANTNYCK.f01 (steady flow) ---

Flow Title=Flow
Program Version=5.07
Number of Profiles= 6
Profile Names=f1p,f10p,f4p,f2p,f02p,f1pplus
River Rch & RM=MFANTNYCK,Main            ,62239
    1410     772    1010    1200    1940    2090
River Rch & RM=MFANTNYCK,Main            ,58106
    1580     868    1130    1350    2160    2330
River Rch & RM=MFANTNYCK,Main            ,55360
    1820    1010    1310    1560    2490    2690
River Rch & RM=MFANTNYCK,Main            ,52938
    2030    1120    1460    1730    2760    3000
River Rch & RM=MFANTNYCK,Main            ,48015
    2310    1290    1670    1980    3150    3420
River Rch & RM=MFANTNYCK,Main            ,44550
    2730    1530    1980    2340    3700    4030
River Rch & RM=MFANTNYCK,Main            ,38407
    3100    1750    2250    2660    4200    4590
River Rch & RM=MFANTNYCK,Main            ,29623
    3460    1960    2520    2980    4680    5120
River Rch & RM=MFANTNYCK,Main            ,25319
    3880    2210    2840    3340    5230    5740
River Rch & RM=MFANTNYCK,Main            ,16951
    4320    2470    3160    3720    5810    6390
River Rch & RM=MFANTNYCK,Main            ,12276
    4850    2780    3560    4180    6510    7170
Boundary for River Rch & Prof#=MFANTNYCK,Main            , 1
Up Type= 0
Dn Type= 1
Dn Known WS=2029.87
Boundary for River Rch & Prof#=MFANTNYCK,Main            , 2
Up Type= 0
Dn Type= 1
Dn Known WS=2028.24
Boundary for River Rch & Prof#=MFANTNYCK,Main            , 3
Up Type= 0
Dn Type= 1
Dn Known WS=2028.9
Boundary for River Rch & Prof#=MFANTNYCK,Main            , 4
Up Type= 0
Dn Type= 1
Dn Known WS=2029.39
Boundary for River Rch & Prof#=MFANTNYCK,Main            , 5
Up Type= 0
Dn Type= 1
Dn Known WS=2031.02
Boundary for River Rch & Prof#=MFANTNYCK,Main            , 6
Up Type= 0
Dn Type= 1
Dn Known WS=2030.37
DSS Import GetInterval= 0
DSS Import GetPeak= 0
DSS Import FillOption= 0

--- MFANTNYCK.g01 (geometry) ---

Geom Title=Geometry
Program Version=5.07

River Reach=MFANTNYCK       ,Main
Reach XY= 30
2254971.66141387388322.0670191042253596.14068414387152.908827558
2252736.81366263385636.5453904722251681.25803097386015.989841565
2250975.70235547385735.4343003032251037.36922689383886.545281559
2248723.03691331381422.6850518142247603.46172464380908.932470396
2247467.36914906377733.2121158092246194.03573772376373.767656222
2244677.36915164375744.8788221482244455.70260023374013.767454982
2243574.03572838 373348.767472642243522.92461014372600.434323639
2240901.81371063371530.9899402262240783.48028588369350.434261978
2239152.36904681367438.2120365652235274.03592423365269.878774807
2234566.36214273362987.7143758982233202.64702238362810.631068647
2230147.09145372360630.0753903992230030.77180447 359732.50599131
2228648.82738988358459.0685775582227153.16765155358235.110035971
2226132.33439139356368.7906058882223534.24411514356347.957314223
2222240.84151822355643.9642996492221132.33454889356143.096175388
2220706.11919397354573.6518077252218662.35814022353232.962341355

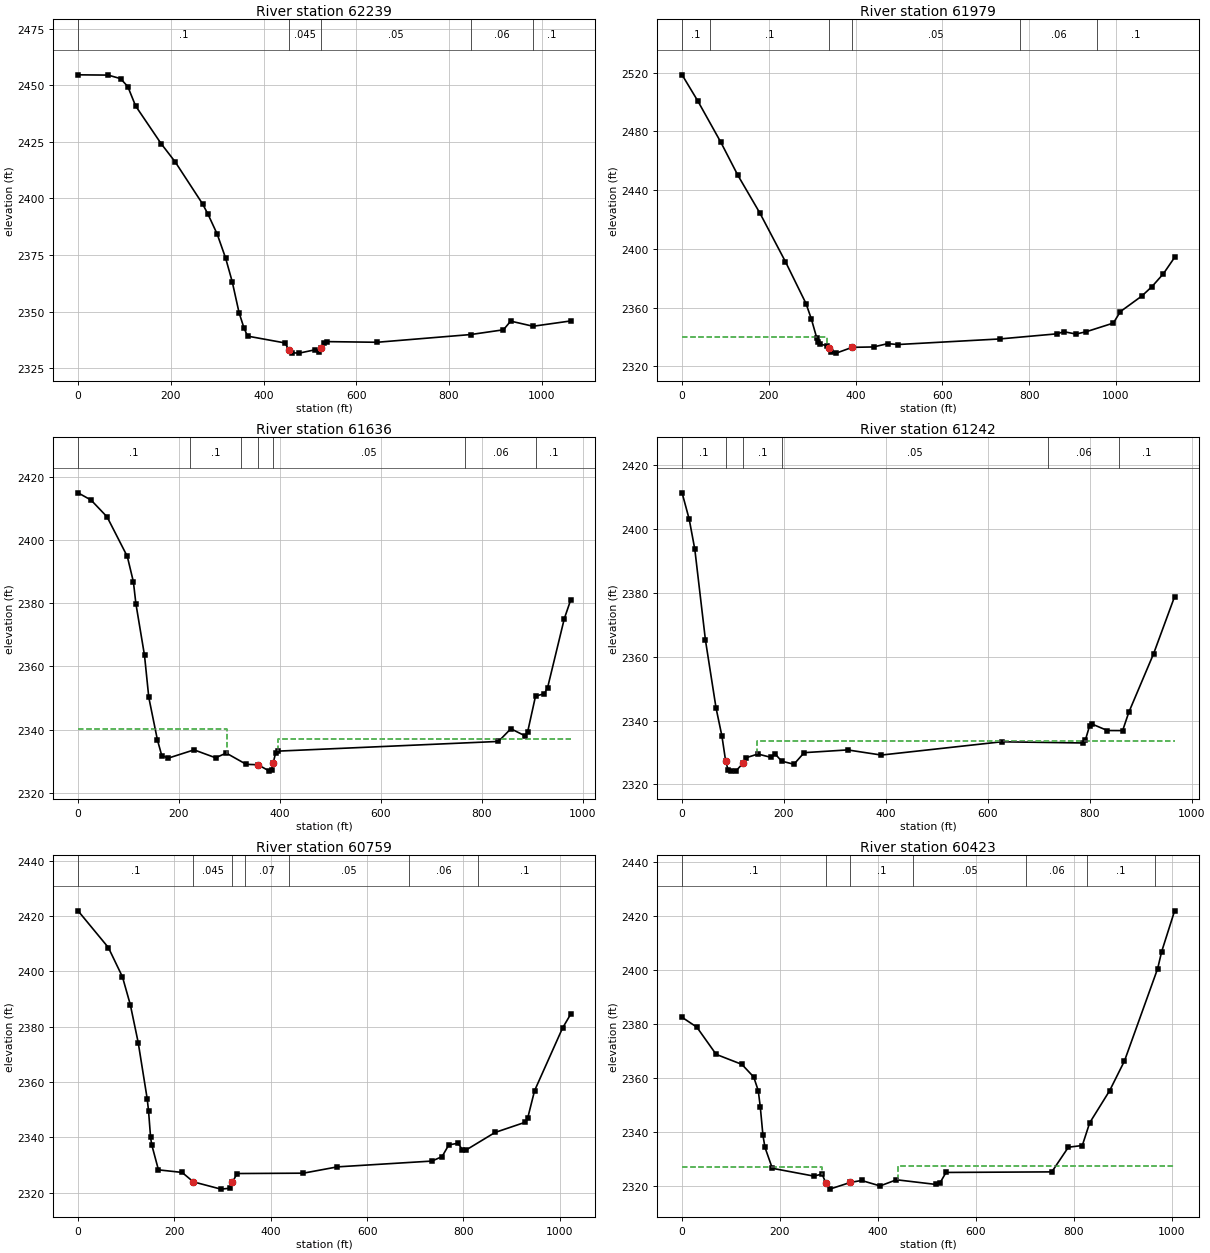
Type RM Length L Ch R = 1 ,62239   ,255.2,259.1,247.6
XS GIS Cut Line= 2
2255366.85704759388050.1571154142254480.43117563388635.595098015
#Sta/Elev= 30
       0 2454.66    64.9 2454.54    91.7 2452.98   107.4 2449.43   124.1 2440.92
   179.1 2424.26   209.6 2416.15   268.6 2397.59   280.4 2392.99   300.1 2384.25
   318.3 2373.62   332.5 2363.22   347.2 2349.59   357.7 2342.84   365.6 2339.15
   446.1 2336.14   455.6 2332.81   461.3 2331.78   476.9 2331.63   510.1 2333.06
   519.5 2332.24   524.3 2333.69   530.4  2336.2     536 2336.72     645 2336.43
   846.6 2339.84   917.4 2341.94   933.1 2345.78   981.3 2343.51  1062.3 2345.85
#Mann= 5 ,-1 , 0
       0      .1       0   455.6    .045       0   524.3     .05       0
   846.6     .06       0   981.3      .1       0
Bank Sta=455.6,524.3
XS Rating Curve= 0 ,0
Exp/Cntr(USF)=0,0
Exp/Cntr=0.3,0.1

Type RM Length L Ch R = 1 ,61979   ,343.6,343.9,335.3
XS GIS Cut Line= 2
2255171.49383263 387885.060578482254261.77189881388563.880086973
#Sta/Elev= 30
       0 2518.56    35.9 2500.94    89.5 2472.55   128.4 2450.24   179.2 2424.49
   238.2 2391.33   285.6 2362.83   297.9 2352.34   310.2 2339.58   314.3  2336.4
   318.3 2335.09   334.7 2334.11     338 2332.71   342.9 2329.58   355.2 2329.04
     392 2332.98   441.2 2333.25     474  2335.5   497.4  2334.9   731.9 2338.69
   863.6 2342.17     880 2343.62   907.8 2342.04   931.1 2343.59   993.8 2349.49
  1010.2 2357.34  1059.3 2367.88    1083 2374.37  1109.3 2383.13  1135.1 2394.24
#Mann= 6 ,-1 , 0
       0      .1       0   63.84      .1       0     338    .045       0
     392     .05       0   779.8     .06       0  955.41      .1       0
#XS Ineff= 2 , 0
          334.19 2340.03
Permanent Ineff=
       F       F
Bank Sta=338,392
XS Rating Curve= 0 ,0
Exp/Cntr=0.3,0.1

Type RM Length L Ch R = 1 ,61636   ,394.1,393.1,385
XS GIS Cut Line= 3
2254909.34114172 387659.366147982254527.39669564387977.074502066
2254141.98014364 388261.79670164
#Sta/Elev= 30
       0 2414.96    25.8 2412.67    57.5 2407.35    97.6 2394.83   109.7 2386.76
   114.6  2379.9   131.7 2363.49   140.2 2350.18   157.3 2336.72   165.9 2331.79
   178.7 2330.97   229.9 2333.59   272.5 2331.09   293.7 2332.57   333.3 2329.01
   356.6 2328.88   379.2 2326.86   383.5 2327.16   386.9 2329.58   391.5 2332.64
   396.1 2333.19   833.1 2336.26   857.6 2340.28   885.8 2338.02   890.9 2339.29
   906.5 2350.59     924 2351.38   930.4 2353.27   963.6 2375.16     976 2380.95
#Mann= 7 ,-1 , 0
       0      .1       0  221.14      .1       0  323.37     .05       0
   356.6    .045       0   386.9     .05       0  767.35     .06       0
  907.35      .1       0
#XS Ineff= 2 , 0
          295.42  2340.1  396.72         2336.96
Permanent Ineff=
       F       F
Bank Sta=356.6,386.9
XS Rating Curve= 0 ,0
Exp/Cntr=0.3,0.1

Type RM Length L Ch R = 1 ,61242   ,458.9,483.1,481.8
XS GIS Cut Line= 2
2254619.41061921387449.2966862322253990.93845098388183.671857893
#Sta/Elev= 30
       0 2411.43      14 2403.16      25 2393.73    45.9 2365.22    66.8 2343.86
    78.2 2335.18    85.5 2327.37    90.1 2324.68      96 2324.17   106.4 2324.33
   120.4  2326.8   126.2 2328.39   148.8 2329.53   173.7 2328.52   183.2 2329.46
   195.3 2327.31   219.5 2326.32   239.6 2329.96   324.9 2330.82     391 2329.21
   627.1 2333.37   786.9    2333   791.2 2333.78   799.7 2338.34   804.8 2338.91
   834.7  2336.9   864.6 2336.88   876.6 2342.58   925.5 2361.05   966.6  2378.9
#Mann= 6 ,-1 , 0
       0      .1       0    85.5    .045       0   120.4      .1       0
  195.59     .05       0  718.86     .06       0  857.06      .1       0
#XS Ineff= 2 , 0
                          147.71         2333.57
Permanent Ineff=
       F       F
Bank Sta=85.5,120.4
XS Rating Curve= 0 ,0
Exp/Cntr=0.3,0.1

Type RM Length L Ch R = 1 ,60759   ,327.2,336.4,338.7
XS GIS Cut Line= 2
2254284.34107938 387190.616101222253652.39680523 387994.43568781
#Sta/Elev= 30
       0 2421.88    62.9 2408.61    92.2 2397.99   108.5 2387.94   124.9 2374.23
   143.6 2353.84   146.4 2349.44   150.6 2339.93   152.9 2337.33   166.9  2328.2
     216 2327.27   239.4 2323.86   296.6 2321.23   315.1 2321.55   320.4 2323.65
     330 2326.87   467.7    2327   538.4 2329.28   734.8 2331.38   755.7    2333
   769.7 2337.24   789.1 2337.82   797.8 2335.41   805.8 2335.41   865.5 2341.71
   928.6 2345.43   933.3 2346.82   947.7 2356.83  1005.7 2379.45  1022.5 2384.45
#Mann= 7 ,-1 , 0
       0      .1       0   239.4    .045       0   320.4      .1       0
  346.63     .07       0  437.33     .05       0   687.8     .06       0
  830.46      .1       0
Bank Sta=239.4,320.4
XS Rating Curve= 0 ,0
Exp/Cntr=0.3,0.1

Type RM Length L Ch R = 1 ,60423   ,468.8,471.4,470.9
XS GIS Cut Line= 3
2254110.73020613386956.2412418872253751.35494064387294.782887638
2253346.84131397387609.019135803
#Sta/Elev= 30
       0 2382.38    30.1 2378.75    69.6 2368.68   122.1 2364.98   146.3 2360.31
   155.6 2355.25   159.8 2349.16   165.1 2338.86   169.3 2334.28   184.3 2326.54
   269.1 2323.66     286 2324.41  293.762321.026   301.6 2318.84   343.4  2321.3
   366.6 2322.04   404.4 2320.02   437.9  2322.3   517.7 2320.59     527  2321.2
     539 2325.01   755.1 2325.22   788.9 2334.34   817.4 2334.97   832.4 2343.35
   873.1 2355.22   903.5 2366.25   971.3 2400.41   979.4 2406.66  1005.9 2421.76
#Mann= 7 ,-1 , 0
       0      .1       0  293.76    .045       0   343.4      .1       0
  472.42     .05       0   703.4     .06       0  826.73      .1       0
  965.17      .1       0
#XS Ineff= 2 , 0
          286.59 2327.09  440.07         2327.26
Permanent Ineff=
       F       F
Bank Sta=293.76,343.4
XS Rating Curve= 0 ,0
Exp/Cntr=0.3,0.1

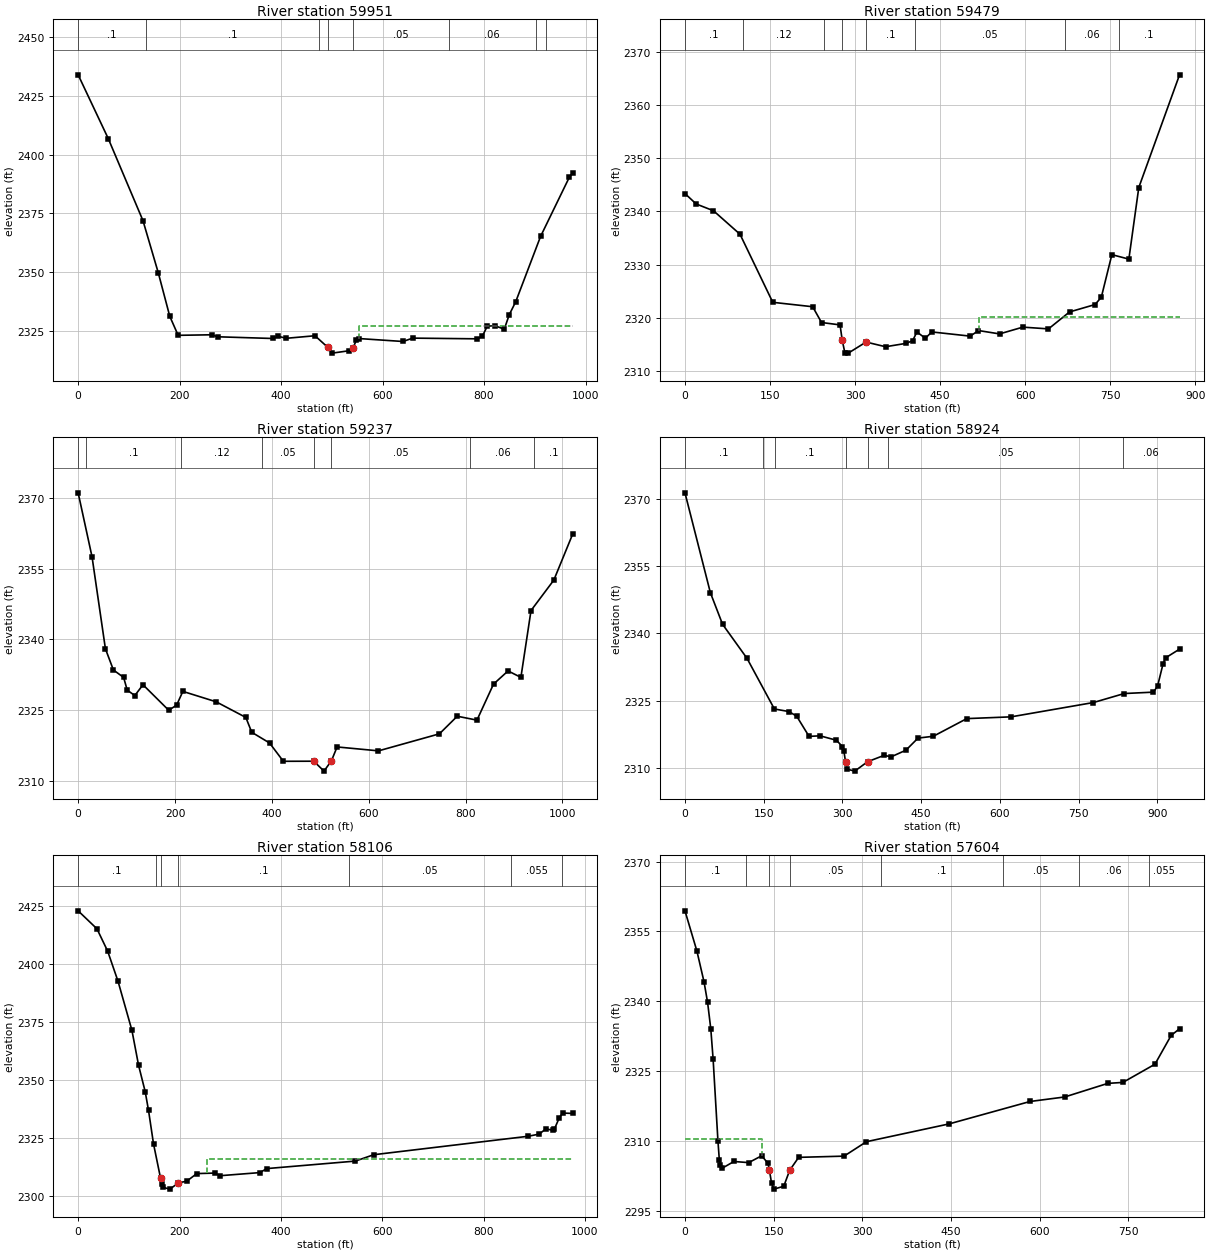
Type RM Length L Ch R = 1 ,59951   ,473,472.9,475.2
XS GIS Cut Line= 2
2254020.45217147386754.8525370662253171.49389564387234.018901557
#Sta/Elev= 30
       0 2433.93    59.4  2406.8   127.8 2371.92     158 2349.73   180.6 2331.26
   197.1 2323.18   263.5 2323.41   274.8 2322.56     384 2321.83   394.5 2322.75
   410.4 2321.92   466.8    2323  491.842318.108   500.8 2315.61   534.2 2316.63
   542.2 2317.96   548.6 2321.34   553.3 2321.81   640.3 2320.56   659.4 2321.99
   787.1 2321.69   796.7 2322.82   806.3 2327.02   820.8 2327.32   839.9 2325.78
   849.7 2331.94   862.5 2337.48   911.4 2365.21   967.9 2390.29   974.8 2392.26
#Mann= 8 ,-1 , 0
       0      .1       0  133.71      .1       0  475.55     .05       0
  491.84    .045       0   542.2     .05       0  730.01     .06       0
  902.34      .1       0   922.1      .1       0
#XS Ineff= 2 , 0
                          553.48         2327.26
Permanent Ineff=
       F       F
Bank Sta=491.84,542.2
XS Rating Curve= 0 ,0
Exp/Cntr=0.3,0.1

Type RM Length L Ch R = 1 ,59479   ,233.1,241.3,221.9
XS GIS Cut Line= 2
2253723.57743713386407.6301343892252957.95232797386826.032840893
#Sta/Elev= 30
       0 2343.35    19.8 2341.39    50.3 2340.12    97.1 2335.71   154.9 2322.93
   225.3  2322.1   240.9 2319.14   273.6 2318.69  277.362315.848   282.1 2313.45
   288.1 2313.39   319.5 2315.47   353.9 2314.59   390.5 2315.23   401.7 2315.74
   409.2 2317.36   424.1 2316.18   435.4 2317.37   503.3 2316.58   517.8 2317.63
     555    2317   596.1 2318.27   641.3 2317.94   678.4 2321.12   723.4 2322.51
   734.5 2323.88   753.1 2331.88   783.1 2331.04   800.6 2344.48   872.5 2365.64
#Mann= 8 ,-1 , 0
       0      .1       0  102.93     .12       0  244.42      .1       0
  277.36    .045       0   319.5      .1       0  405.87     .05       0
  670.55     .06       0  765.34      .1       0
#XS Ineff= 2 , 0
                          519.52         2320.25
Permanent Ineff=
       F       F
Bank Sta=277.36,319.5
XS Rating Curve= 0 ,0
Exp/Cntr=0.3,0.1

Type RM Length L Ch R = 1 ,59237   ,301.1,312.9,312.1
XS GIS Cut Line= 5
2253688.71825489386143.6214760542253295.03465906 386434.89418748
2253279.46218364386447.4440311492253263.89069247386459.994202897
2252888.52038021386777.165156484
#Sta/Elev= 30
       0 2371.16    28.7 2357.55    56.3 2338.01    72.8  2333.5    93.9 2331.92
   101.3 2329.22     117 2328.07   133.9 2330.36     187 2324.94   203.3 2326.03
   216.2 2328.95   284.9 2326.74   346.2 2323.42   358.4 2320.26   395.1 2317.99
   423.7 2314.09   486.5 2314.11   507.6    2312  523.012314.213   534.6 2317.14
   620.1 2316.31   745.9 2319.93   782.7 2323.67   823.4 2322.84   857.6  2330.5
   887.6  2333.3   914.1 2331.93     935 2346.14   982.1 2352.61  1021.1 2362.41
#Mann= 8 ,-1 , 0
       0      .1       0   16.84      .1       0  213.13     .12       0
  379.94     .05       0   486.5    .045       0  523.01     .05       0
  809.42     .06       0  942.16      .1       0
Bank Sta=486.5,523.01
XS Rating Curve= 0 ,0
Exp/Cntr=0.3,0.1

Type RM Length L Ch R = 1 ,58924   ,836.4,818.7,788.1
XS GIS Cut Line= 3
2253544.75791289386039.5744400622253089.89661789386201.032778561
2252706.21628289386454.505040646
#Sta/Elev= 30
       0 2371.29    48.4 2349.07    71.6 2342.04   118.2 2334.46   170.4 2323.18
   198.2 2322.61   212.9 2321.57   236.5 2317.08   257.4 2317.21   288.7 2316.22
   300.2 2314.79   302.7 2313.93   306.1 2311.35   309.6 2309.77   323.6 2309.35
   347.9 2311.44   379.3 2312.85   393.2 2312.55   421.1 2314.01   444.1  2316.7
   473.3 2317.11   537.1 2321.04   621.5 2321.43   778.5 2324.62   837.1 2326.62
   892.8 2326.93   900.6 2328.27   911.2 2333.29     916 2334.57   942.5  2336.5
#Mann= 7 ,-1 , 0
       0      .1       0  148.42     .12       0  171.26      .1       0
   306.1    .045       0   347.9      .1       0  387.39     .05       0
  834.67     .06       0
Bank Sta=306.1,347.9
XS Rating Curve= 0 ,0
Exp/Cntr=0.3,0.1

Type RM Length L Ch R = 1 ,58106   ,510,501.9,491.1
XS GIS Cut Line= 3
2252687.98698863385451.0329662262252701.87606847385826.032872394
2252637.63964839386423.255103141
#Sta/Elev= 30
       0 2422.94    37.1  2415.2    58.3 2405.55    78.8 2392.54   106.1  2371.5
   119.2 2356.47   132.3  2345.1   138.9 2336.99   148.7 2322.65  162.512307.944
   165.2 2305.25   168.4 2303.86     181 2303.13   197.9 2305.82   214.4 2306.56
   234.1 2309.82   269.7 2310.04   280.1 2308.91   358.9 2310.25     372 2311.97
   546.9  2315.2   583.2 2317.94   887.8 2325.88   909.8 2326.82     923 2329.09
   936.2 2328.47   939.5 2328.85   949.4 2333.85     956 2335.87   975.9 2335.73
#Mann= 7 ,-1 , 0
       0      .1       0   153.9     .12       0  162.51    .045       0
   197.9      .1       0  535.07     .05       0  854.33    .055       0
  955.28     .06       0
#XS Ineff= 2 , 0
                          253.54         2316.01
Permanent Ineff=
       F       F
Bank Sta=162.51,197.9
XS Rating Curve= 0 ,0
Exp/Cntr=0.3,0.1

Type RM Length L Ch R = 1 ,57604   ,581.9,593.6,602.6
XS GIS Cut Line= 2
2252142.84798706385668.0469678942252599.44549905 386369.43565698
#Sta/Elev= 30
       0 2359.42    20.2 2350.79    32.3 2344.15    38.3 2339.76    43.7 2334.08
    47.6 2327.67    55.8 2310.03    58.1 2306.03    59.3 2304.82    63.3  2304.2
    82.8 2305.62   107.9 2305.38   129.8 2306.85   140.5 2305.22  142.892303.765
   146.5 2300.98   150.6 2299.69   167.2 2300.31   177.2 2303.73   192.4 2306.51
   269.2 2306.77   307.1 2309.87     447 2313.69   583.9  2318.5   642.6 2319.47
   715.6 2322.39     741 2322.59   795.3  2326.5   822.7 2332.68   836.9 2334.11
#Mann= 8 ,-1 , 0
       0      .1       0   102.7     .05       0  142.89    .045       0
   177.2     .05       0  332.28      .1       0  537.61     .05       0
  665.95     .06       0  785.22    .055       0
#XS Ineff= 2 , 0
           129.6 2310.49
Permanent Ineff=
       F       F
Bank Sta=142.89,177.2
XS Rating Curve= 0 ,0
Exp/Cntr=0.3,0.1

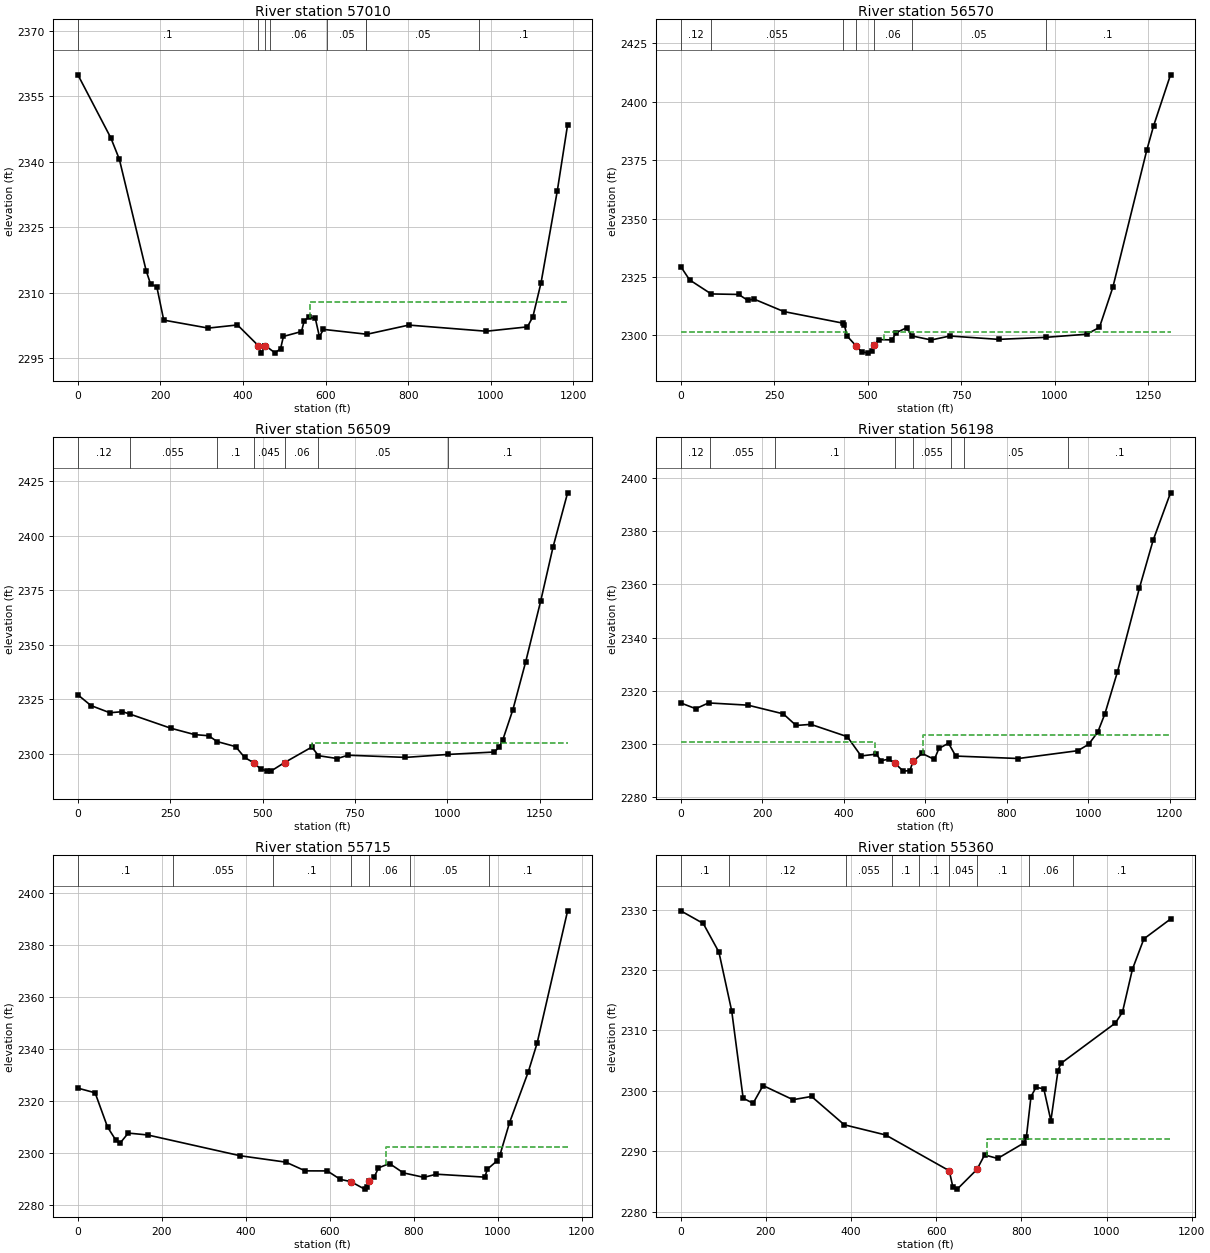
Type RM Length L Ch R = 1 ,57010   ,435.1,440.6,443.7
XS GIS Cut Line= 3
2251802.57045239385577.7689332222251674.09826839386122.907934815
2251585.55645072386742.699674234
#Sta/Elev= 30
       0 2359.91    79.8 2345.44   100.4 2340.55   165.3 2315.01   176.2 2311.88
     191 2311.37   207.9 2303.67   315.8 2301.84   386.5 2302.56   437.1  2297.8
   443.8  2296.1     454 2297.81   454.4  2297.8   477.5 2296.14     491 2297.14
   497.8 2299.93   541.6 2301.05   548.3 2303.57     559 2304.29     575  2304.1
     585 2299.88   594.9 2301.54   700.1 2300.43   801.6 2302.53   989.3 2301.12
  1088.7 2302.12    1102 2304.41  1121.9 2312.25  1161.2  2333.3  1186.2 2348.49
#Mann= 8 ,-1 , 0
       0      .1       0   437.1    .045       0     454      .1       0
  464.53     .06       0  603.94     .05       0  697.28      .1       0
  698.57     .05       0  972.09      .1       0
#XS Ineff= 2 , 0
                          562.31         2307.85
Permanent Ineff=
       F       F
Bank Sta=437.1,454.4
XS Rating Curve= 0 ,0
Exp/Cntr=0.5,0.3

Type RM Length L Ch R = 1 ,56570   ,62.8,60.8,61.9
XS GIS Cut Line= 4
2251568.19526497385529.1578099732251302.57046814385860.755243897
2251253.95934489385977.0745650532250983.12589705386685.407794058
#Sta/Elev= 30
       0 2329.43    23.5 2323.77    81.2 2317.76   154.7 2317.54   178.6 2315.07
     196 2315.54   275.3 2310.22   433.5 2305.25   437.3 2304.42   444.8  2299.7
     469 2295.44   483.3    2293     501 2292.42   511.7 2293.32   517.5 2295.97
     530 2298.21   564.9 2298.07   575.4 2301.12   603.5 2303.28   617.6 2299.79
   669.5 2298.06   719.4 2299.75   849.4 2298.31   975.8 2299.18  1084.7 2300.51
  1119.3 2303.43    1155 2320.55  1246.2 2379.52  1264.1 2389.75  1309.3 2411.56
#Mann= 7 ,-1 , 0
       0     .12       0    81.2    .055       0   433.5      .1       0
     469    .045       0   517.5     .06       0   617.6     .05       0
   975.8      .1       0
#XS Ineff= 2 , 0
             444 2301.28   542.5         2301.28
Permanent Ineff=
       F       F
Bank Sta=469,517.5
XS Rating Curve= 0 ,0
Exp/Cntr=0.5,0.3

Type RM Length L Ch R = 1 ,56509   ,291.3,310.4,327
XS GIS Cut Line= 4
2251556.04273023385503.1161953962251247.01480497385841.657841146
2251196.66746472385956.2412733882250943.19520263386654.157856554
#Sta/Elev= 30
       0 2327.02    35.3 2322.11    86.5  2318.8   120.6  2319.3   139.8 2318.25
   251.3 2311.72   316.3 2308.77   354.2 2308.26   376.7  2305.6   427.2 2303.26
   451.5 2298.29   477.2 2295.74   494.5 2293.02     513 2292.02   523.7 2292.14
   559.6 2295.95   633.5 2303.06   651.5  2299.1   702.7 2297.79   731.2 2299.32
   887.1 2298.32  1002.3 2299.68  1127.8 2300.79  1140.6 2303.02  1150.1 2306.12
    1178 2320.26  1212.3 2341.99  1253.3 2370.13  1286.5 2394.72  1326.1  2419.7
#Mann= 7 ,-1 , 0
       0     .12       0   139.8    .055       0   376.7      .1       0
   477.2    .045       0   559.6     .06       0   651.5     .05       0
  1002.3      .1       0
#XS Ineff= 2 , 0
                          634.84         2305.03
Permanent Ineff=
       F       F
Bank Sta=477.2,559.6
XS Rating Curve= 0 ,0
Exp/Cntr=0.5,0.3

Type RM Length L Ch R = 1 ,56198   ,472.8,483,490.3
XS GIS Cut Line= 2
2251451.87594381385457.9775061462250399.79274614386039.574440062
#Sta/Elev= 30
       0 2315.49    36.7 2313.33    68.1  2315.5     165 2314.66   251.6 2311.39
     283 2307.03   319.2 2307.45   408.7 2302.82   442.5 2295.58   479.9 2296.27
   491.2  2293.8   509.9 2294.34   524.9 2292.92   546.1 2289.88   562.4 2290.08
   569.9 2293.52   592.4 2296.53   622.4 2294.27   633.6  2298.4   657.2 2300.36
   674.9 2295.54   828.6 2294.62   974.8 2297.56    1001 2299.95  1023.5 2304.52
    1041  2311.4  1071.7  2327.1  1125.5 2358.51  1159.3 2376.56  1202.1 2394.43
#Mann= 8 ,-1 , 0
       0     .12       0   71.56    .055       0  231.17      .1       0
   524.9    .045       0   569.9    .055       0  662.13     .06       0
  694.56     .05       0  951.64      .1       0
#XS Ineff= 2 , 0
          477.76  2300.8  594.23         2303.37
Permanent Ineff=
       F       F
Bank Sta=524.9,569.9
XS Rating Curve= 0 ,0
Exp/Cntr=0.3,0.1

Type RM Length L Ch R = 1 ,55715   ,348.1,354.9,364.2
XS GIS Cut Line= 3
2251387.63985181 385263.533013152250651.52879122385326.032888144
 2250224.4453278385350.338613808
#Sta/Elev= 30
       0 2324.92      41 2323.12    70.6 2309.93    90.4 2304.88   100.3 2303.72
     120 2307.61   166.1 2306.89   386.7 2298.88   495.4 2296.42   541.5 2293.06
   594.1 2293.04   624.9  2289.8   650.1 2288.92     683 2286.03   689.6 2286.73
  694.132289.148   706.1 2290.76     716 2294.22   742.3 2295.88   775.2 2292.29
   824.2 2290.57     854 2291.78   969.1 2290.65   975.6 2293.74   998.6 2296.96
  1005.2 2299.09  1028.2 2311.67    1073 2331.27  1093.9 2342.27  1166.5  2393.2
#Mann= 7 ,-1 , 0
       0      .1       0   227.4    .055       0  463.71      .1       0
   650.1    .045       0  694.13     .06       0  792.11     .05       0
  978.68      .1       0
#XS Ineff= 2 , 0
                          734.13         2302.16
Permanent Ineff=
       F       F
Bank Sta=650.1,694.13
XS Rating Curve= 0 ,0
Exp/Cntr=0.3,0.1

Type RM Length L Ch R = 1 ,55360   ,683.8,664.6,664.9
XS GIS Cut Line= 4
2251434.51475805385109.0188864772250875.48700473384996.171671227
2250601.18145098384926.7272563132250311.25092848384990.963348314
#Sta/Elev= 30
       0 2329.79    52.7  2327.7    89.5 2322.96   119.6 2313.21   146.4  2298.8
   169.8 2297.96   193.2 2300.89   263.5 2298.55     307 2299.09     384  2294.4
   481.1 2292.72   630.5  2286.8   638.9 2284.14   649.3 2283.76   695.6 2287.02
   713.6 2289.42   744.1 2288.83   806.3 2291.41   811.8 2292.46   822.5 2299.07
   834.4  2300.6   852.6 2300.35   869.2 2295.09     886 2303.38   892.7 2304.55
  1020.7 2311.23  1037.3 2313.02  1060.7 2320.12  1087.6 2325.15  1150.2 2328.43
#Mann= 9 ,-1 , 0
       0      .1       0  112.81     .12       0     389    .055       0
  495.13      .1       0  560.57      .1       0   630.5    .045       0
   695.6      .1       0  818.37     .06       0  920.68      .1       0
#XS Ineff= 2 , 0
                          719.19         2292.12
Permanent Ineff=
       F       F
Bank Sta=630.5,695.6
XS Rating Curve= 0 ,0
Exp/Cntr=0.3,0.1

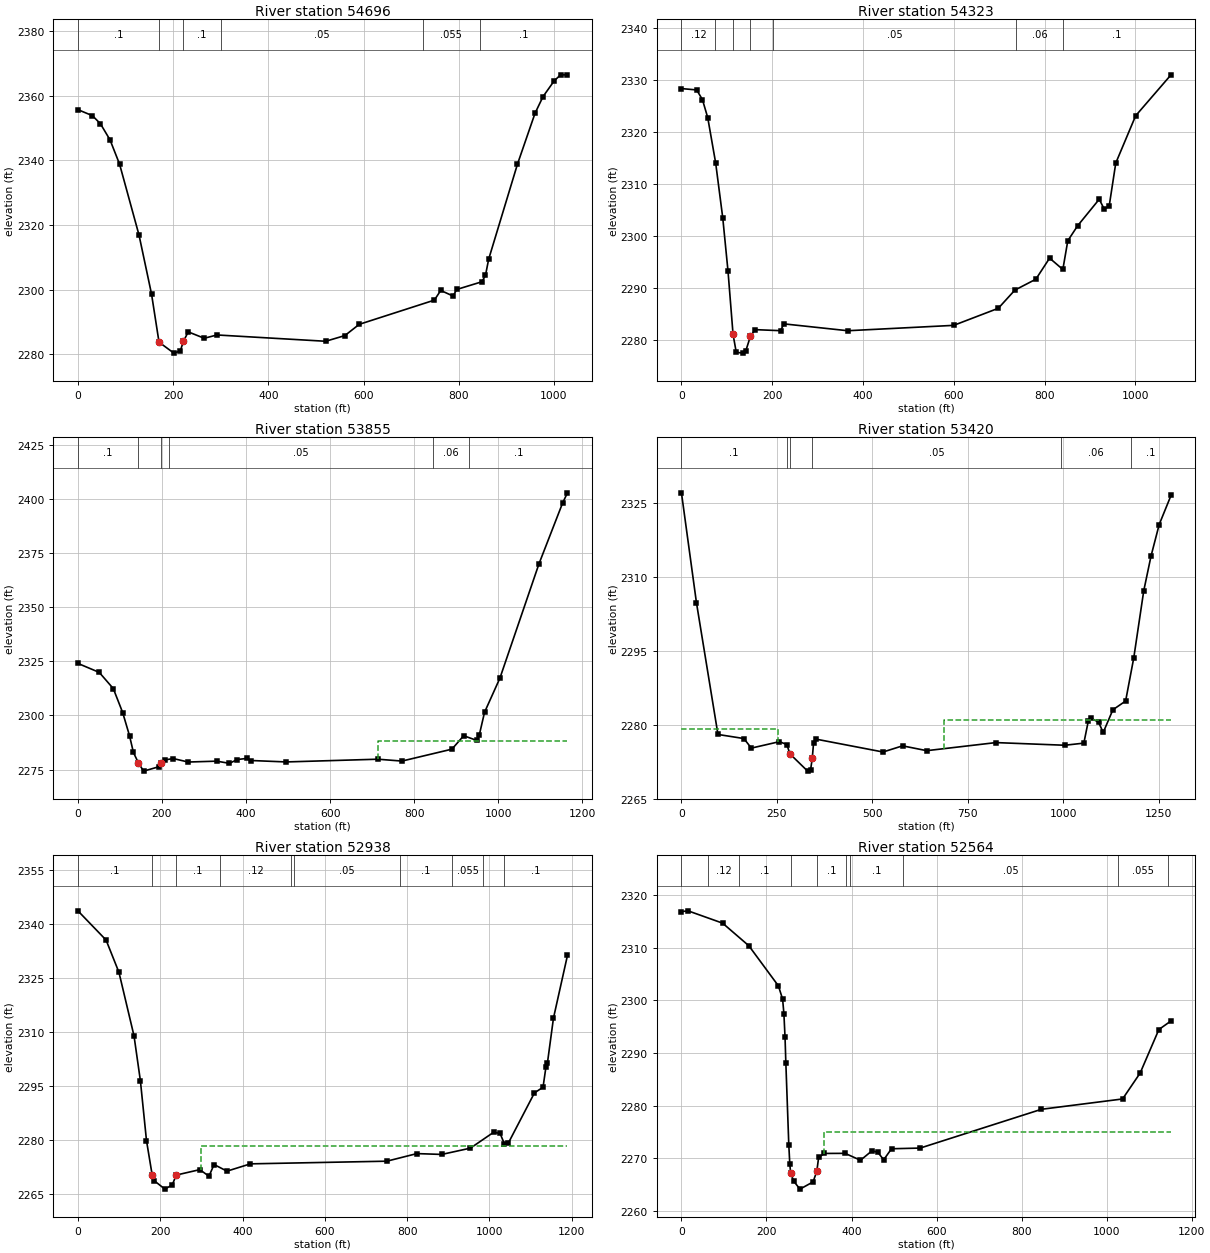
Type RM Length L Ch R = 1 ,54696   ,370.7,372.8,366.9
XS GIS Cut Line= 3
2251307.77879106384437.143917888 2250998.7508658384503.116226897
2250302.57049964384654.157919556
#Sta/Elev= 30
       0 2355.71    30.5 2353.84    47.3 2351.35    67.5 2346.35    87.6 2338.82
   128.4 2316.89   154.7 2298.64  170.41 2283.76   201.6 2280.36   215.1 2281.03
   221.8 2284.05   231.8 2286.94   265.4 2284.96   292.2 2285.98   520.5 2284.03
   560.8 2285.79     591 2289.27   748.8 2296.76   762.2 2299.76   788.1 2298.02
   795.8 2300.06   848.8 2302.45   856.2 2304.43   862.9 2309.43   923.3 2338.79
   960.3 2354.59   977.1 2359.74  1000.5 2364.61    1014 2366.48  1028.4 2366.48
#Mann= 6 ,-1 , 0
       0      .1       0  170.41    .045       0   221.8      .1       0
  300.25     .05       0  724.36    .055       0  844.31      .1       0
Bank Sta=170.41,221.8
XS Rating Curve= 0 ,0
Exp/Cntr=0.3,0.1

Type RM Length L Ch R = 1 ,54323   ,475.4,467.8,458.9
XS GIS Cut Line= 3
2251217.50075638384072.5606575612250983.12589705384157.630041227
2250236.59819064384518.741195649
#Sta/Elev= 30
       0  2328.3    33.5 2328.04    46.2 2326.19    57.9 2322.72    75.4    2314
      91 2303.48   102.6 2293.21   113.7  2281.1   120.7 2277.68   134.7 2277.51
   141.7 2277.93   152.1 2280.78   162.6 2282.02   218.5 2281.82   225.5 2283.13
   366.4 2281.81   599.8 2282.84   698.1 2286.12   734.6 2289.61   780.8  2291.7
   811.1 2295.75   840.3 2293.57   851.2 2299.09   873.1 2301.99   920.5 2307.06
   931.4 2305.15   942.3  2305.7   956.9    2314  1000.7 2323.08  1078.6 2330.94
#Mann= 7 ,-1 , 0
       0     .12       0   74.57      .1       0   113.7    .045       0
   152.1      .1       0  201.04     .05       0  737.84     .06       0
  841.49      .1       0
Bank Sta=113.7,152.1
XS Rating Curve= 0 ,0
Exp/Cntr=0.3,0.1

Type RM Length L Ch R = 1 ,53855   ,423.4,435.6,432.1
XS GIS Cut Line= 2
2251024.79248039383605.5468278082250123.75097539 384343.39410539
#Sta/Elev= 30
       0 2324.01    50.8 2319.86    84.2  2312.4   106.5 2301.34   122.8 2290.66
   132.1  2282.9   143.8 2278.16   156.3  2274.3   192.7 2276.33   198.7 2277.97
   206.7 2279.47   226.9  2280.1   262.3  2278.5   330.3  2278.9   360.6 2277.89
   379.2 2279.66   402.2 2280.17   411.9  2279.2   495.5 2278.54   713.6  2279.8
   770.9 2278.94   889.7 2284.43   917.8 2290.64   949.2 2288.44   955.1 2291.17
   967.4 2301.47    1004 2317.25  1096.8 2369.92  1153.2 2398.08  1164.6 2402.72
#Mann= 6 ,-1 , 0
       0      .1       0   143.8    .045       0   198.7      .1       0
  217.59     .05       0  844.98     .06       0  931.32      .1       0
#XS Ineff= 2 , 0
                          714.43         2288.14
Permanent Ineff=
       F       F
Bank Sta=143.8,198.7
XS Rating Curve= 0 ,0
Exp/Cntr=0.3,0.1

Type RM Length L Ch R = 1 ,53420   ,486.1,482.1,477.2
XS GIS Cut Line= 2
2250802.57048389383352.0745657242249719.23702064384037.838614151
#Sta/Elev= 30
       0 2327.02    39.3 2304.72    95.6    2278   163.5 2277.17     183 2275.23
   256.7 2276.54   276.1 2275.95   283.9 2274.07   330.5 2270.56   338.1 2270.77
  342.59 2273.19     346 2276.26   352.4 2277.05   527.9 2274.44     579 2275.69
   642.4 2274.71   823.6 2276.35  1003.9 2275.81  1053.8 2276.24  1065.7  2280.8
  1072.8 2281.28  1092.3  2280.5  1104.5  2278.4  1129.9 2283.01  1163.2 2284.78
  1184.6 2293.56  1210.7 2307.15  1229.7 2314.17  1251.1 2320.58  1282.1 2326.49
#Mann= 6 ,-1 , 0
       0      .1       0  276.14     .05       0   283.9    .045       0
  342.59     .05       0  994.98     .06       0 1176.56      .1       0
#XS Ineff= 2 , 0
          252.74  2279.2  687.72         2280.85
Permanent Ineff=
       F       F
Bank Sta=283.9,342.59
XS Rating Curve= 0 ,0
Exp/Cntr=0.3,0.1

Type RM Length L Ch R = 1 ,52938   ,373.5,373.8,375
XS GIS Cut Line= 4
2250370.27869755383095.1301977342250123.75097539383322.560845226
2249665.41757447383826.0329353962249549.09825331383954.505119398
#Sta/Elev= 30
       0 2343.74    68.5 2335.61    99.8 2326.62   136.4 2308.95   151.9 2296.46
   166.7 2279.82   180.5 2270.27   185.7 2268.66   211.4 2266.34   229.3 2267.53
     239 2270.25   296.2 2271.76   318.5 2269.93   330.9 2273.18   362.3 2271.34
   419.3 2273.37   750.7 2274.11   823.7 2276.22   884.2 2275.99   953.8 2277.74
  1010.1 2282.14  1025.8 2281.85  1036.6 2278.88  1045.5 2279.05  1109.4  2293.1
  1130.3 2294.69  1137.3 2300.29    1141 2301.46  1155.6 2313.89  1189.6 2331.33
#Mann= 10 ,-1 , 0
       0      .1       0   180.5    .045       0     239      .1       0
  345.31     .12       0  518.61      .1       0  525.84     .05       0
  781.87      .1       0  908.74    .055       0  985.08     .06       0
 1035.65      .1       0
#XS Ineff= 2 , 0
                          298.81         2278.22
Permanent Ineff=
       F       F
Bank Sta=180.5,239
XS Rating Curve= 0 ,0
Exp/Cntr=0.3,0.1

Type RM Length L Ch R = 1 ,52564   ,546.8,550.2,555.8
XS GIS Cut Line= 4
 2250128.9592983382831.2412898092249976.18138863382964.921796724
2249849.44542164383077.7690119742249312.98717697383642.005088225
#Sta/Elev= 30
       0 2316.84    15.4 2316.99    96.8 2314.65   158.5 2310.36     228 2302.75
   237.9 2300.23   240.9  2297.5   243.6 2292.98   245.5 2288.11   252.5 2272.47
   254.8 2268.93   256.8 2267.21   264.1 2265.68   278.7 2264.18   309.5 2265.55
   318.3 2267.56   322.6 2270.19   335.8 2270.95   384.8 2270.97     421 2269.66
   448.2 2271.46   461.8 2271.17   475.6 2269.75     494 2271.84   561.4 2271.97
   846.6 2279.33  1037.4 2281.29  1078.8 2286.22  1122.7 2294.46  1151.3  2296.1
#Mann= 10 ,-1 , 0
       0      .1       0   61.64     .12       0  136.19      .1       0
   256.8    .045       0   318.3      .1       0  387.28     .12       0
  396.12      .1       0  520.87     .05       0 1026.59    .055       0
 1144.61     .06       0
#XS Ineff= 2 , 0
                          334.13            2275
Permanent Ineff=
       F       F
Bank Sta=256.8,318.3
XS Rating Curve= 0 ,0
Exp/Cntr=0.3,0.1