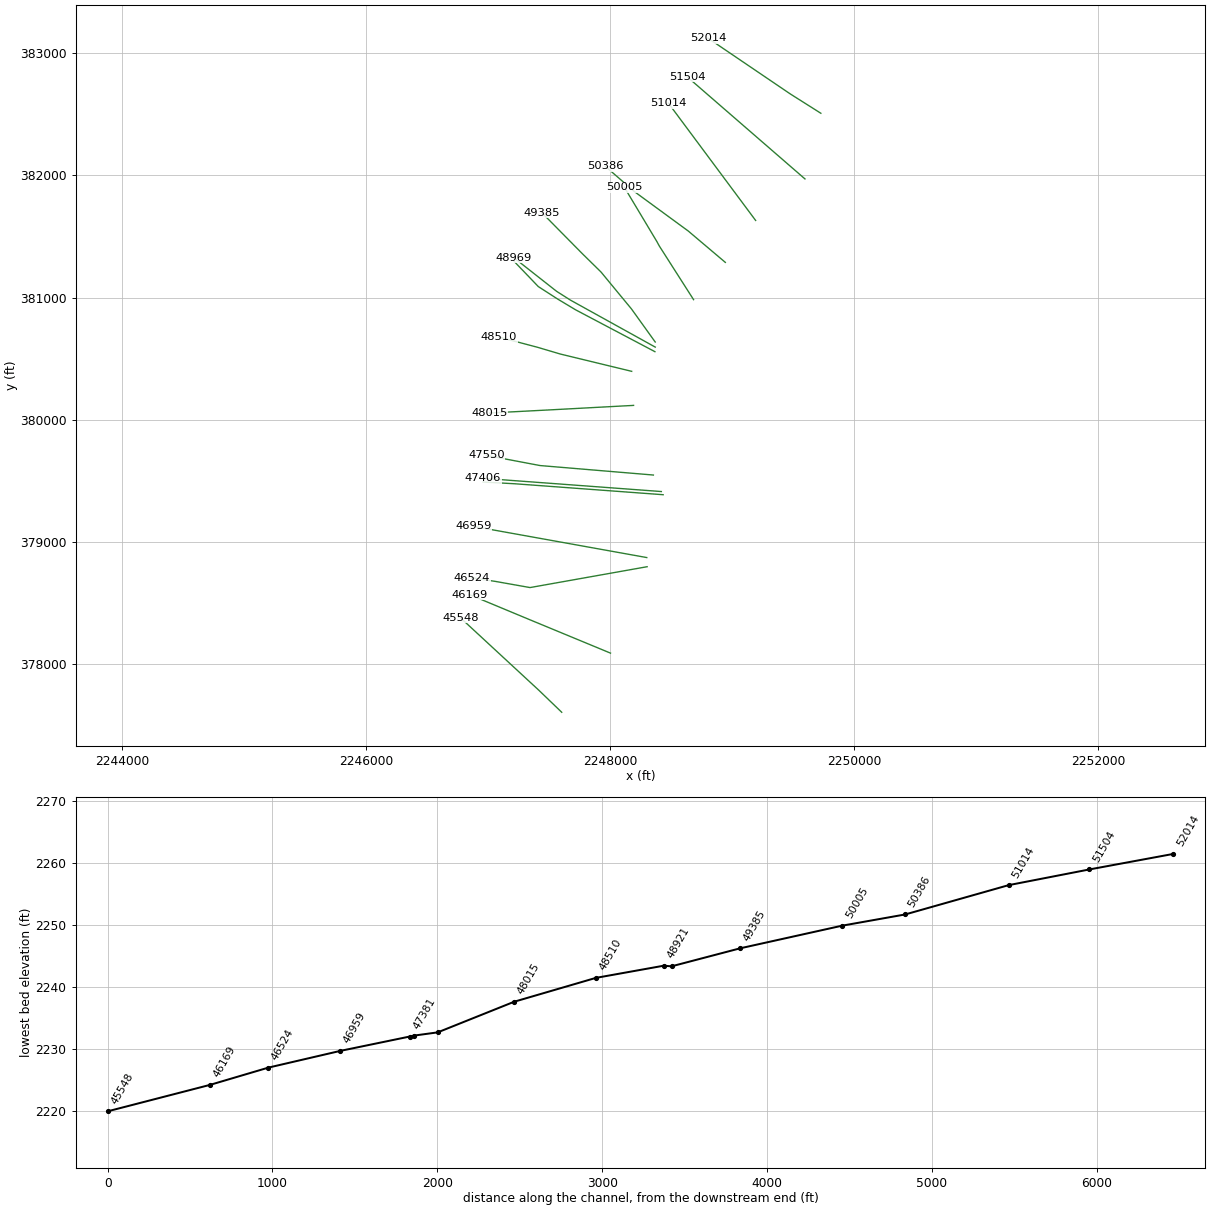
HEC-RAS study MFANTNYCK.prj: MFANTNYCK

--- MFANTNYCK.g01 (geometry) --- (continued)

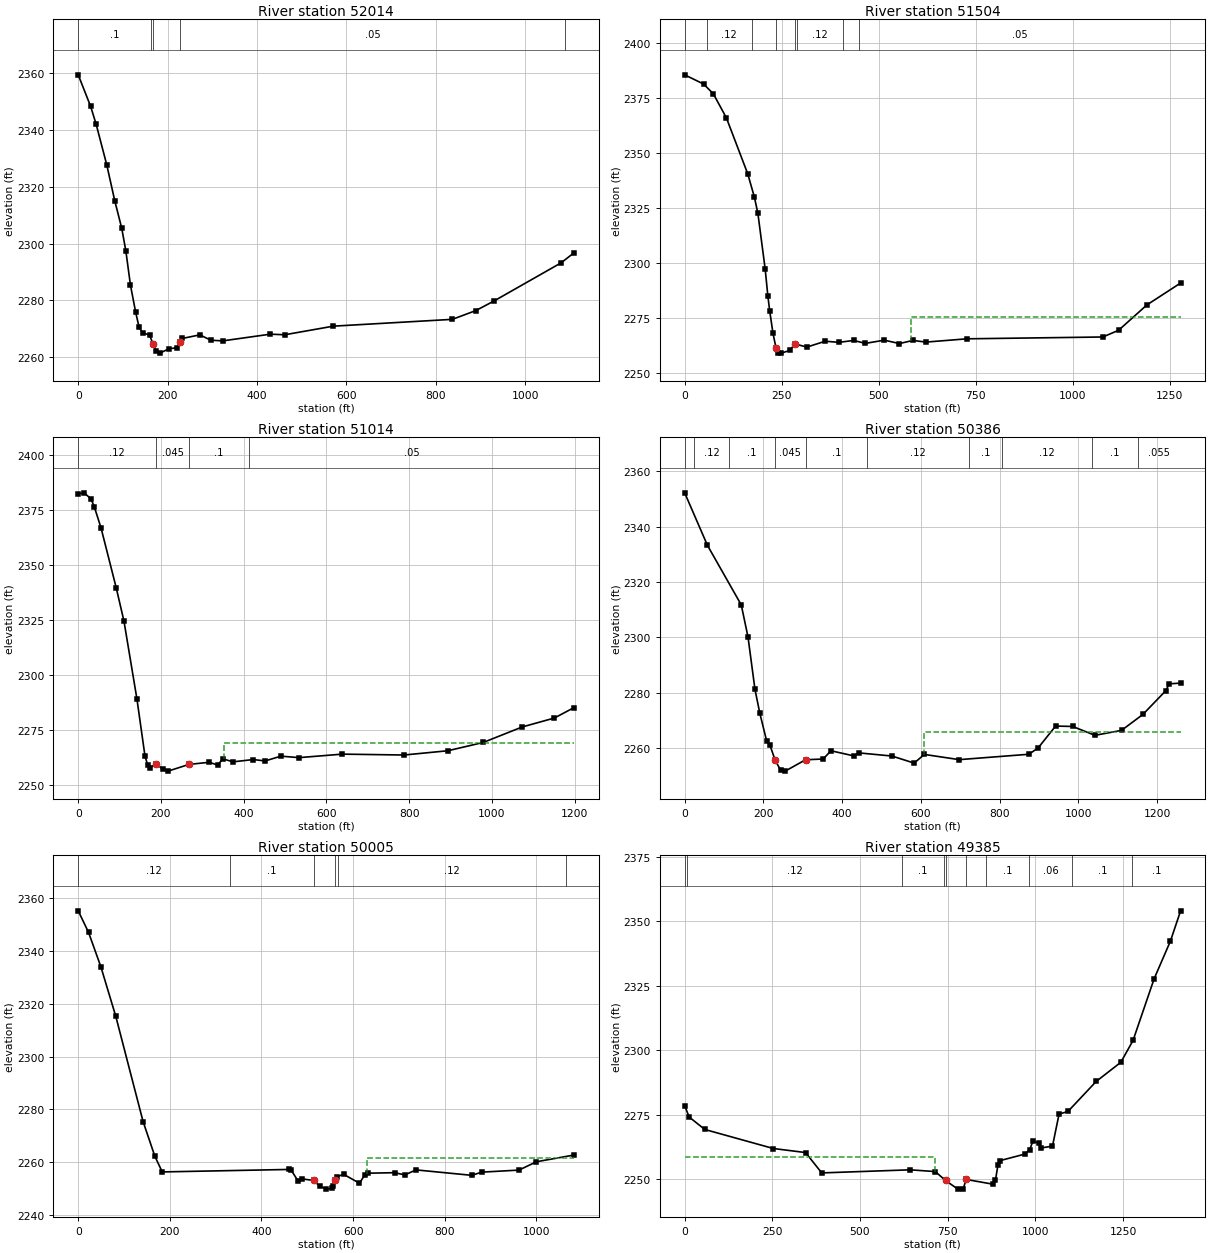
Type RM Length L Ch R = 1 ,52014   ,510.8,509.4,506.3
XS GIS Cut Line= 3
2249729.65366647382510.0608298032249479.65383838382668.046734303
 2248806.0426528383124.643918231
#Sta/Elev= 30
       0 2359.43    27.5 2348.43      40  2342.1    63.8 2327.76    81.9 2314.97
    97.4 2305.37   106.6 2297.38   116.8 2285.44   128.4  2275.9   136.2 2270.51
     144 2268.56   159.5  2267.8   167.2 2264.73     175 2262.06   182.5 2261.41
   204.1 2263.02   221.6 2263.25  227.882265.256   233.2 2266.59     272 2267.84
   296.8 2265.96   323.1 2265.72   430.1 2268.09   461.8 2267.87   570.8 2270.91
     837 2273.31   889.6  2276.4   929.5 2279.71  1080.1 2293.19  1109.5 2296.78
#Mann= 5 ,-1 , 0
       0      .1       0  163.19     .05       0   167.2    .045       0
  227.88     .05       0 1089.11    .055       0
Bank Sta=167.2,227.88
XS Rating Curve= 0 ,0
Exp/Cntr=0.3,0.1

Type RM Length L Ch R = 1 ,51504   ,492.4,490.3,476
XS GIS Cut Line= 2
2249599.44526547381971.8663681452248634.16766848382808.671781138
#Sta/Elev= 30
       0  2385.5    48.9 2381.29    73.9 2376.84   107.4 2365.94   162.4 2340.48
   179.5 2329.91   188.5 2322.56   207.4 2297.11   214.3 2284.81     219 2278.16
   227.5 2267.86   235.3  2261.3   240.6 2259.16   249.2 2258.91     271 2260.18
     284 2263.09   314.8 2261.66   362.1 2264.33   396.9 2263.81   435.3 2264.67
   465.5 2263.35   514.1  2264.8   553.2 2263.27   587.9 2264.68   621.4 2263.93
   726.9 2265.42  1077.2 2266.25  1117.7  2269.3  1190.8 2280.86  1277.5  2290.8
#Mann= 8 ,-1 , 0
       0      .1       0   56.75     .12       0   173.5      .1       0
   235.3    .045       0     284      .1       0  290.26     .12       0
  407.01      .1       0  448.81     .05       0
#XS Ineff= 2 , 0
                          582.34         2275.38
Permanent Ineff=
       F       F
Bank Sta=235.3,284
XS Rating Curve= 0 ,0
Exp/Cntr=0.3,0.1

Type RM Length L Ch R = 1 ,51014   ,608.2,627.9,601.6
XS GIS Cut Line= 2
2249194.93131071381631.588505387 2248479.6535418382593.393996477
#Sta/Elev= 30
       0 2382.17    14.2 2382.62    30.6 2379.94    38.7 2376.37    55.1 2366.74
    91.9 2339.51   110.6 2324.39   142.1 2288.89   161.4 2263.17   167.8 2259.22
   172.5  2257.7     189  2259.8     204 2257.19   217.1 2256.38   267.7 2259.43
   316.8 2260.39   337.2 2259.12   349.5 2261.97     374 2260.59   423.1 2261.63
   451.7    2261   489.9 2263.17   533.6  2262.5   638.3 2264.09   787.4 2263.69
   893.3 2265.62   978.9 2269.39  1073.2 2276.42  1150.8 2280.47  1198.6 2285.23
#Mann= 4 ,-1 , 0
       0     .12       0     189    .045       0   267.7      .1       0
   412.3     .05       0
#XS Ineff= 2 , 0
                          352.46         2268.94
Permanent Ineff=
       F       F
Bank Sta=189,267.7
XS Rating Curve= 0 ,0
Exp/Cntr=0.3,0.1

Type RM Length L Ch R = 1 ,50386   ,383.5,381.4,336.9
XS GIS Cut Line= 4
2248946.66769964381287.8385367242248642.84809731381544.782904729
2248201.87588213381867.699581727 2247964.0285888382074.296937555
#Sta/Elev= 30
       0 2352.18    57.7 2333.24   143.7  2311.7   160.9 2300.04   178.5 2281.19
   190.9 2272.52   208.1 2262.61   216.7 2260.98   229.7 2255.62   243.7 2251.99
   255.3 2251.66     307 2255.77   351.8 2256.03   371.4 2259.02   430.8 2257.12
     442 2258.25   526.5 2257.11   582.8 2254.56   608.5 2257.69   697.4 2255.81
   873.9 2257.75   897.4    2260     942 2267.94   985.4 2267.79  1041.9 2264.59
  1109.4 2266.38  1163.6 2272.12  1222.2 2280.77  1230.4 2283.18  1259.5 2283.46
#Mann= 10 ,-1 , 0
       0      .1       0   23.77     .12       0  112.62      .1       0
   229.7    .045       0     307      .1       0  464.26     .12       0
  721.88      .1       0  806.79     .12       0 1033.84      .1       0
 1150.66    .055       0
#XS Ineff= 2 , 0
                           607.7         2265.93
Permanent Ineff=
       F       F
Bank Sta=229.7,307
XS Rating Curve= 0 ,0
Exp/Cntr=0.3,0.1

Type RM Length L Ch R = 1 ,50005   ,604,619.8,625.4
XS GIS Cut Line= 5
2248686.36736722380982.3404600622248404.75638188381423.235247567
 2248395.2245768381440.8175614772248385.69244364381458.400203481
2248118.88753106381903.818603978
#Sta/Elev= 30
       0 2355.18    22.5 2347.05    49.4 2334.03    81.9 2315.32   141.6 2275.41
   167.4 2262.24   183.4 2256.37   460.8 2257.31   464.7 2257.08   480.3  2252.8
     488 2253.75   514.2 2253.13   526.8 2250.97   541.7 2249.86   552.9 2250.18
   556.7 2251.23     560 2253.46   564.2 2254.56   579.5 2255.44   613.9 2252.09
   625.3 2255.22     633 2255.89   690.4 2256.08   712.9 2255.24   737.1 2257.14
     859 2255.08   880.6 2256.29   961.9 2257.06  1000.1 2260.22  1082.4 2262.77
#Mann= 6 ,-1 , 0
       0     .12       0  331.29      .1       0   514.2    .045       0
     560      .1       0  567.44     .12       0  1064.2      .1       0
#XS Ineff= 2 , 0
                           630.9         2261.71
Permanent Ineff=
       F       F
Bank Sta=514.2,560
XS Rating Curve= 0 ,0
Exp/Cntr=0.3,0.1

Type RM Length L Ch R = 1 ,49385   ,405.2,416.2,412.4
XS GIS Cut Line= 5
2248372.01464947380635.0606428092248177.57048455380905.894090638
2247927.16514547 381209.482066142247775.08178823381358.787541807
2247441.74846539381696.287522972
#Sta/Elev= 30
       0 2278.53    12.8 2274.14    57.4 2269.32   252.7 2261.95   344.7 2260.38
   390.9 2252.49   642.9 2253.69   714.7 2253.01   743.9 2249.56   779.1 2246.21
   794.5 2246.32   802.5 2249.97   879.7 2248.11   886.4 2249.73   893.6  2255.7
   898.2 2257.21   969.7 2259.77   984.1 2261.51     993 2264.77  1009.6 2264.11
  1016.5 2262.16    1049 2262.88  1067.7 2275.28  1093.1  2276.3  1173.5 2287.92
  1243.9 2295.35  1278.7 2303.81    1339 2327.76  1385.2 2342.27  1414.4 2354.03
#Mann= 10 ,-1 , 0
       0      .1       0     7.3     .12       0  620.51      .1       0
  738.63     .12       0   743.9    .045       0   802.5     .12       0
  860.27      .1       0  982.37     .06       0 1105.37      .1       0
 1276.65      .1       0
#XS Ineff= 2 , 0
          712.62 2258.54
Permanent Ineff=
       F       F
Bank Sta=743.9,802.5
XS Rating Curve= 0 ,0
Exp/Cntr=0.5,0.3

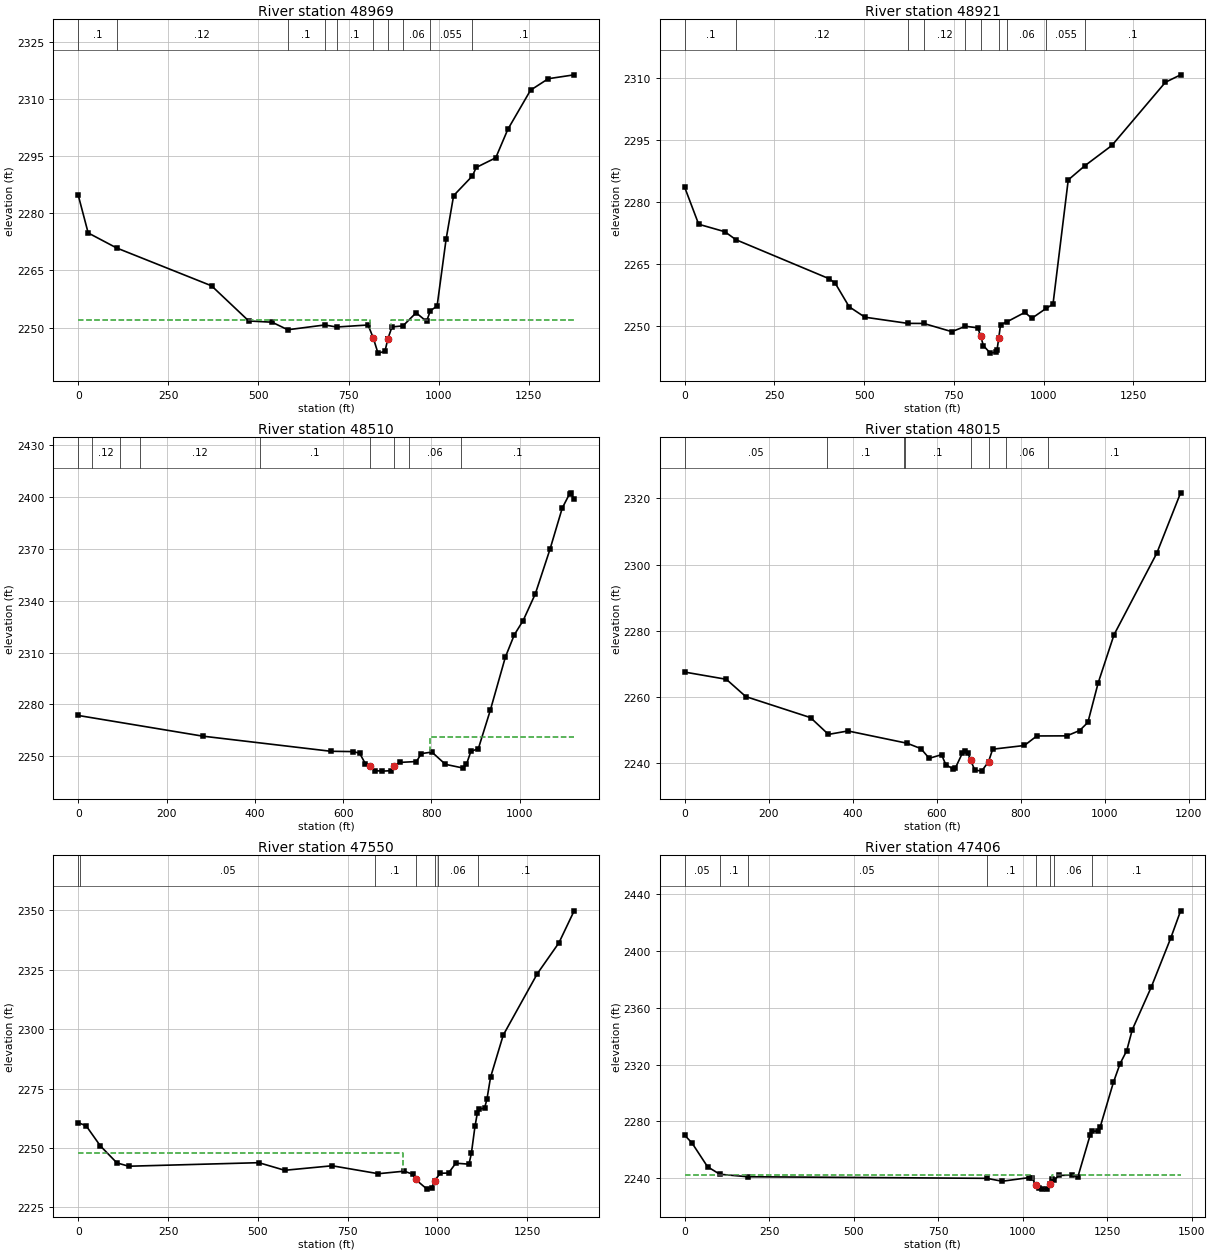
Type RM Length L Ch R = 1 ,48969   ,48.7,47.4,48.1
XS GIS Cut Line= 4
2248372.30401897380593.5098728982247677.85986981380978.231872484
2247563.97066189381050.4541689752247212.58192897381326.843051896
#Sta/Elev= 30
       0 2284.74    27.6 2274.83   106.8 2270.88   369.9 2260.96   473.1 2251.74
   537.7 2251.42   581.4 2249.44   683.6 2250.69   717.4 2250.16   804.2 2250.69
  818.692247.242   831.6 2243.31     851 2243.78   858.8 2246.99   858.8 2247.01
   870.4 2250.18     901 2250.46   937.3 2253.88   966.3 2251.65   976.9 2254.42
   995.6 2255.66  1020.5 2273.14  1041.4 2284.61  1093.7 2289.79    1104 2291.99
  1158.3 2294.53  1191.8 2301.99  1254.9 2312.27    1304 2315.27  1375.8 2316.29
#Mann= 10 ,-1 , 0
       0      .1       0   106.8     .12       0   581.4      .1       0
   683.6     .12       0   717.4      .1       0  818.69    .045       0
   858.8      .1       0     901     .06       0   976.9    .055       0
  1093.7      .1       0
#XS Ineff= 2 , 0
          808.69 2252.03   868.8         2252.03
Permanent Ineff=
       F       F
Bank Sta=818.69,858.8
XS Rating Curve= 0 ,0
Exp/Cntr=0.5,0.3

Type RM Length L Ch R = 1 ,48921   ,406.3,411.5,418.8
XS GIS Cut Line= 5
2248369.52646548380556.0099478962247719.52645314380899.065364137
2247573.69308339380986.5651891382247413.97096188381089.343198806
2247215.35981056381296.287666813
#Sta/Elev= 30
       0 2283.48      39 2274.55   111.7 2272.75   142.9 2270.81   402.7 2261.38
   419.7 2260.26   458.2 2254.62   502.2 2252.09   621.5  2250.6     666 2250.58
   744.2  2248.6   782.4  2249.9   816.9 2249.51   824.5 2247.55   832.2 2245.24
   851.3 2243.41   867.3 2243.65   870.4 2244.22   875.2 2247.14     880 2250.25
   899.2 2251.03   947.8 2253.25   967.3 2251.83  1007.2 2254.23  1026.2 2255.22
  1068.7 2285.26  1115.2  2288.7  1190.2 2293.58  1339.4 2308.85  1381.8 2310.65
#Mann= 10 ,-1 , 0
       0      .1       0   142.9     .12       0   621.5      .1       0
     666     .12       0   782.4      .1       0   824.5    .045       0
   875.2      .1       0   899.2     .06       0  1007.2    .055       0
  1115.2      .1       0
Bank Sta=824.5,875.2
XS Rating Curve= 0 ,0
Exp/Cntr=0.5,0.3

Type RM Length L Ch R = 1 ,48510   ,484.4,494.6,501.9
XS GIS Cut Line= 4
2248179.24863081380394.8987215612247594.52637506380536.565432981
2247407.02642196380592.1207680552247091.74850921380675.454262808
#Sta/Elev= 30
       0 2273.66     282 2261.69   572.3 2252.93   623.2 2252.75   637.4 2251.79
   650.6 2245.66   660.9 2244.43   671.1 2241.74   688.2 2241.45   708.8 2241.69
   715.6 2244.54   729.3  2246.5   766.1 2247.01   777.2 2251.59   801.1 2252.47
   831.7 2245.38   872.4  2243.2   879.2 2245.29   889.3 2252.83   906.3 2254.45
   933.5 2276.76   967.5 2307.42   987.8 2320.34  1007.8 2328.59  1035.3 2343.99
  1068.7 2369.92  1096.3 2393.62  1113.3 2402.08  1116.7 2402.47  1123.3 2398.76
#Mann= 9 ,-1 , 0
       0      .1       0   31.44     .12       0    94.1      .1       0
   139.9     .12       0  412.24      .1       0   660.9    .045       0
   715.6      .1       0  749.33     .06       0   866.1      .1       0
#XS Ineff= 2 , 0
                          795.93         2261.48
Permanent Ineff=
       F       F
Bank Sta=660.9,715.6
XS Rating Curve= 0 ,0
Exp/Cntr=0.3,0.1

Type RM Length L Ch R = 1 ,48015   ,468.7,464.9,458.8
XS GIS Cut Line= 3
2248194.52648738380115.7319570632247522.30407855 380079.62080881
2247015.35955438380053.232082054
#Sta/Elev= 30
       0 2267.53    99.2 2265.35   145.5 2260.13   299.6 2253.78   342.3 2248.71
   388.8 2249.75   529.6 2246.04   562.4 2244.42   582.2 2241.49   611.7 2242.58
   621.6 2239.57     638 2238.35   644.6  2238.6     661 2243.01   667.6 2243.57
   674.1 2243.19   680.7 2240.96   690.6 2237.96     707 2237.62   723.4 2240.45
   733.3 2244.24   808.8 2245.36   838.4 2248.24   909.8 2248.27   940.3 2249.88
     960 2252.34   984.4 2264.22  1022.2 2278.79  1124.2 2303.47  1180.8 2321.66
#Mann= 8 ,-1 , 0
       0     .05       0  339.66      .1       0  521.18     .05       0
   523.8      .1       0   680.7    .045       0   723.4      .1       0
  764.05     .06       0  865.67      .1       0
Bank Sta=680.7,723.4
XS Rating Curve= 0 ,0
Exp/Cntr=0.3,0.1

Type RM Length L Ch R = 1 ,47550   ,141.9,144,146.4
XS GIS Cut Line= 3
2248357.02649046379544.8987811512247427.85971364379622.676512733
2246987.58205089379706.009679392
#Sta/Elev= 30
       0 2260.65    22.1 2259.34    61.6 2250.88   107.7 2243.72   140.6 2242.32
   502.8 2243.81   574.8 2240.61   706.9 2242.51   835.3 2239.17   907.7 2240.24
   930.8 2238.96   938.9 2236.79   970.8 2232.68   984.2 2233.25   992.2 2236.23
  1007.6 2239.35  1030.9 2239.46    1051 2243.59  1087.7 2243.19  1094.4 2247.72
  1104.5 2259.17  1111.1 2264.75  1115.7 2266.34  1131.1 2266.76  1137.8  2270.6
  1147.8 2279.78  1183.1 2297.51    1278 2323.38  1338.1 2336.36  1380.5 2349.83
#Mann= 7 ,-1 , 0
       0      .1       0    5.14     .05       0  825.42      .1       0
   938.9    .045       0   992.2      .1       0 1001.19     .06       0
 1111.82      .1       0
#XS Ineff= 2 , 0
          904.81 2247.96
Permanent Ineff=
       F       F
Bank Sta=938.9,992.2
XS Rating Curve= 0 ,0
Exp/Cntr=0.5,0.3

Type RM Length L Ch R = 1 ,47406   ,25.2,25.3,25.6
XS GIS Cut Line= 2
2248422.29210797379409.6392091362246958.75041564379518.145881891
#Sta/Elev= 30
       0 2270.19    21.7 2264.69    67.8 2247.91     104 2242.65   186.2 2240.89
   893.5 2239.78   939.6 2237.73  1018.6 2240.26  1028.4 2239.93  1038.3 2235.38
  1048.2 2232.63    1058 2232.16  1071.2 2232.52  1081.1 2235.77  1087.6    2239
  1094.2 2238.88  1108.2 2241.79  1146.9  2242.1  1163.3 2240.59  1199.5    2270
  1206.1 2272.96  1222.5 2273.16  1229.2 2275.67  1268.6 2307.37  1288.3 2320.59
  1308.1  2329.8  1324.5 2344.58  1380.4 2374.46  1438.7 2409.42  1467.6 2428.45
#Mann= 8 ,-1 , 0
       0     .05       0     104      .1       0   186.2     .05       0
   893.5      .1       0  1038.3    .045       0  1081.1      .1       0
  1094.2     .06       0  1206.1      .1       0
#XS Ineff= 2 , 0
          1031.3 2241.84  1088.1         2241.84
Permanent Ineff=
       F       F
Bank Sta=1038.3,1081.1
XS Rating Curve= 0 ,0
Exp/Cntr=0.5,0.3

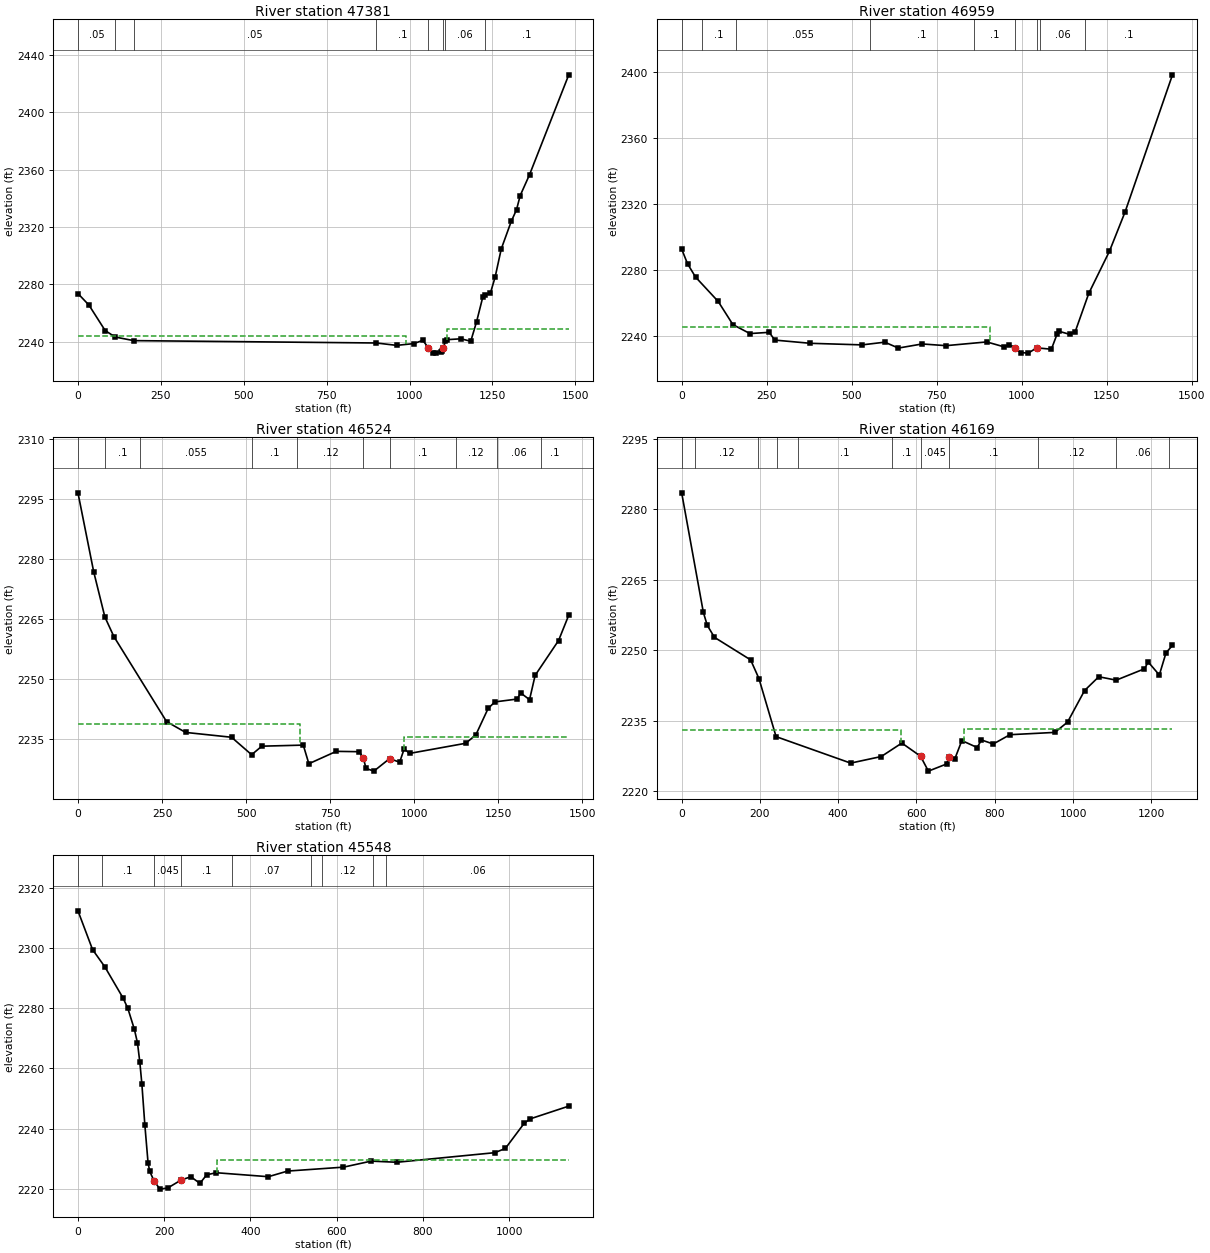
Type RM Length L Ch R = 1 ,47381   ,423.5,421.3,417.8
XS GIS Cut Line= 3
2248437.04896823379383.5975945592247226.11142947379473.007192642
2246960.48663263379487.764052898
#Sta/Elev= 30
       0 2273.55    33.2 2265.49      82 2247.78   112.2 2243.25   168.1 2240.73
   900.2 2239.08   961.2 2237.42  1013.6 2238.67  1039.9 2240.95  1056.4 2235.92
  1069.5 2232.32  1079.4 2232.01    1096 2233.02  1099.2 2233.59  1102.2 2235.78
  1108.3 2240.31  1114.4 2241.42  1155.1    2242  1184.7  2240.3  1202.2 2253.84
  1220.8 2270.92  1226.8  2272.6  1243.8  2273.8  1258.1 2284.91  1276.7 2304.68
  1306.8 2323.89  1322.7 2331.98  1333.8  2341.9  1361.9  2356.4  1480.3 2426.11
#Mann= 8 ,-1 , 0
       0     .05       0   112.2      .1       0   168.1     .05       0
   900.2      .1       0  1056.4    .045       0  1102.2      .1       0
  1108.3     .06       0  1226.8      .1       0
#XS Ineff= 2 , 0
          988.99 2243.89 1113.66         2248.98
Permanent Ineff=
       F       F
Bank Sta=1056.4,1102.2
XS Rating Curve= 0 ,0
Exp/Cntr=0.5,0.3

Type RM Length L Ch R = 1 ,46959   ,425,436,444.1
XS GIS Cut Line= 2
2248302.85960406378868.5097139782246882.02648772379124.065305233
#Sta/Elev= 30
       0 2292.66    17.3 2283.77    40.7 2275.77   107.4 2260.98   150.7 2246.95
   200.7 2241.54   257.4 2242.28     274 2237.59   378.2 2235.65   530.6 2234.69
   597.4 2236.33   637.4 2232.76   707.4 2235.25   777.4 2234.22   897.4 2236.48
   947.4 2233.55   964.1  2234.8   980.7 2232.68   997.4 2230.06  1019.6  2229.7
  1044.1 2232.91  1087.4 2232.06  1104.3 2241.26  1110.7 2242.86    1141 2241.09
  1157.4  2242.6  1197.4 2265.86  1258.2 2291.36  1304.1  2315.1  1443.6 2398.14
#Mann= 9 ,-1 , 0
       0      .1       0   59.98      .1       0  159.32    .055       0
  554.34      .1       0  860.55      .1       0   980.7    .045       0
  1044.1      .1       0 1053.38     .06       0 1187.75      .1       0
#XS Ineff= 2 , 0
          905.49 2245.33
Permanent Ineff=
       F       F
Bank Sta=980.7,1044.1
XS Rating Curve= 0 ,0
Exp/Cntr=0.3,0.1

Type RM Length L Ch R = 1 ,46524   ,363.9,354.3,323.9
XS GIS Cut Line= 4
2248305.63748564378793.5098639732247345.91532372378622.676544234
2247063.97067764378672.6764442322246868.13740788378703.232157394
#Sta/Elev= 30
       0 2296.53    46.8 2276.81    80.1  2265.5   106.8 2260.63   263.4 2239.39
   320.1 2236.68   456.7 2235.47   516.4 2231.11   546.7 2233.24     670 2233.51
   686.6 2228.86   768.1 2231.95   836.6 2231.86  848.852230.227   856.6 2227.68
   879.9 2227.01   926.6 2230.13   956.6 2229.24   969.9 2232.55   986.5 2231.44
  1153.2 2233.97  1183.2 2236.08  1219.8 2242.69  1239.8  2244.3  1306.3 2245.02
  1316.2 2246.56  1342.8 2244.86  1359.4 2250.93  1429.1 2259.64  1459.4 2265.97
#Mann= 10 ,-1 , 0
       0      .1       0   79.17      .1       0  184.42    .055       0
  517.93      .1       0   652.8     .12       0  848.85    .045       0
   926.6      .1       0 1122.82     .12       0 1246.42     .06       0
  1376.3      .1       0
#XS Ineff= 2 , 0
           659.2 2238.79  968.87         2235.48
Permanent Ineff=
       F       F
Bank Sta=848.85,926.6
XS Rating Curve= 0 ,0
Exp/Cntr=0.3,0.1

Type RM Length L Ch R = 1 ,46169   ,622.3,621.4,601.6
XS GIS Cut Line= 3
2248005.63742948378085.1763068882247344.52621889 378358.78763631
2246847.30411622378565.732104316
#Sta/Elev= 30
       0 2283.52    55.4 2258.05    65.4 2255.29    83.8 2252.73   176.2 2247.93
   197.5 2243.94   241.2 2231.58   431.8 2225.94     510 2227.34   562.6 2230.21
   610.3 2227.41   630.4 2224.23   676.8 2225.75   683.2 2227.31   698.1 2226.87
   715.9 2230.74     755 2229.26     766 2230.87   796.1 2230.01   838.8 2231.99
   953.4 2232.48   985.9 2234.66  1029.5  2241.4  1065.8 2244.34  1110.3 2243.61
  1182.5 2246.03  1192.1 2247.48  1220.5 2244.71  1237.7 2249.46  1254.1 2251.01
#Mann= 11 ,-1 , 0
       0      .1       0   34.37     .12       0  195.21      .1       0
  242.92     .12       0  297.26      .1       0  537.48      .1       0
   610.3    .045       0   683.2      .1       0  909.65     .12       0
 1108.93     .06       0  1245.9      .1       0
#XS Ineff= 2 , 0
          560.95 2232.93  722.58          2233.1
Permanent Ineff=
       F       F
Bank Sta=610.3,683.2
XS Rating Curve= 0 ,0
Exp/Cntr=0.3,0.1

Type RM Length L Ch R = 1 ,45548   ,273.8,274.5,268.3
XS GIS Cut Line= 3
 2247605.6375733377600.4541792272247419.52639697 377779.62081565
2246773.69304296378376.843046397
#Sta/Elev= 30
       0 2312.28    33.9 2299.41    62.3 2293.71   104.9 2283.28   115.7  2279.9
   130.7 2273.04     138 2268.49   143.5 2262.01   148.2 2254.82   155.1 2241.24
   162.5 2228.76   166.4 2225.88     176 2222.83   189.9 2219.97   208.1 2220.34
     240 2223.06   261.9 2224.06   282.8 2221.88   298.4 2224.72   320.7 2225.41
   441.4 2224.09   486.1 2225.96   615.7 2227.26   679.8 2229.26   739.4 2228.88
   966.5 2232.06     991 2233.46    1035 2241.87  1049.1  2243.3    1138  2247.5
#Mann= 9 ,-1 , 0
       0     .06       0   56.35      .1       0     176    .045       0
     240      .1       0  358.15     .07       0  539.33      .1       0
  565.89     .12       0  685.07     .05       0   714.1     .06       0
#XS Ineff= 2 , 0
                           321.9         2229.55
Permanent Ineff=
       F       F
Bank Sta=176,240
XS Rating Curve= 0 ,0
Exp/Cntr=0.3,0.1