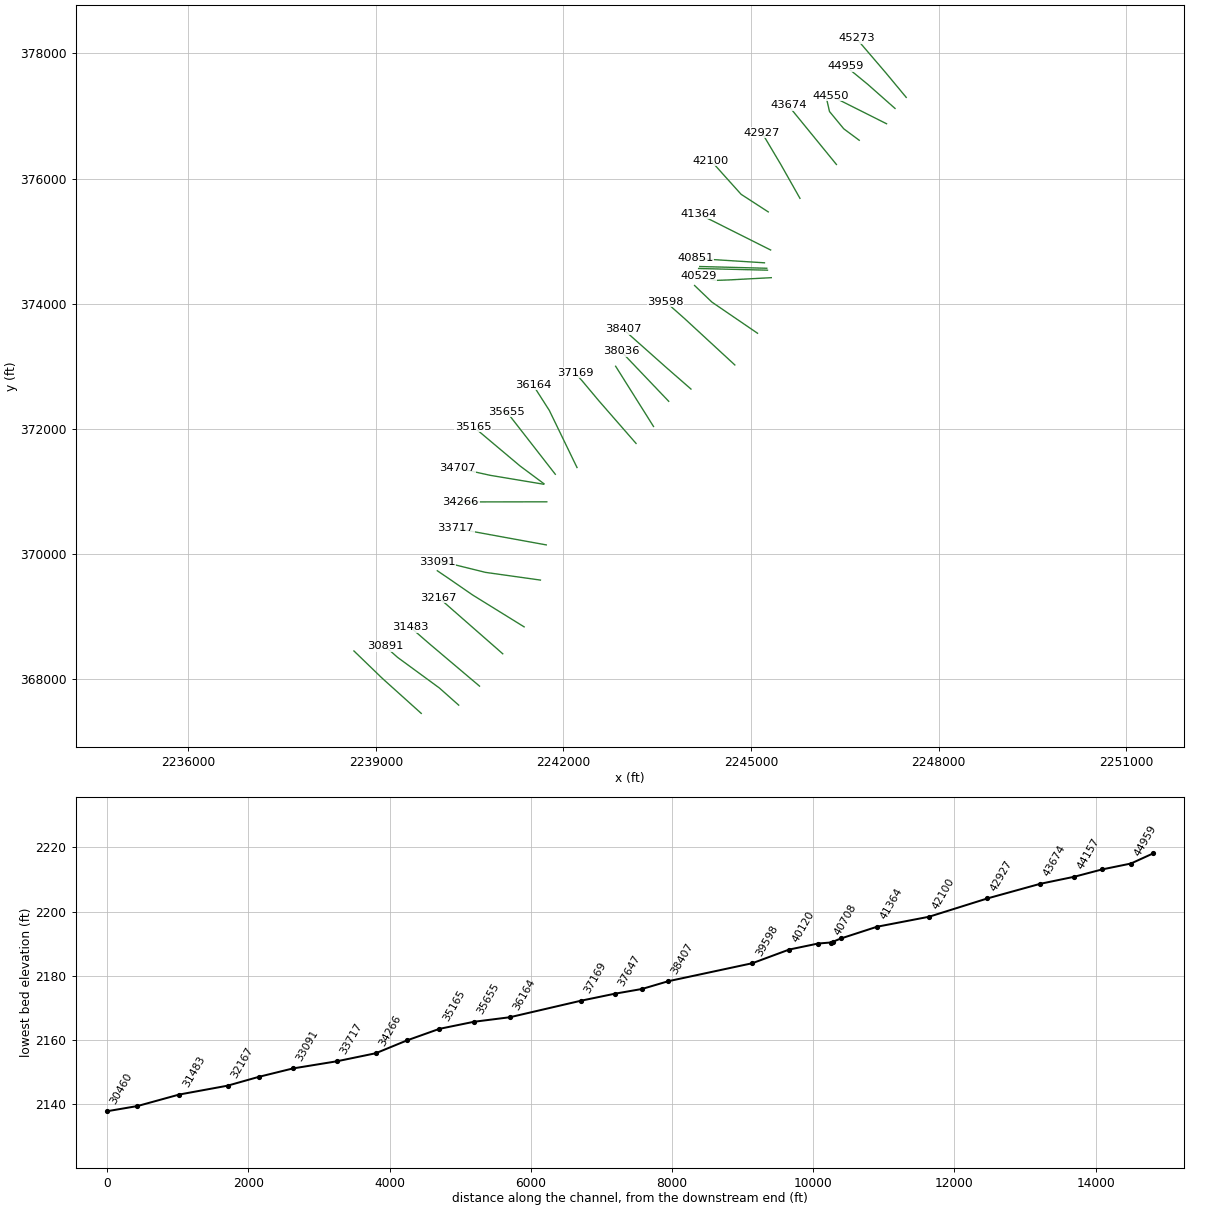
HEC-RAS study MFANTNYCK.prj: MFANTNYCK

--- MFANTNYCK.g01 (geometry) --- (continued)

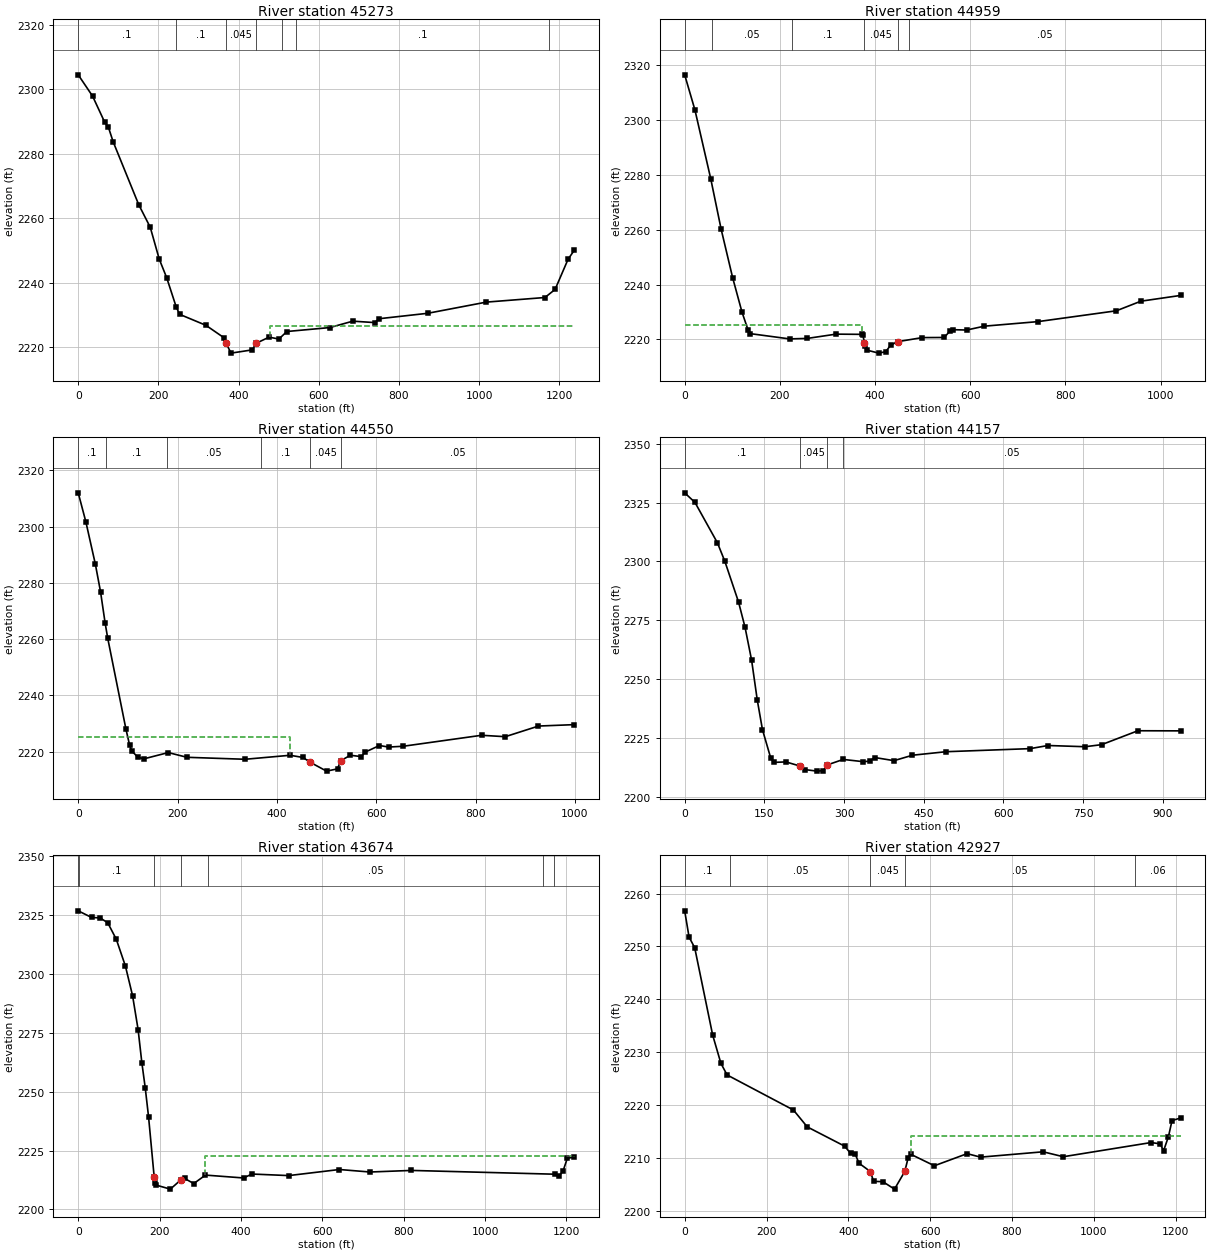
Type RM Length L Ch R = 1 ,45273   ,309.4,314.5,320.6
XS GIS Cut Line= 3
2247481.97213823 377297.974469232247159.05546123377686.863127142
2246683.36087455 378242.41877456
#Sta/Elev= 30
       0  2304.5    35.8  2297.9    66.1 2289.78    75.4  2288.2      87 2283.77
   150.8 2264.24   179.7 2257.18     202 2247.34   220.8 2241.49   244.6 2232.39
   253.1 2230.17   318.4 2226.78     364 2222.88     369 2221.19   381.1 2218.14
   434.2 2219.15   443.5 2221.18   476.1  2223.1   500.5 2222.51   520.4 2224.85
   627.4 2226.07   684.9 2228.06   739.1 2227.62   750.7 2228.82   871.6  2230.5
  1017.8 2233.97  1164.1  2235.4  1189.4 2237.92  1221.7 2247.26  1236.9 2250.02
#Mann= 7 ,-1 , 0
       0      .1       0  243.03      .1       0     369    .045       0
   443.5      .1       0  508.32     .07       0  542.81      .1       0
 1173.68     .06       0
#XS Ineff= 2 , 0
                          477.76         2226.53
Permanent Ineff=
       F       F
Bank Sta=369,443.5
XS Rating Curve= 0 ,0
Exp/Cntr=0.3,0.1

Type RM Length L Ch R = 1 ,44959   ,396.6,408.6,412.3
XS GIS Cut Line= 3
2247303.15261397377120.8911619782246869.12493873377504.571496978
2246511.48589022377797.974453479
#Sta/Elev= 30
       0 2316.55    21.5 2303.76    54.7 2278.66    76.6 2260.21   100.7 2242.56
   120.4 2229.95   133.5 2223.26   137.9 2222.09   220.4 2220.17   257.6 2220.35
     318 2221.91   373.2 2221.83   374.4  2221.6  377.642218.664   378.8 2217.54
   383.1 2216.06   407.9 2214.98   422.5 2215.52   432.6 2217.87   447.5 2219.17
   499.3 2220.65   545.2 2220.69   557.4 2223.05   564.4 2223.53   592.3 2223.41
   629.6 2224.82   741.7 2226.47   906.9 2230.43   958.3 2233.93  1041.9 2236.04
#Mann= 6 ,-1 , 0
       0      .1       0    57.1     .05       0  225.46      .1       0
  377.64    .045       0   447.5      .1       0  472.02     .05       0
#XS Ineff= 2 , 0
          371.48 2225.33
Permanent Ineff=
       F       F
Bank Sta=377.64,447.5
XS Rating Curve= 0 ,0
Exp/Cntr=0.3,0.1

Type RM Length L Ch R = 1 ,44550   ,396.3,393.1,387
XS GIS Cut Line= 2
2247167.73589006376876.0993287272246275.37481388377324.016083807
#Sta/Elev= 30
       0 2311.98    15.5  2301.6    34.6 2286.57    44.9 2276.89    54.2 2265.72
    59.5 2260.26    96.2 2227.97   103.6 2222.29     108 2220.28   120.2 2218.06
   132.4 2217.51   181.3 2219.73     219 2218.05     336 2217.35   426.6 2218.77
   452.6 2217.99   467.2 2216.27     500 2213.14   522.1 2213.95   528.3  2216.8
   547.9 2218.78   569.9 2218.29   577.4 2219.86   606.5 2222.24   624.9 2221.69
   654.2 2221.97   812.1 2225.87   859.8 2225.37   926.7 2229.15   998.5 2229.65
#Mann= 6 ,-1 , 0
       0      .1       0    55.7      .1       0  178.93     .05       0
  368.03      .1       0   467.2    .045       0   528.3     .05       0
#XS Ineff= 2 , 0
          425.58 2225.33
Permanent Ineff=
       F       F
Bank Sta=467.2,528.3
XS Rating Curve= 0 ,0
Exp/Cntr=0.3,0.1

Type RM Length L Ch R = 1 ,44157   ,490.3,483.5,475.2
XS GIS Cut Line= 4
2246730.23578081376612.2104208172246483.70805864376794.502050981
2246254.54152222377072.2800387292246195.51375313 377332.69651264
#Sta/Elev= 30
       0 2329.12    19.4 2325.03    61.6  2307.9    75.7 2299.97   101.4 2282.72
   113.7 2271.93     126    2258   136.6 2241.17   146.4 2228.51   162.1 2216.33
   167.7 2214.58   190.6 2214.77   216.4 2213.07   225.8 2211.53   249.2 2210.86
   260.6 2211.04   268.8 2213.53   298.5 2215.83   336.1 2214.88   348.4 2215.09
   357.5 2216.65   394.1 2215.31   428.9 2217.62     492 2219.11   650.5 2220.42
     684 2221.75   753.9 2221.23     785 2222.11   853.3 2228.02   933.7 2227.97
#Mann= 4 ,-1 , 0
       0      .1       0   216.4    .045       0   268.8      .1       0
  297.91     .05       0
Bank Sta=216.4,268.8
XS Rating Curve= 0 ,0
Exp/Cntr=0.3,0.1

Type RM Length L Ch R = 1 ,43674   ,750.4,746.5,742
XS GIS Cut Line= 2
2246365.65252048376225.0576518182245594.81908838377169.501957148
#Sta/Elev= 30
       0 2326.84    32.9 2324.02    53.9 2323.84    72.6 2321.75    93.6 2314.77
     116  2303.4   133.6 2290.81   147.2 2276.44   156.5 2262.24   164.7 2251.72
   172.9 2239.41   186.8 2213.72   189.2 2211.33   192.2 2210.33   226.5 2208.65
   252.9 2212.68   261.5  2213.2     284 2211.01   312.8 2214.61   406.5 2213.39
     427 2215.06   517.5  2214.4   642.1 2216.98   717.3 2215.92     819 2216.59
  1173.2 2214.98  1181.7 2214.06  1192.1 2216.52  1202.4 2221.77  1219.1 2222.21
#Mann= 7 ,-1 , 0
       0      .1       0    3.15      .1       0   186.8    .045       0
   252.9      .1       0  317.95     .05       0 1143.47    .055       0
 1170.56     .06       0
#XS Ineff= 2 , 0
                          312.17         2222.51
Permanent Ineff=
       F       F
Bank Sta=186.8,252.9
XS Rating Curve= 0 ,0
Exp/Cntr=0.3,0.1

Type RM Length L Ch R = 1 ,42927   ,823,827.2,834.3
XS GIS Cut Line= 3
2245782.31936955375683.3910842242245475.02766131 376226.79386881
2245174.68049297376732.002175972
#Sta/Elev= 30
       0 2256.74    10.7 2251.78    24.5 2249.76    68.4 2233.24    88.5  2227.9
   103.6  2225.7   265.7 2219.07   299.6 2215.87   391.1 2212.22   405.5 2210.85
   416.4 2210.77   426.2 2208.99   453.7 2207.43   461.7 2205.57   484.3 2205.51
   512.8  2204.1   537.9 2207.44   546.2 2210.05   552.1 2210.71   610.2 2208.52
   690.3 2210.81     723 2210.15   875.9 2211.16   925.3 2210.23  1139.7 2212.91
  1161.9 2212.67  1170.4 2211.36  1182.3 2214.05    1191 2217.07    1212 2217.56
#Mann= 5 ,-1 , 0
       0      .1       0  111.58     .05       0   453.7    .045       0
   537.9     .05       0 1099.54     .06       0
#XS Ineff= 2 , 0
                          553.03          2214.1
Permanent Ineff=
       F       F
Bank Sta=453.7,537.9
XS Rating Curve= 0 ,0
Exp/Cntr=0.3,0.1

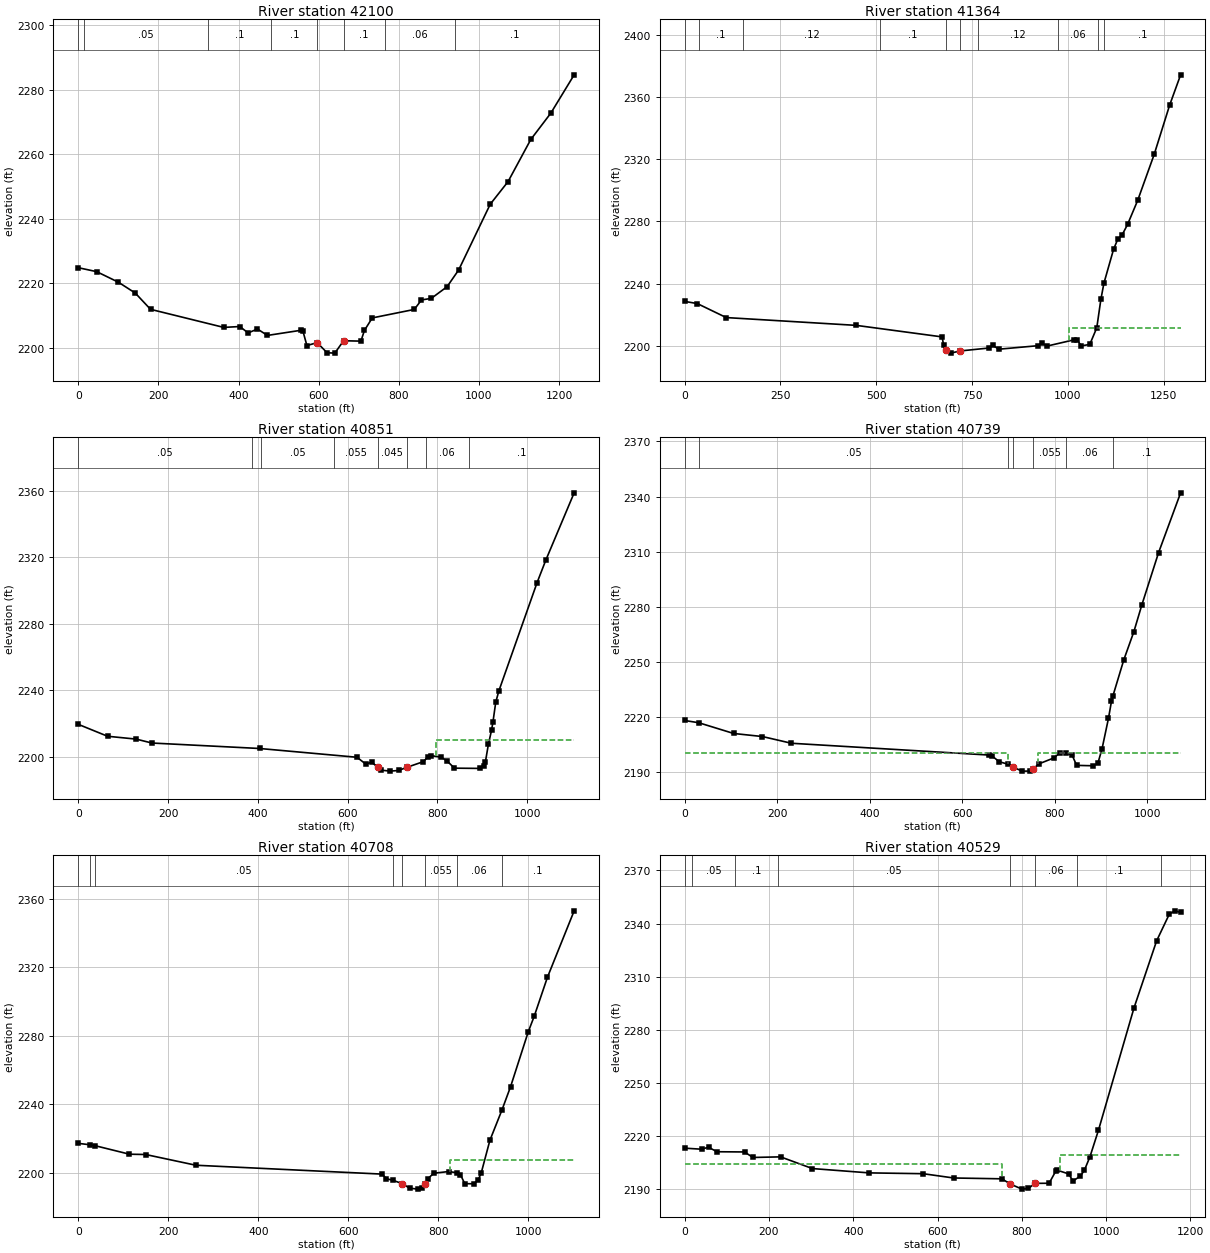
Type RM Length L Ch R = 1 ,42100   ,715.9,735.6,750.5
XS GIS Cut Line= 4
2245275.37484539375466.3770825562244841.34717014375747.627176225
2244549.68043064376072.2797421372244360.44426055376284.085420892
#Sta/Elev= 30
       0 2224.88    46.1 2223.65   100.4 2220.37   142.4 2217.01   180.4 2211.97
   363.1 2206.36   403.4 2206.63   423.9 2204.64   447.3 2205.86   472.2 2203.87
   556.5 2205.48   560.9 2205.15   570.7 2200.72   596.4 2201.64   620.9  2198.5
   640.3 2198.38   662.3 2202.22   705.5  2202.1   714.2 2205.42   733.8  2209.3
   838.7 2211.93   856.6 2214.88   881.1 2215.36   920.4 2218.97   949.4 2224.17
  1028.2 2244.57  1072.6 2251.57  1129.4 2264.65  1179.4 2272.82  1237.6  2284.7
#Mann= 8 ,-1 , 0
       0      .1       0   15.61     .05       0  322.72      .1       0
  482.21      .1       0   596.4    .045       0   662.3      .1       0
  764.56     .06       0   940.6      .1       0
Bank Sta=596.4,662.3
XS Rating Curve= 0 ,0
Exp/Cntr=0.3,0.1

Type RM Length L Ch R = 1 ,41364   ,501.7,512.9,524.8
XS GIS Cut Line= 4
2245313.56932281374857.0019889772244624.33316848375202.488174647
2244414.26370671375308.3908499782244155.58312172375435.127145067
#Sta/Elev= 30
       0 2228.55    32.9 2227.15   108.6 2218.14     448 2213.12   671.8 2205.71
   675.5  2200.8   680.7  2197.2   693.9 2195.27   719.6 2196.68   793.3 2198.54
     804 2200.24     820  2197.8   922.6 2200.06   932.3 2201.91   944.5 2199.74
    1017 2203.88  1024.3 2203.74    1035 2199.94  1057.2 2200.86  1075.5 2211.56
  1086.2 2229.87  1094.1 2240.22  1119.3 2262.06  1130.3 2268.59  1141.3 2271.16
  1155.9 2278.08  1182.2  2293.5  1225.3 2323.09  1265.6 2354.76  1294.3  2374.3
#Mann= 10 ,-1 , 0
       0     .12       0   37.84      .1       0  151.99     .12       0
  510.81      .1       0   680.7    .045       0   719.6      .1       0
   766.5     .12       0  974.83     .06       0 1078.75      .1       0
 1095.52      .1       0
#XS Ineff= 2 , 0
                         1003.06         2211.24
Permanent Ineff=
       F       F
Bank Sta=680.7,719.6
XS Rating Curve= 0 ,0
Exp/Cntr=0.3,0.1

Type RM Length L Ch R = 1 ,40851   ,110.9,112,114.5
XS GIS Cut Line= 2
 2245214.6108593374652.1408501422244112.18032138374721.585593149
#Sta/Elev= 30
       0  2219.7    65.4 2212.53     129 2210.82   164.1 2208.47   403.8 2205.19
     621 2199.92   640.7 2195.76   653.9 2197.06   667.1 2193.79   673.6 2192.21
   694.9  2191.6   713.5 2191.99   732.1 2193.89   768.9  2197.3   778.8 2200.21
   785.4 2200.93   808.4 2199.96   821.5 2197.69     838 2193.38   893.8 2193.23
   903.7 2194.72     907 2197.28   913.6 2207.71   920.7 2216.27   923.8 2221.18
     930 2233.04     937 2239.83    1022 2304.74  1041.3 2318.13  1104.6 2358.65
#Mann= 8 ,-1 , 0
       0     .05       0  387.46     .12       0  406.88     .05       0
  569.92    .055       0   667.1    .045       0   732.1      .1       0
   774.1     .06       0  869.33      .1       0
#XS Ineff= 2 , 0
                          797.28         2210.53
Permanent Ineff=
       F       F
Bank Sta=667.1,732.1
XS Rating Curve= 0 ,0
Exp/Cntr=0.5,0.3

Type RM Length L Ch R = 1 ,40739   ,31.8,31.7,32
XS GIS Cut Line= 2
2245251.92738572374565.0383340572244179.70512073374592.816165641
#Sta/Elev= 30
       0 2218.15    30.5 2216.92   105.9 2211.08   168.2 2209.41   230.7 2205.76
   657.3 2199.35   663.9 2199.01   680.3 2195.72   699.4 2194.34   709.8 2192.84
   729.5 2190.59   745.9 2190.61   754.4 2191.92   765.6 2194.49   798.4 2197.77
   811.6 2200.59   825.2 2200.39   837.8 2199.38   847.7 2193.72   883.8  2193.5
   893.6 2194.81   902.7 2202.79   916.6 2219.36   923.1 2228.68   926.3 2231.62
   949.8 2251.22   971.4 2266.42   988.8 2281.11  1024.9 2309.49  1072.6 2342.05
#Mann= 7 ,-1 , 0
       0      .1       0    30.5     .05       0   699.4    .055       0
   709.8    .045       0   754.4    .055       0   825.2     .06       0
   926.3      .1       0
#XS Ineff= 2 , 0
           699.8  2200.4   764.4          2200.4
Permanent Ineff=
       F       F
Bank Sta=709.8,754.4
XS Rating Curve= 0 ,0
Exp/Cntr=0.5,0.3

Type RM Length L Ch R = 1 ,40708   ,177,178.4,180.1
XS GIS Cut Line= 2
2245263.03858396374534.4829489742244161.64971064 374560.87167573
#Sta/Elev= 30
       0  2217.1    25.2  2216.3    38.3 2215.68   113.8 2210.76   149.9 2210.57
   261.4 2204.31   674.9 2199.13   684.8 2196.41   699.3  2195.5     719 2193.62
   736.3 2190.92   754.3 2190.35   763.6 2190.99   769.9 2193.58   776.7 2196.44
   789.8 2199.64   822.6 2200.62   840.5 2199.97   848.9 2198.88   858.7 2193.55
   878.4 2193.47   888.3 2195.61   895.3 2199.84   914.5 2218.85   941.4 2236.64
   960.5 2250.25   999.8 2282.32    1013 2291.38  1042.3 2314.11  1101.7 2352.97
#Mann= 8 ,-1 , 0
       0      .1       0    25.2      .1       0    38.3     .05       0
   699.3    .055       0     719    .045       0   769.9    .055       0
   840.5     .06       0   941.4      .1       0
#XS Ineff= 2 , 0
                          826.25         2207.12
Permanent Ineff=
       F       F
Bank Sta=719,769.9
XS Rating Curve= 0 ,0
Exp/Cntr=0.5,0.3

Type RM Length L Ch R = 1 ,40529   ,428.7,409.4,390.6
XS GIS Cut Line= 4
2245323.98596863374414.2938848882244638.22192022374377.835296392
2244435.09699839374370.8910845672244155.58312172374435.127176553
#Sta/Elev= 30
       0 2213.16    40.2 2212.57    56.6 2213.72    76.4 2211.14   142.1 2211.02
   161.8 2207.91   227.5 2208.25   303.1 2201.64   437.8  2199.2   565.9 2198.74
   638.2 2196.32   752.8 2195.85   772.8 2192.89   800.4 2190.03   815.5 2190.45
   831.7 2193.28   864.7 2193.35   881.1 2200.41   884.4 2200.69   911.2 2198.62
   921.3 2194.61   938.8 2197.37   948.2 2200.56   961.7 2208.33   981.9 2223.33
  1066.1  2292.3  1119.9 2330.26  1150.2 2345.43  1163.7 2347.18  1176.8 2346.27
#Mann= 8 ,-1 , 0
       0      .1       0   18.38     .05       0  120.02      .1       0
  221.66     .05       0   772.8    .045       0   831.7     .06       0
  931.48      .1       0 1130.56      .1       0
#XS Ineff= 2 , 0
          753.14 2203.97  890.32          2209.4
Permanent Ineff=
       F       F
Bank Sta=772.8,831.7
XS Rating Curve= 0 ,0
Exp/Cntr=0.3,0.1

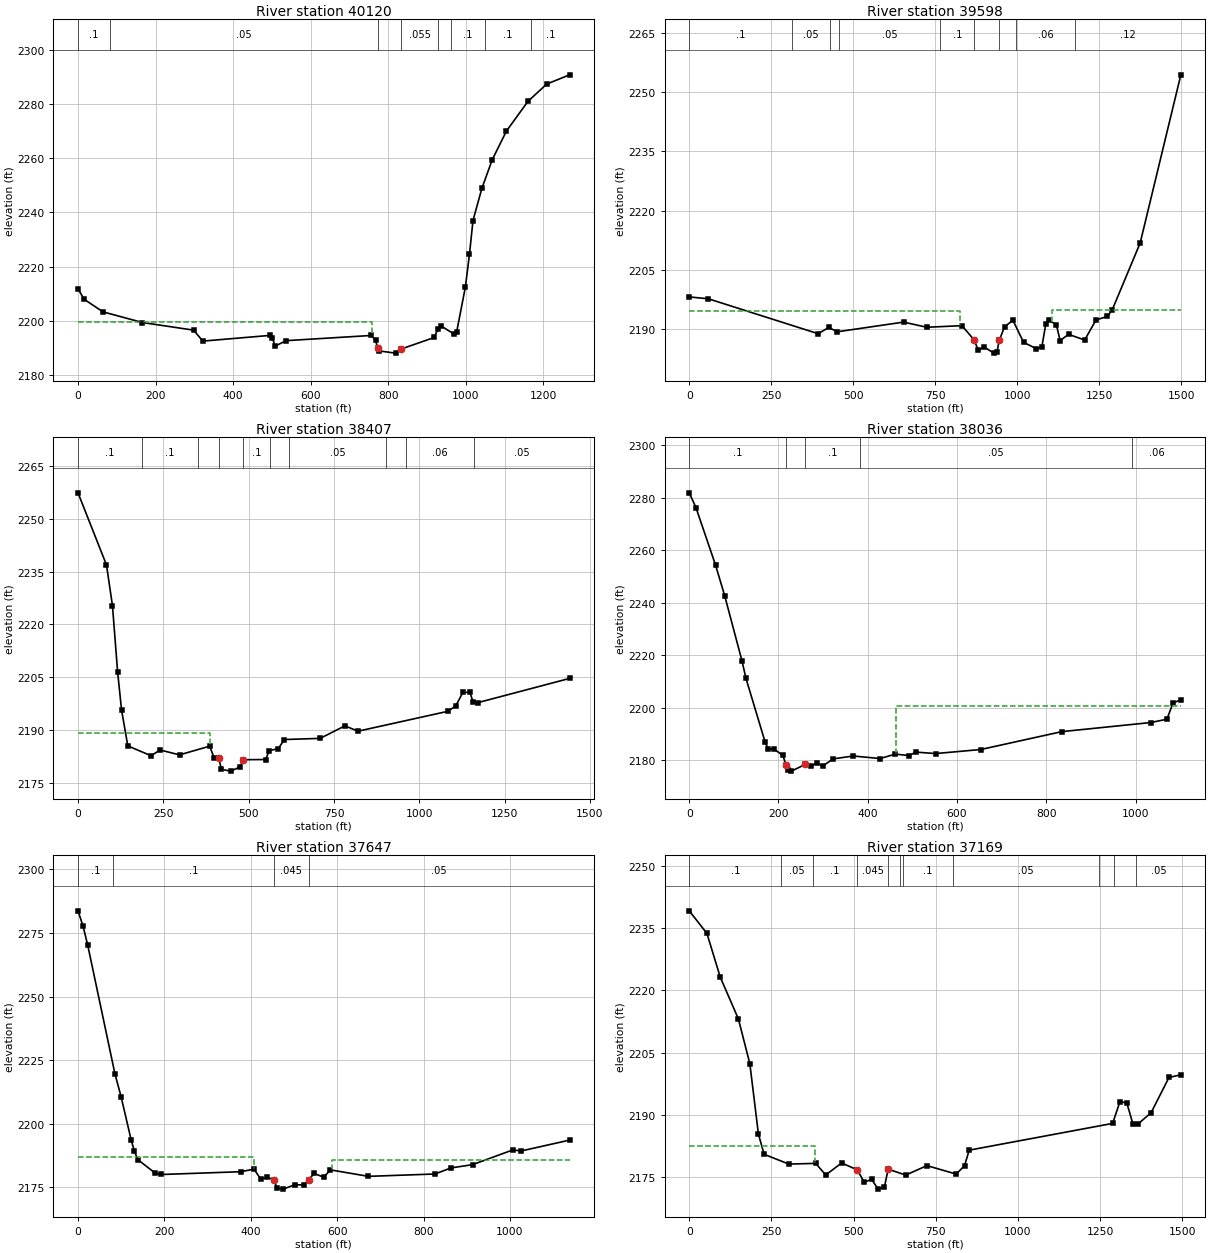
Type RM Length L Ch R = 1 ,40120   ,522.2,521.5,516.2
XS GIS Cut Line= 3
2245103.49986105373525.404914647 2244374.3330123 374023.66868189
2244096.55535264374289.293806806
#Sta/Elev= 30
       0 2211.83      16 2207.98    64.4 2203.37   165.9 2199.44   298.2 2196.62
   321.7 2192.58     494 2194.67   500.8  2193.9   508.2 2190.72   536.4 2192.75
   756.1 2194.66   767.1  2192.9   772.6 2190.04   775.4 2188.98   818.7 2188.15
     834  2189.7   918.5 2193.92   927.6 2196.97   937.1 2198.07   969.4 2195.22
   976.3 2195.95   998.8 2212.52  1009.3 2224.54  1018.4 2237.02  1041.3  2248.9
  1068.3 2259.54  1104.6 2270.01  1160.2 2280.99  1208.4 2287.34  1267.5 2290.76
#Mann= 8 ,-1 , 0
       0      .1       0    83.1     .05       0   772.6    .045       0
     834    .055       0   928.1     .06       0  962.98      .1       0
 1048.63      .1       0 1169.16      .1       0
#XS Ineff= 2 , 0
          758.23 2199.45
Permanent Ineff=
       F       F
Bank Sta=772.6,834
XS Rating Curve= 0 ,0
Exp/Cntr=0.3,0.1

Type RM Length L Ch R = 1 ,39598   ,1148.3,1191.6,1161.1
XS GIS Cut Line= 3
2244740.65248963373018.4603904782243931.62490822373764.988096893
2243633.01362881374028.877004817
#Sta/Elev= 30
       0 2198.13    58.5 2197.65   392.8 2188.82   426.1  2190.4   450.9 2189.29
   653.7 2191.75   724.5 2190.44   831.7 2190.85   868.8 2187.24   881.4 2184.63
     899 2185.45   929.2 2183.89   938.5 2184.19   945.4 2187.09   961.6 2190.55
   987.2 2192.22  1019.6 2186.63  1058.3 2185.02  1075.4 2185.45  1087.4 2191.26
    1097 2192.22  1119.6  2191.1  1131.2 2187.07  1156.8 2188.65    1206 2187.21
  1240.6 2192.29  1275.3 2193.19  1290.2 2194.89  1375.3  2211.8  1499.3 2254.39
#Mann= 9 ,-1 , 0
       0      .1       0  313.68     .05       0   430.3      .1       0
  456.49     .05       0  766.31      .1       0   868.8    .045       0
   945.4      .1       0  997.73     .06       0 1176.57     .12       0
#XS Ineff= 2 , 0
          826.71 2194.57  1105.6         2194.87
Permanent Ineff=
       F       F
Bank Sta=868.8,945.4
XS Rating Curve= 0 ,0
Exp/Cntr=0.3,0.1

Type RM Length L Ch R = 1 ,38407   ,368.8,370.5,370
XS GIS Cut Line= 3
2244039.26380055372633.0438384712243645.16649164372976.793807149
2242959.40244322373586.168900728
#Sta/Elev= 30
       0 2257.37    83.5 2236.86     101 2225.28     116 2206.57   127.6 2195.65
   145.9 2185.45   213.7 2182.66   240.8 2184.27   297.4 2182.89   385.8 2185.36
     399 2181.99   412.1 2181.98   420.4 2178.78   446.9 2178.27   475.3 2179.47
   483.4 2181.51   549.9 2181.57   560.4 2184.13   586.8 2184.63   604.3 2187.25
   709.6 2187.58   782.1 2191.14   820.4 2189.62  1082.7 2195.25  1106.3 2196.74
  1127.8 2200.66  1148.1 2200.65  1157.3 2198.04  1172.3 2197.76  1440.3 2204.62
#Mann= 10 ,-1 , 0
       0      .1       0  187.19      .1       0   352.3      .1       0
   412.1    .045       0   483.4      .1       0  563.59      .1       0
  618.75     .05       0  902.43      .1       0  959.92     .06       0
 1160.04     .05       0
#XS Ineff= 2 , 0
          386.64 2189.02
Permanent Ineff=
       F       F
Bank Sta=412.1,483.4
XS Rating Curve= 0 ,0
Exp/Cntr=0.3,0.1

Type RM Length L Ch R = 1 ,38036   ,388.5,389.6,383.7
XS GIS Cut Line= 2
2243683.36096905372436.863128483 2242922.9441828373233.738175139
#Sta/Elev= 30
       0 2281.81    15.1 2276.16    59.1 2254.23    79.4 2242.65   118.1  2217.9
   127.1 2211.19   169.9 2186.99   176.8 2184.27   190.8 2184.12     210 2181.84
   216.3 2178.36   220.9 2176.13     229 2175.86   260.4 2178.46   272.2 2177.74
     286 2178.87   299.8 2177.84   322.1 2180.51   367.5 2181.62   427.5 2180.65
   461.8 2182.34   492.4 2181.79   508.1  2183.1   552.1 2182.55   653.2 2184.09
   834.6 2190.89  1034.1 2194.36  1070.3 2195.62  1084.2 2201.88  1101.5 2202.96
#Mann= 5 ,-1 , 0
       0      .1       0   216.3    .045       0   260.4      .1       0
  381.73     .05       0  993.06     .06       0
#XS Ineff= 2 , 0
                          463.84         2200.63
Permanent Ineff=
       F       F
Bank Sta=216.3,260.4
XS Rating Curve= 0 ,0
Exp/Cntr=0.3,0.1

Type RM Length L Ch R = 1 ,37647   ,467.1,478,481.2
XS GIS Cut Line= 2
2243440.30535281372034.0853907322242834.40269323372997.627098814
#Sta/Elev= 30
       0 2283.73    11.6 2277.75    22.5 2270.25    85.4 2219.77     100 2210.53
   123.2 2193.61   130.6 2189.26   138.7 2185.93   179.3 2180.57     193 2180.11
   376.5  2181.2   407.4  2182.2   423.3  2178.3   437.6 2179.02   454.2 2177.98
   460.4 2174.89   475.2 2174.36   501.8 2176.09   523.2 2175.99     534 2178.06
     547 2180.53   568.9 2179.02   584.4 2181.93   672.4 2179.38   826.5 2180.31
   863.4 2182.69   913.4 2183.97  1006.9 2189.78  1026.2 2189.36  1138.2 2193.62
#Mann= 4 ,-1 , 0
       0      .1       0   80.43      .1       0   454.2    .045       0
     534     .05       0
#XS Ineff= 2 , 0
          406.79 2186.91  588.12         2185.85
Permanent Ineff=
       F       F
Bank Sta=454.2,534
XS Rating Curve= 0 ,0
Exp/Cntr=0.3,0.1

Type RM Length L Ch R = 1 ,37169   ,1020.8,1004.3,989
XS GIS Cut Line= 4
2243160.79147613371763.252270982 2242567.0413513372443.807668388
2242297.94412047372764.9881283942242181.62479931372893.460312396
#Sta/Elev= 30
       0 2239.18    53.8 2233.75    94.3 2223.22   149.6 2213.14   184.4 2202.36
   210.5  2185.4   227.9 2180.56   302.9 2178.21   384.7 2178.38   415.1 2175.59
   463.6 2178.47   510.9 2176.84   532.7 2173.81   554.5 2174.55   574.9 2172.18
   593.7 2172.64   605.1 2176.99   658.6 2175.56   723.1 2177.84   812.1  2175.8
   837.5 2177.82   851.6 2181.56    1288    2188  1310.3 2193.27  1331.3  2192.9
  1349.9 2187.81  1366.1 2187.94  1404.8 2190.54  1459.5 2199.07  1495.5  2199.7
#Mann= 11 ,-1 , 0
       0      .1       0   280.5     .05       0  375.61      .1       0
   510.9    .045       0   605.1      .1       0  639.77    .025       0
  649.55      .1       0   801.1     .05       0 1247.63    .055       0
  1291.6     .06       0 1358.77     .05       0
#XS Ineff= 2 , 0
          382.12 2182.66
Permanent Ineff=
       F       F
Bank Sta=510.9,605.1
XS Rating Curve= 0 ,0
Exp/Cntr=0.3,0.1

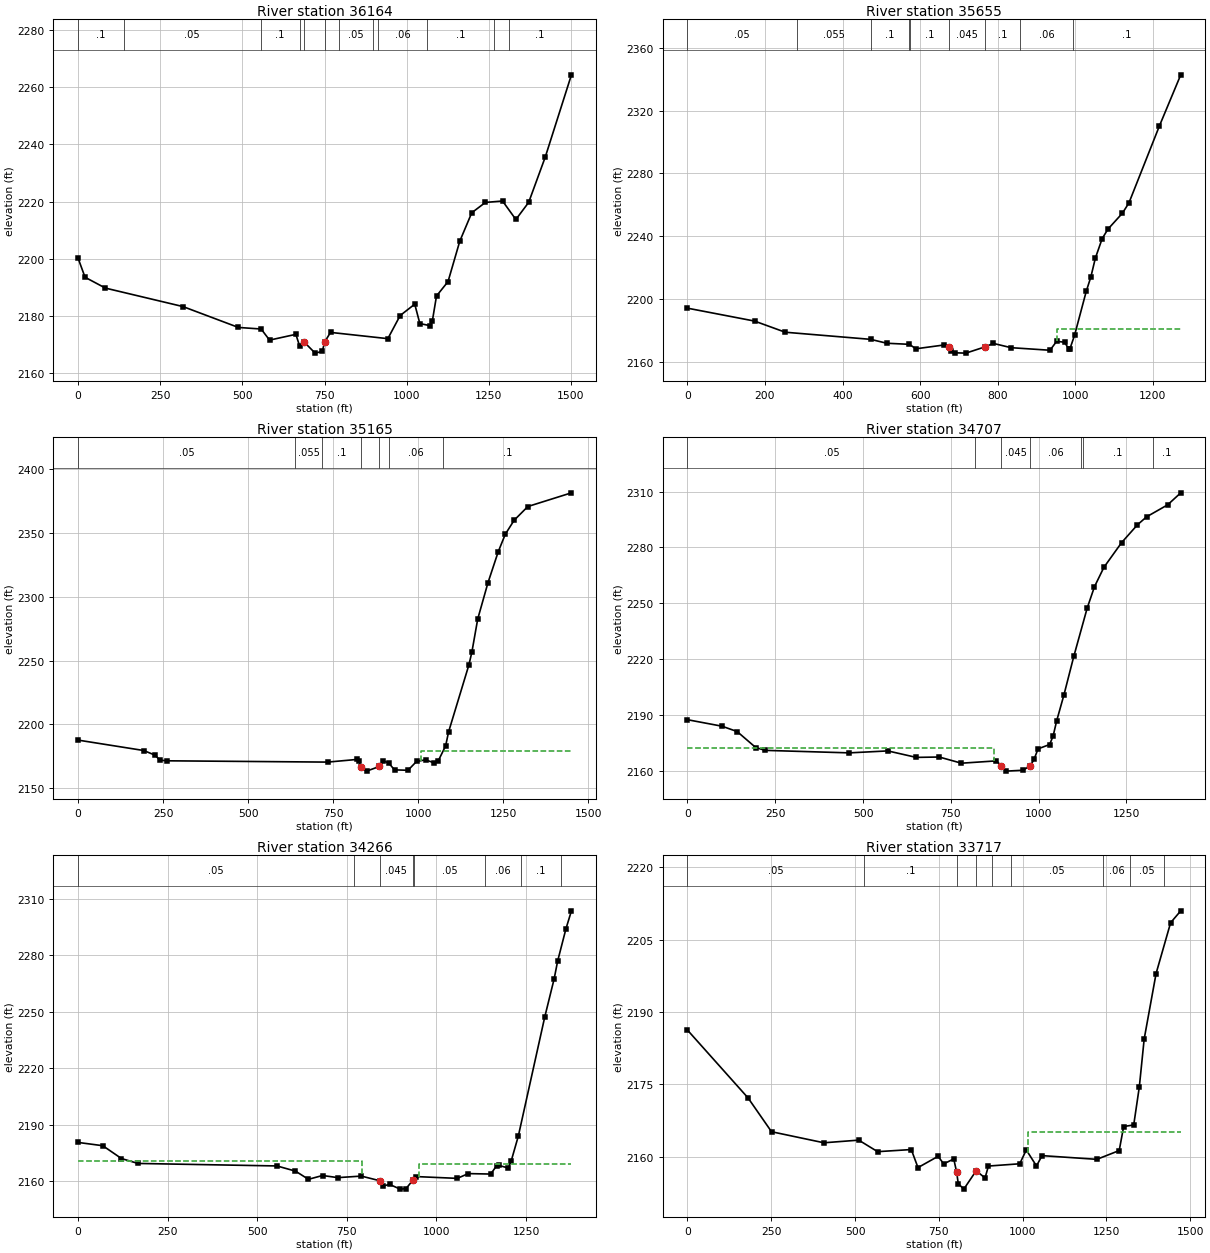
Type RM Length L Ch R = 1 ,36164   ,503.7,509.5,525.8
XS GIS Cut Line= 3
 2242216.3471708371377.8353908962241773.63873863372291.029758722
2241511.48604771372700.752036393
#Sta/Elev= 30
       0 2200.23    21.2 2193.57    83.2 2189.78   318.9 2183.33   487.9 2176.02
   557.1 2175.47   582.7 2171.59   662.7 2173.61   673.9 2169.62   687.2 2171.01
   721.3 2167.04   743.1 2167.64   750.4 2170.95   768.2 2174.29   942.6  2172.1
   980.1 2180.19  1024.5 2184.16    1040 2177.39  1071.3 2176.63    1078 2178.25
  1090.7 2187.03  1125.8 2192.06  1161.5 2206.17    1198 2216.13  1239.5 2219.74
  1291.7 2220.23  1332.2 2213.77  1371.2 2219.76  1421.8 2235.65  1501.3 2264.36
#Mann= 12 ,-1 , 0
       0      .1       0  139.77     .05       0  555.27      .1       0
   673.9      .1       0   687.2    .045       0   750.4      .1       0
  792.53     .05       0  897.45      .1       0  911.16     .06       0
 1062.62      .1       0 1265.74      .1       0 1311.06      .1       0
Bank Sta=687.2,750.4
XS Rating Curve= 0 ,0
Exp/Cntr=0.3,0.1

Type RM Length L Ch R = 1 ,35655   ,484.5,489.3,483.9
XS GIS Cut Line= 2
2241869.12476814371270.1964985582241087.87469022372273.668901056
#Sta/Elev= 30
       0 2194.25   173.1 2186.03   252.2 2178.93   472.5 2174.39   513.9 2171.91
   572.3 2171.22   588.9 2168.38   661.2  2170.8   675.2 2169.49   680.4 2167.01
   688.7 2165.83   717.8 2165.62   767.7 2169.65   788.5 2171.82   834.2 2169.09
   934.7 2167.45   951.7 2173.12   972.1 2172.58   983.7 2168.01   986.2  2168.5
   997.9 2176.92  1028.2 2205.05  1039.9 2214.05  1051.6 2226.11  1069.2 2238.57
  1084.3 2244.64  1121.1 2254.65  1138.1 2261.24  1216.7 2310.28  1271.7 2342.82
#Mann= 9 ,-1 , 0
       0     .05       0  282.54    .055       0  472.37      .1       0
  570.94      .1       0  572.57      .1       0   675.2    .045       0
   767.7      .1       0  858.58     .06       0  994.99      .1       0
#XS Ineff= 2 , 0
                          953.93          2180.9
Permanent Ineff=
       F       F
Bank Sta=675.2,767.7
XS Rating Curve= 0 ,0
Exp/Cntr=0.3,0.1

Type RM Length L Ch R = 1 ,35165   ,447.5,458.4,483.4
XS GIS Cut Line= 3
2241686.83313797371119.1548058992241308.36079781371400.404899567
2240558.36098547372030.613284811
#Sta/Elev= 30
       0 2187.74     193 2179.58   227.4 2175.82   239.7 2172.11   260.1 2171.51
   734.1 2170.49   819.8 2172.56     826 2171.46  832.352166.374   848.6 2163.41
   886.5 2167.08   898.2 2171.48   914.1 2169.65   930.8  2164.4   970.4 2164.07
   995.5 2170.98    1022 2172.27    1047 2169.93  1059.8 2171.66  1081.2 2183.25
  1089.8 2194.16  1149.7 2246.82  1158.4 2256.84  1175.5 2282.66  1205.6 2311.09
  1235.8 2335.42  1256.6 2349.16  1282.6 2360.14  1322.9 2370.92  1451.2 2381.67
#Mann= 7 ,-1 , 0
       0     .05       0     638    .055       0  718.21      .1       0
  832.35    .045       0   886.5      .1       0  915.17     .06       0
 1074.06      .1       0
#XS Ineff= 2 , 0
                         1008.72         2179.52
Permanent Ineff=
       F       F
Bank Sta=832.35,886.5
XS Rating Curve= 0 ,0
Exp/Cntr=0.3,0.1

Type RM Length L Ch R = 1 ,34707   ,442.5,441.4,458.7
XS GIS Cut Line= 3
2241683.36103205371110.4743770662240829.19410522371252.835312814
2240303.15250638371369.154962063
#Sta/Elev= 30
       0 2187.44    98.4 2183.95   141.6 2181.08   194.8 2172.45   222.1 2170.96
   460.9 2169.62   570.7 2170.67   651.6 2167.19     717 2167.39   780.2 2164.07
     880 2165.32   893.6 2162.68     907 2159.81   954.4 2160.27   976.4 2162.58
   987.7 2166.48   998.4 2171.77  1031.4 2174.11  1041.4 2178.73  1051.5  2186.9
  1071.7 2200.48  1100.2 2221.48  1138.3  2247.4    1159 2258.87  1185.9  2269.3
  1236.3 2282.58  1281.4 2292.15  1307.3 2296.42  1367.4 2302.88  1404.7 2309.33
#Mann= 7 ,-1 , 0
       0     .05       0  820.12      .1       0   893.6    .045       0
   976.4     .06       0 1121.55      .1       0 1125.48      .1       0
 1324.45      .1       0
#XS Ineff= 2 , 0
           873.8 2172.34
Permanent Ineff=
       F       F
Bank Sta=893.6,976.4
XS Rating Curve= 0 ,0
Exp/Cntr=0.3,0.1

Type RM Length L Ch R = 1 ,34266   ,547.7,548.8,540.8
XS GIS Cut Line= 2
2241733.70804422370829.2242833972240356.97195256 370827.48806639
#Sta/Elev= 30
       0 2180.59    68.9 2178.85   121.1 2172.04   167.1 2169.44     555 2168.11
   606.7 2165.36   642.8 2161.02   682.2 2163.04   724.8 2161.91   790.4 2162.73
   842.9 2160.21   849.5 2157.37   869.2 2158.33   898.7 2155.81   915.1 2156.07
   933.5  2160.4   943.3 2162.47    1058 2161.52    1089 2164.05  1151.3 2163.81
  1167.7 2168.11  1174.3 2168.39  1200.5 2167.02  1208.8 2170.87  1228.5 2183.97
  1302.2 2247.13  1328.5 2267.44  1338.3  2276.9  1361.3  2293.9  1376.7  2303.5
#Mann= 8 ,-1 , 0
       0     .05       0  771.32      .1       0   842.9    .045       0
   933.5      .1       0  937.06     .05       0 1135.33     .06       0
 1235.98      .1       0  1347.5      .1       0
#XS Ineff= 2 , 0
          791.51 2170.98  952.35          2169.4
Permanent Ineff=
       F       F
Bank Sta=842.9,933.5
XS Rating Curve= 0 ,0
Exp/Cntr=0.3,0.1

Type RM Length L Ch R = 1 ,33717   ,622.7,626.3,623.5
XS GIS Cut Line= 2
2241725.02761538370139.988129064 2240277.1108918370403.877036974
#Sta/Elev= 30
       0 2186.27     181  2172.2     251  2165.2   407.3 2162.91   511.2 2163.46
   567.5 2161.07   667.9 2161.51   687.9 2157.77   747.9 2160.11   764.6 2158.54
   794.6 2159.56     8032156.899   808.1 2154.45   824.6 2153.31   861.5 2157.11
     888 2155.62     898 2158.09   991.4 2158.56    1011 2161.43  1041.4 2158.11
  1058.1 2160.25  1221.5 2159.48  1288.2  2161.3  1301.5 2166.28  1331.5  2166.6
  1348.2 2174.48  1362.7 2184.41  1398.2 2197.97  1441.6  2208.5  1471.8 2210.96
#Mann= 9 ,-1 , 0
       0     .05       0  527.98      .1       0     803    .045       0
   861.5      .1       0  908.39      .1       0  966.02     .05       0
 1239.12     .06       0 1321.83     .05       0 1421.18      .1       0
#XS Ineff= 2 , 0
                         1016.86         2165.13
Permanent Ineff=
       F       F
Bank Sta=803,861.5
XS Rating Curve= 0 ,0
Exp/Cntr=0.3,0.1

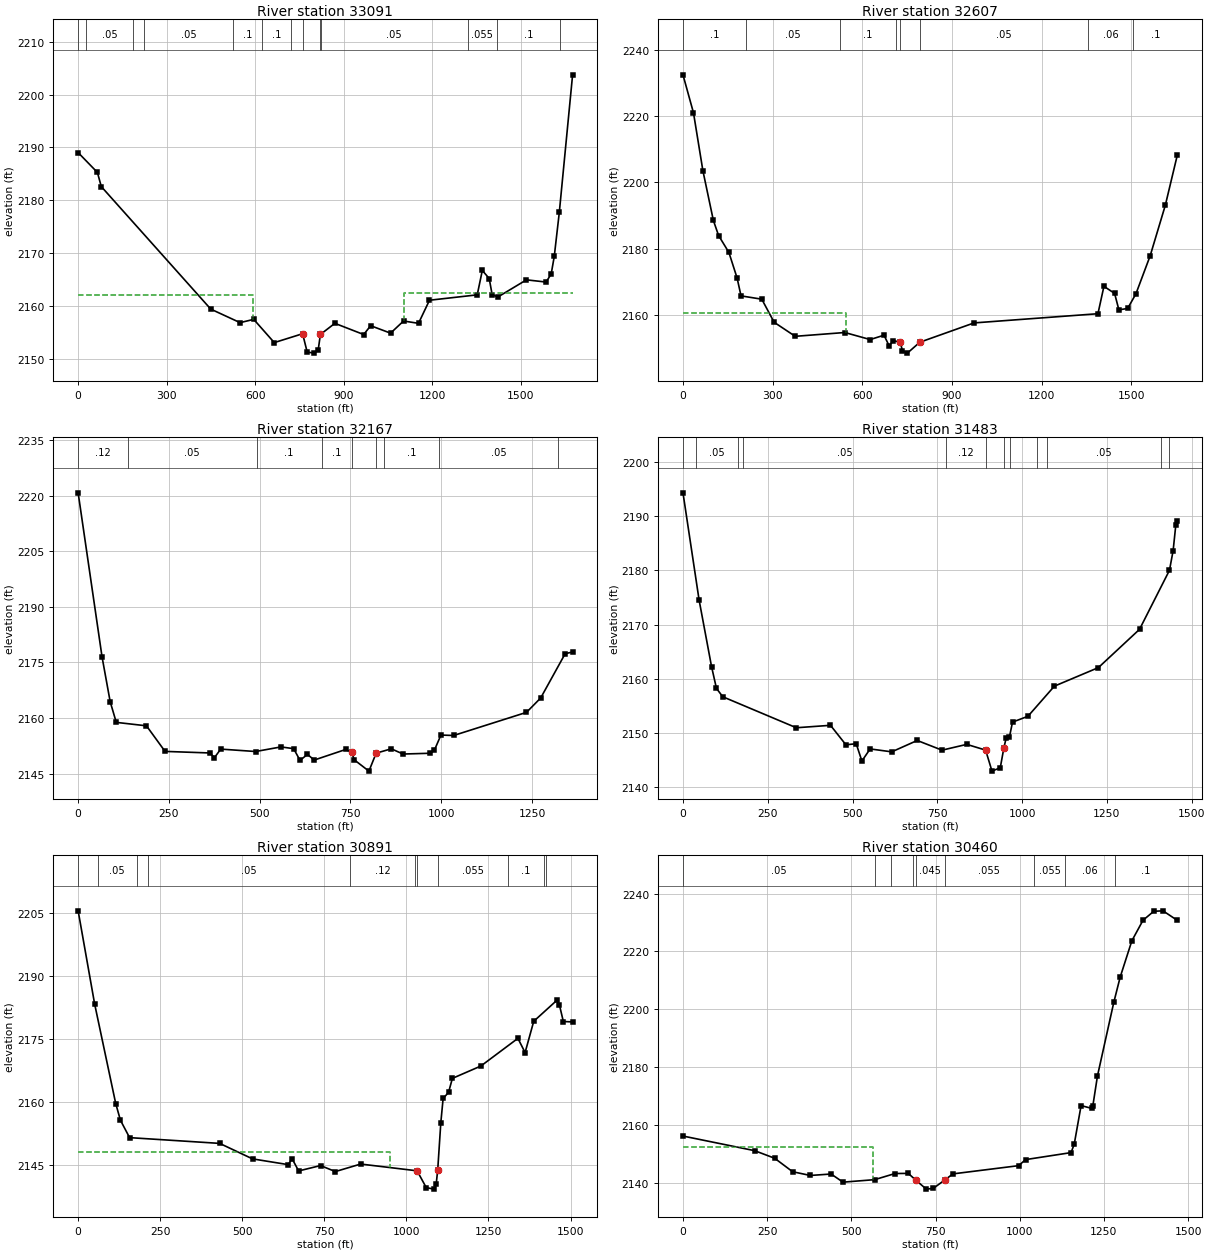
Type RM Length L Ch R = 1 ,33091   ,494.6,483.9,468.2
XS GIS Cut Line= 4
2241631.27747481369577.4882698062240752.80547847369700.752130896
 2240275.3746748369818.8076690582239981.97204639369867.418792307
#Sta/Elev= 30
       0 2189.01    65.3 2185.26    78.5 2182.58   449.6 2159.39     549 2156.83
   595.3 2157.45   664.9 2153.05     761 2154.73   776.5 2151.26   800.8 2151.06
     814 2151.73   821.3 2154.59   870.3  2156.7     968 2154.58   991.7 2156.25
  1059.2 2154.84  1103.2 2157.14  1153.9  2156.7  1191.1 2161.07    1353 2162.09
  1370.2 2166.71  1393.6 2165.18  1403.6 2162.11  1423.5  2161.7  1519.9 2164.93
  1586.5 2164.51  1603.7 2166.04  1614.1 2169.35  1631.2 2177.68  1676.3 2203.73
#Mann= 13 ,-1 , 0
       0      .1       0   26.02     .05       0  186.51    .055       0
  222.83     .05       0  524.63      .1       0  623.97      .1       0
  723.32      .1       0     761    .045       0   821.3      .1       0
  822.67     .05       0 1320.76    .055       0 1420.28      .1       0
 1632.49      .1       0
#XS Ineff= 2 , 0
          591.85 2162.14 1104.24         2162.36
Permanent Ineff=
       F       F
Bank Sta=761,821.3
XS Rating Curve= 0 ,0
Exp/Cntr=0.3,0.1

Type RM Length L Ch R = 1 ,32607   ,442.4,440,432.5
XS GIS Cut Line= 4
2241370.86100088368829.2243463992240546.20812264369339.640976474
2240171.20821647369598.3215614712239981.97204639369726.793745473
#Sta/Elev= 30
       0 2232.53    35.2 2221.03    66.7 2203.52   101.6 2188.55   119.1 2183.97
   153.6 2178.86   181.1 2171.11   194.2 2165.73   263.6 2164.73     305 2157.75
   375.5 2153.51   541.4 2154.66   626.3 2152.53   672.6 2153.85   689.7 2150.61
   703.5  2152.2   727.1 2151.75     734 2149.16   750.7 2148.43   792.2 2151.72
   973.7 2157.56  1388.2 2160.34  1408.2 2168.62  1443.9 2166.48  1458.2 2161.52
  1487.5 2161.92  1515.3 2166.36  1562.9 2177.85  1613.6 2193.12  1654.1 2208.43
#Mann= 8 ,-1 , 0
       0      .1       0  210.06     .05       0  526.84      .1       0
   711.1      .1       0   727.1    .045       0   792.2     .05       0
 1354.94     .06       0 1506.15      .1       0
#XS Ineff= 2 , 0
          544.99 2160.48
Permanent Ineff=
       F       F
Bank Sta=727.1,792.2
XS Rating Curve= 0 ,0
Exp/Cntr=0.3,0.1

Type RM Length L Ch R = 1 ,32167   ,678.5,683.7,680.8
XS GIS Cut Line= 2
2241028.84692113368398.6687770632240004.54155505369296.238176137
#Sta/Elev= 30
       0 2220.75    65.8 2176.53    88.2 2164.44     105 2158.84   188.2 2157.91
   239.4 2151.01   362.4 2150.59   375.5 2149.34   392.8 2151.63   488.9 2150.98
   558.7 2152.22   593.6 2151.75   611.1 2148.59   631.6  2150.2   650.3 2148.68
   736.9 2151.53   753.2 2150.76     761  2148.7   800.9 2145.69   820.8 2150.53
   862.5 2151.71     895  2150.3   969.4 2150.51     981 2151.29   999.3 2155.42
  1034.2  2155.3  1234.9 2161.54    1274 2165.42  1341.4 2177.36  1361.9 2177.82
#Mann= 9 ,-1 , 0
       0     .12       0  137.07     .05       0  491.31      .1       0
   670.7      .1       0   753.2    .045       0   820.8      .1       0
  842.73      .1       0   995.1     .05       0 1322.57    .055       0
Bank Sta=753.2,820.8
XS Rating Curve= 0 ,0
Exp/Cntr=0.3,0.1

Type RM Length L Ch R = 1 ,31483   ,583.1,591.6,592
XS GIS Cut Line= 3
2240657.31912088367881.3076070552239862.18029122368553.182575643
2239547.12190404368826.566551329
#Sta/Elev= 30
       0 2194.32    47.5 2174.54    84.2 2162.25    98.7 2158.21   117.4 2156.66
   334.3 2150.94     435 2151.39   480.5 2147.79   510.8 2147.99   527.6  2144.8
   551.9 2147.03   615.6 2146.49   690.8 2148.59   763.9  2146.8   836.9 2147.87
   892.5 2146.81   911.2 2142.93   935.7 2143.56   946.1 2147.16   952.9 2149.02
   962.4 2149.14   971.8 2151.98  1017.3 2153.06  1095.2 2158.62  1225.1 2162.05
  1346.3 2169.11  1434.6 2180.02  1445.4 2183.64  1453.2 2188.32  1458.1 2189.14
#Mann= 12 ,-1 , 0
       0     .12       0   38.94     .05       0  162.93     .12       0
  176.59     .05       0  776.47     .12       0   892.5    .045       0
   946.1     .12       0  965.78     .05       0 1043.73      .1       0
 1072.72     .05       0 1410.73    .055       0 1432.33     .06       0
Bank Sta=892.5,946.1
XS Rating Curve= 0 ,0
Exp/Cntr=0.3,0.1

Type RM Length L Ch R = 1 ,30891   ,434.4,431.1,429.6
XS GIS Cut Line= 4
2240323.98579806367577.4883328082240014.95820089367851.793886557
2239346.55533822368341.377224982 2239148.6387393368516.724315226
#Sta/Elev= 30
       0  2205.6    50.3  2183.4   114.5 2159.71   128.8 2155.75   156.7  2151.6
   431.1 2150.23   531.3 2146.54     640 2145.17   651.7 2146.59   671.7 2143.67
   738.4 2144.95   783.5 2143.52   860.6 2145.31  1032.6  2143.7  1060.4  2139.7
  1084.4 2139.34  1090.7 2140.52  1095.4 2143.99  1104.8 2155.19  1111.8 2160.93
  1128.3 2162.37    1140 2165.71  1226.8 2168.65  1339.6 2175.24  1361.5 2171.85
  1387.8  2179.3  1457.9 2184.27    1466 2183.22    1478 2179.25  1506.2 2179.15
#Mann= 11 ,-1 , 0
       0     .12       0   60.36     .05       0  177.98     .12       0
  211.47     .05       0   829.4     .12       0 1025.39    .055       0
  1032.6    .045       0  1095.4    .055       0 1308.51      .1       0
 1417.64    .055       0 1426.05     .06       0
#XS Ineff= 2 , 0
          949.86 2148.29
Permanent Ineff=
       F       F
Bank Sta=1032.6,1095.4
XS Rating Curve= 0 ,0
Exp/Cntr=0.3,0.1

Type RM Length L Ch R = 1 ,30460   ,830.6,837,822
XS GIS Cut Line= 3
2239725.02767839367445.5437148062239101.76383306368006.307685137
2238648.63875505368443.807794392
#Sta/Elev= 30
       0 2156.09   212.8 2151.03   272.2 2148.41   325.6 2143.74   378.1 2142.45
   439.9 2142.95   475.2 2140.13   569.3    2141   629.7 2143.12     669 2143.17
   692.4 2140.73   722.6 2137.72   743.6    2138   776.9 2140.84   801.8    2143
   996.5 2145.84  1017.5 2147.94  1152.4 2150.36  1161.8 2153.26  1182.2 2166.64
  1213.8 2165.66    1217 2166.46  1230.9 2176.94  1279.4 2202.41  1298.2 2211.07
    1333 2223.68  1366.1 2230.78    1398 2233.88  1425.4 2234.04  1468.3 2230.71
#Mann= 9 ,-1 , 0
       0     .05       0  570.04      .1       0  616.37     .12       0
  681.96    .055       0   692.4    .045       0   776.9    .055       0
 1041.03    .055       0 1135.78     .06       0 1282.89      .1       0
#XS Ineff= 2 , 0
          564.12 2152.41
Permanent Ineff=
       F       F
Bank Sta=692.4,776.9
XS Rating Curve= 0 ,0
Exp/Cntr=0.3,0.1