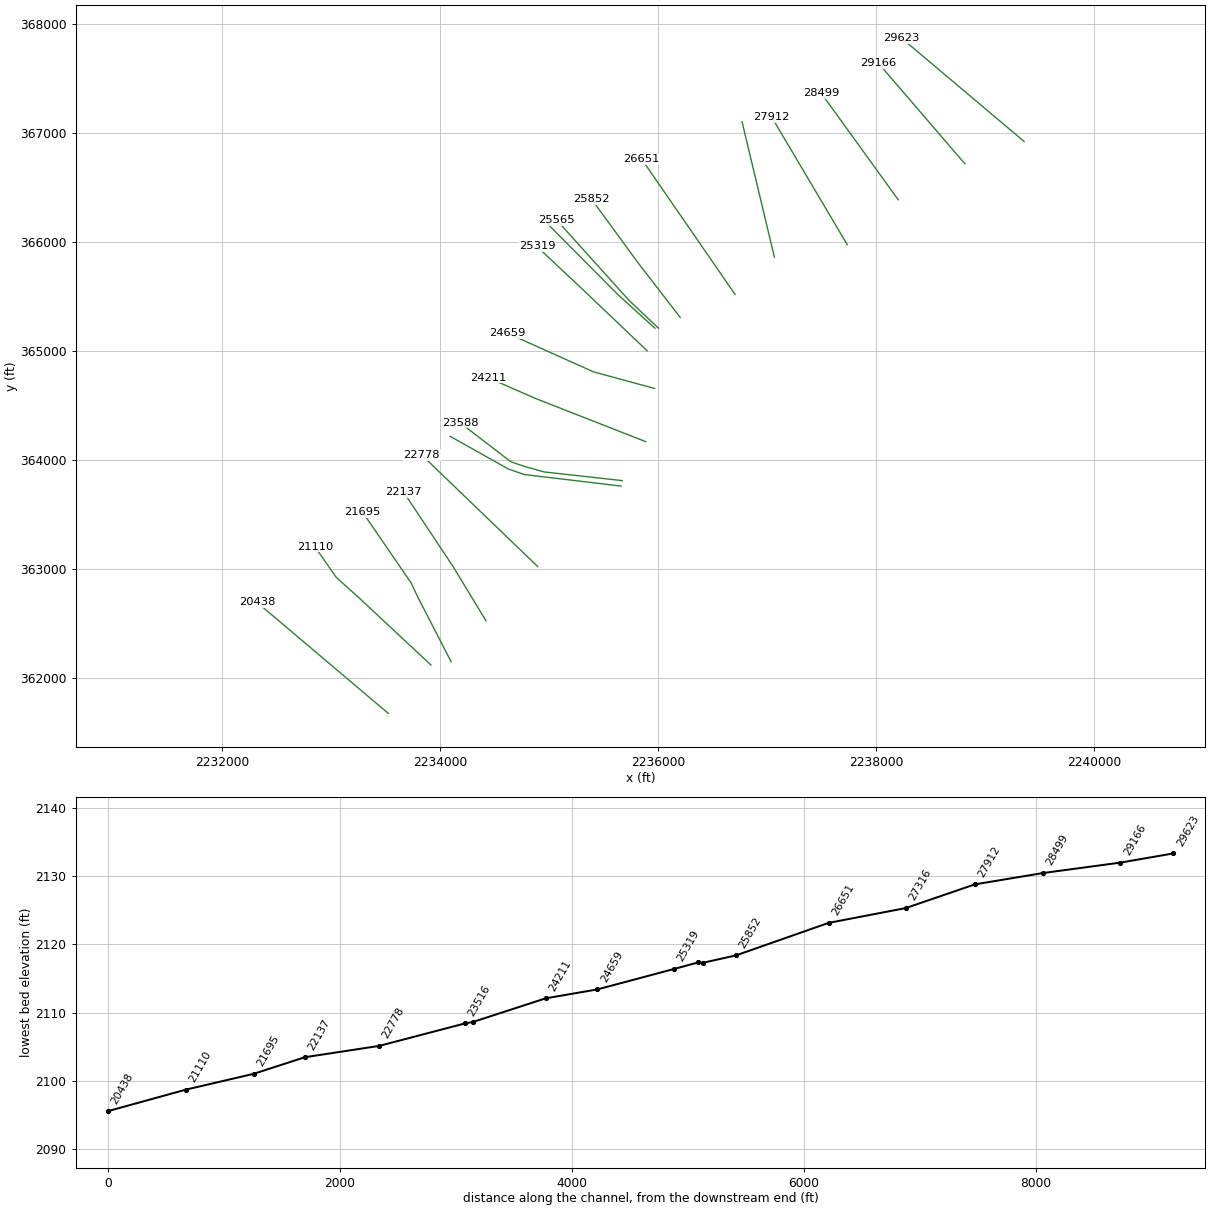
HEC-RAS study MFANTNYCK.prj: MFANTNYCK

--- MFANTNYCK.g01 (geometry) --- (continued)

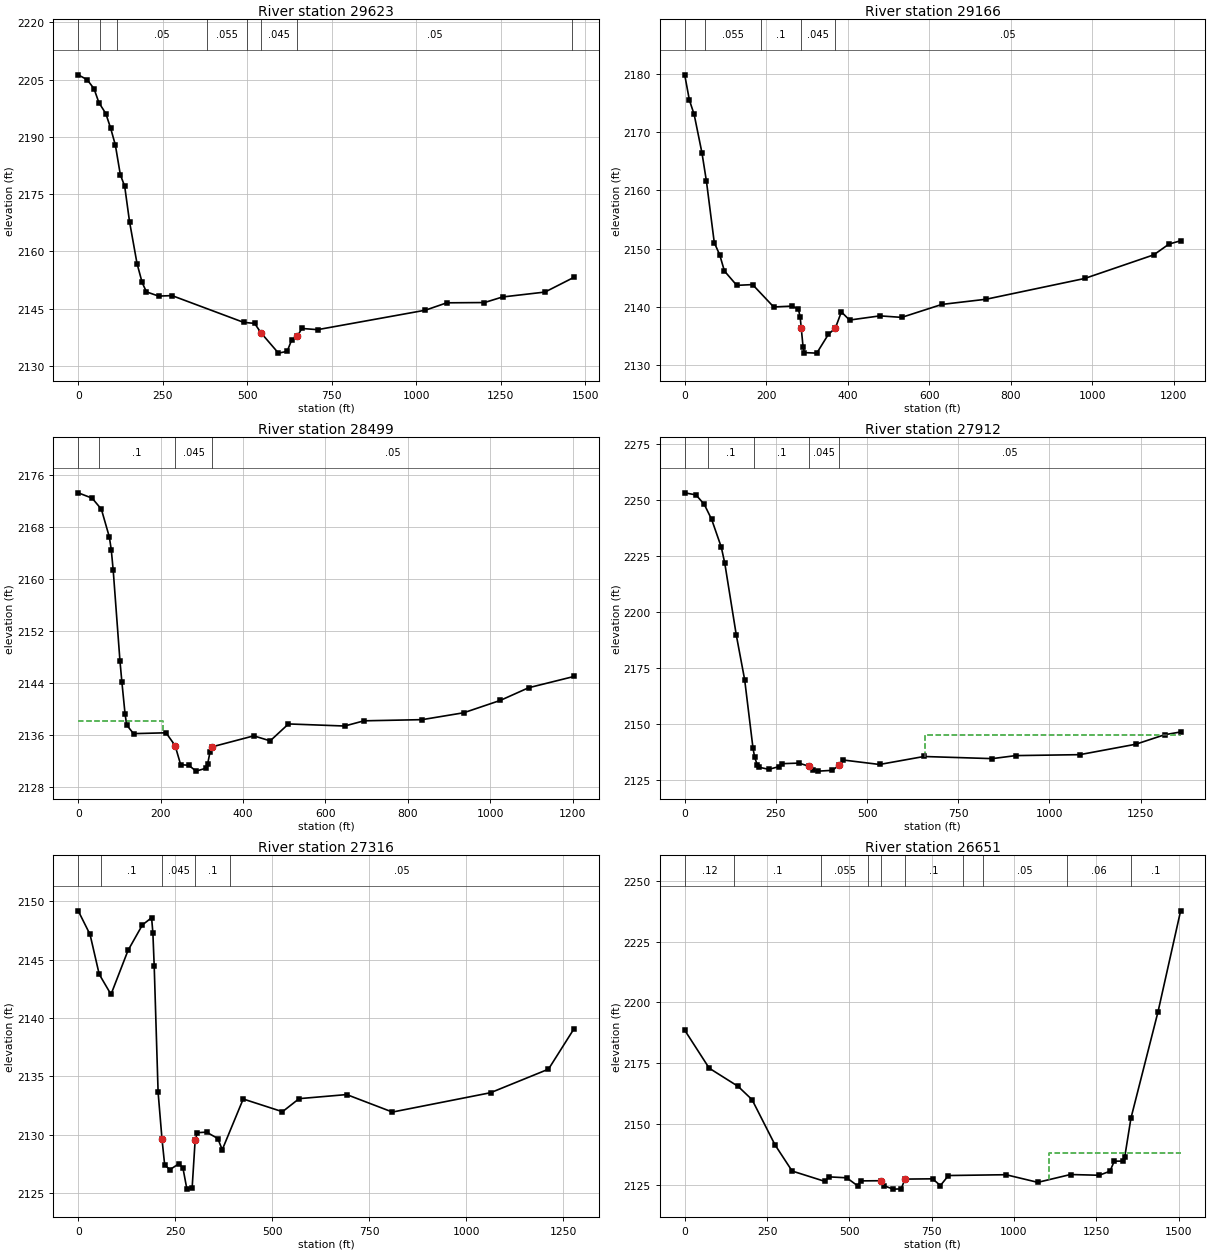
Type RM Length L Ch R = 1 ,29623   ,463,457.4,449
XS GIS Cut Line= 2
2239358.70820105366921.2383329722238237.18026039367867.418855309
#Sta/Elev= 30
       0 2206.26    26.4 2204.99    46.8 2202.62      61 2199.01    81.7  2196.1
      96 2192.27   109.9 2187.86   124.6 2180.11   137.5 2177.07   151.8 2167.82
     174 2156.83   189.1 2151.86   201.8  2149.4     238 2148.29   277.6 2148.42
   489.4 2141.41     522 2141.14   540.3 2138.72   592.5 2133.35   618.2 2133.82
   631.9 2136.86   647.8 2137.72   661.7 2139.81   708.3  2139.5  1027.3  2144.6
  1090.4 2146.53    1202  2146.6  1255.4 2148.06  1381.1 2149.35  1467.3 2153.23
#Mann= 8 ,-1 , 0
       0      .1       0   64.74      .1       0   113.3     .05       0
  382.13    .055       0  499.41      .1       0   540.3    .045       0
   647.8     .05       0 1459.71     .06       0
Bank Sta=540.3,647.8
XS Rating Curve= 0 ,0
Exp/Cntr=0.3,0.1

Type RM Length L Ch R = 1 ,29166   ,667.1,667.1,660.4
XS GIS Cut Line= 2
2238815.37365781366716.6800150572238021.90247571367639.988207817
#Sta/Elev= 30
       0 2179.88    11.5 2175.54    23.2 2173.06    42.4 2166.44    53.4 2161.55
    72.6 2151.01      86  2148.9    97.5 2146.13   127.8 2143.66   166.7 2143.79
   218.5 2139.94   263.8 2140.09   279.1 2139.56   283.5  2138.2   286.1  2136.3
   290.7 2132.99     294 2132.09   324.2    2132   352.8 2135.24   369.8  2136.3
   384.6 2139.09   404.7 2137.69   479.2 2138.41   532.7 2138.15   631.3 2140.38
   739.7 2141.27   981.7 2144.84  1151.5 2148.91  1188.8 2150.76  1217.4 2151.33
#Mann= 5 ,-1 , 0
       0      .1       0   48.94    .055       0  187.28      .1       0
   286.1    .045       0   369.8     .05       0
Bank Sta=286.1,369.8
XS Rating Curve= 0 ,0
Exp/Cntr=0.3,0.1

Type RM Length L Ch R = 1 ,28499   ,591.1,586.7,583.1
XS GIS Cut Line= 2
2238203.89883089366386.8119083942237499.33298281367362.210548148
#Sta/Elev= 30
       0 2173.23    33.8 2172.41    56.2 2170.71    75.5 2166.45    80.2 2164.49
    84.9 2161.33   101.3 2147.39     106 2144.14   113.7 2139.23   117.7 2137.55
   134.2 2136.23   213.1 2136.36   235.1 2134.39   248.6 2131.46   268.2 2131.37
     286 2130.47   310.5 2130.93     314 2131.54   319.9 2133.46   324.1 2134.19
     426 2135.89   465.8 2135.12   510.2 2137.72   646.5  2137.4   693.5  2138.2
   834.5 2138.38   935.5 2139.44  1024.3 2141.34  1092.8 2143.28  1203.3 2145.02
#Mann= 4 ,-1 , 0
       0     .12       0   51.02      .1       0   235.1    .045       0
   324.1     .05       0
#XS Ineff= 2 , 0
          205.21  2138.1
Permanent Ineff=
       F       F
Bank Sta=235.1,324.1
XS Rating Curve= 0 ,0
Exp/Cntr=0.3,0.1

Type RM Length L Ch R = 1 ,27912   ,607.5,596.5,583.4
XS GIS Cut Line= 2
2237737.18027614365973.3215936422237044.47201589367143.460329473
#Sta/Elev= 30
       0 2253.04      31 2252.12    53.8 2247.84      74 2241.14   100.4 2228.74
   109.9 2221.59   141.5 2189.51   164.4 2169.62   187.3 2139.03   191.8 2135.06
   198.7 2131.73   202.5  2130.6   230.4 2129.61   258.4 2130.81   267.4 2132.14
   313.1 2132.39   339.6 2131.05   351.2 2129.28   366.5 2128.81   404.6 2129.16
   423.7 2131.44   435.1 2133.76   534.2 2131.78     656 2135.34   843.1 2134.39
   907.9 2135.74  1083.3 2136.16  1236.7 2140.81  1315.8 2145.05  1359.8 2146.29
#Mann= 5 ,-1 , 0
       0     .12       0   64.09      .1       0  190.42      .1       0
   339.6    .045       0   423.7     .05       0
#XS Ineff= 2 , 0
                          657.61         2145.15
Permanent Ineff=
       F       F
Bank Sta=339.6,423.7
XS Rating Curve= 0 ,0
Exp/Cntr=0.3,0.1

Type RM Length L Ch R = 1 ,27316   ,654.3,664.5,678.1
XS GIS Cut Line= 2
2237068.77741347  365858.73816142236771.90267913367101.793746144
#Sta/Elev= 30
       0  2149.2    30.5 2147.17    54.1 2143.76    84.5 2142.03   128.3  2145.8
   165.4 2147.99   189.1 2148.61   192.4 2147.32   195.8 2144.49   205.9 2133.63
     216 2129.59   222.8 2127.41   236.3    2127   259.9 2127.52     270 2127.12
   280.1 2125.33   293.6 2125.44   301.3 2129.51   307.1 2130.17   330.7 2130.22
   359.7 2129.67   371.2 2128.71   425.2 2133.06   526.4 2131.97   569.3 2133.09
   691.9 2133.44   809.7 2131.94  1062.7  2133.6  1211.9 2135.62    1278  2139.1
#Mann= 5 ,-1 , 0
       0     .12       0   59.64      .1       0     216    .045       0
   301.3      .1       0   392.3     .05       0
Bank Sta=216,301.3
XS Rating Curve= 0 ,0
Exp/Cntr=0.3,0.1

Type RM Length L Ch R = 1 ,26651   ,773.1,798.6,774.8
XS GIS Cut Line= 2
2236707.30864821365518.1843805612235851.76377139366758.043777481
#Sta/Elev= 30
       0 2188.59    74.4 2172.94   162.1 2165.46   204.5    2160   274.4 2141.36
   326.3 2130.61   425.9 2126.34   437.9 2128.21   492.3 2127.82   524.9 2124.55
   534.7 2126.55   597.3 2126.62   605.3 2124.57   633.2 2123.16   657.4 2123.25
   669.2 2127.29   752.8  2127.4   776.7 2124.64   801.3 2128.76     976 2129.09
  1072.5 2125.95  1171.9 2129.17    1259 2128.87  1291.9 2130.53  1304.8 2134.67
    1332 2134.69  1336.7 2136.44  1355.5 2152.35  1437.7 2196.13  1506.4  2237.7
#Mann= 10 ,-1 , 0
       0     .12       0  149.92      .1       0  414.71    .055       0
  558.16    .025       0   597.3    .045       0   669.2      .1       0
  845.06    .055       0  905.87     .05       0 1160.85     .06       0
 1355.29      .1       0
#XS Ineff= 2 , 0
                         1107.41         2137.94
Permanent Ineff=
       F       F
Bank Sta=597.3,669.2
XS Rating Curve= 0 ,0
Exp/Cntr=0.3,0.1

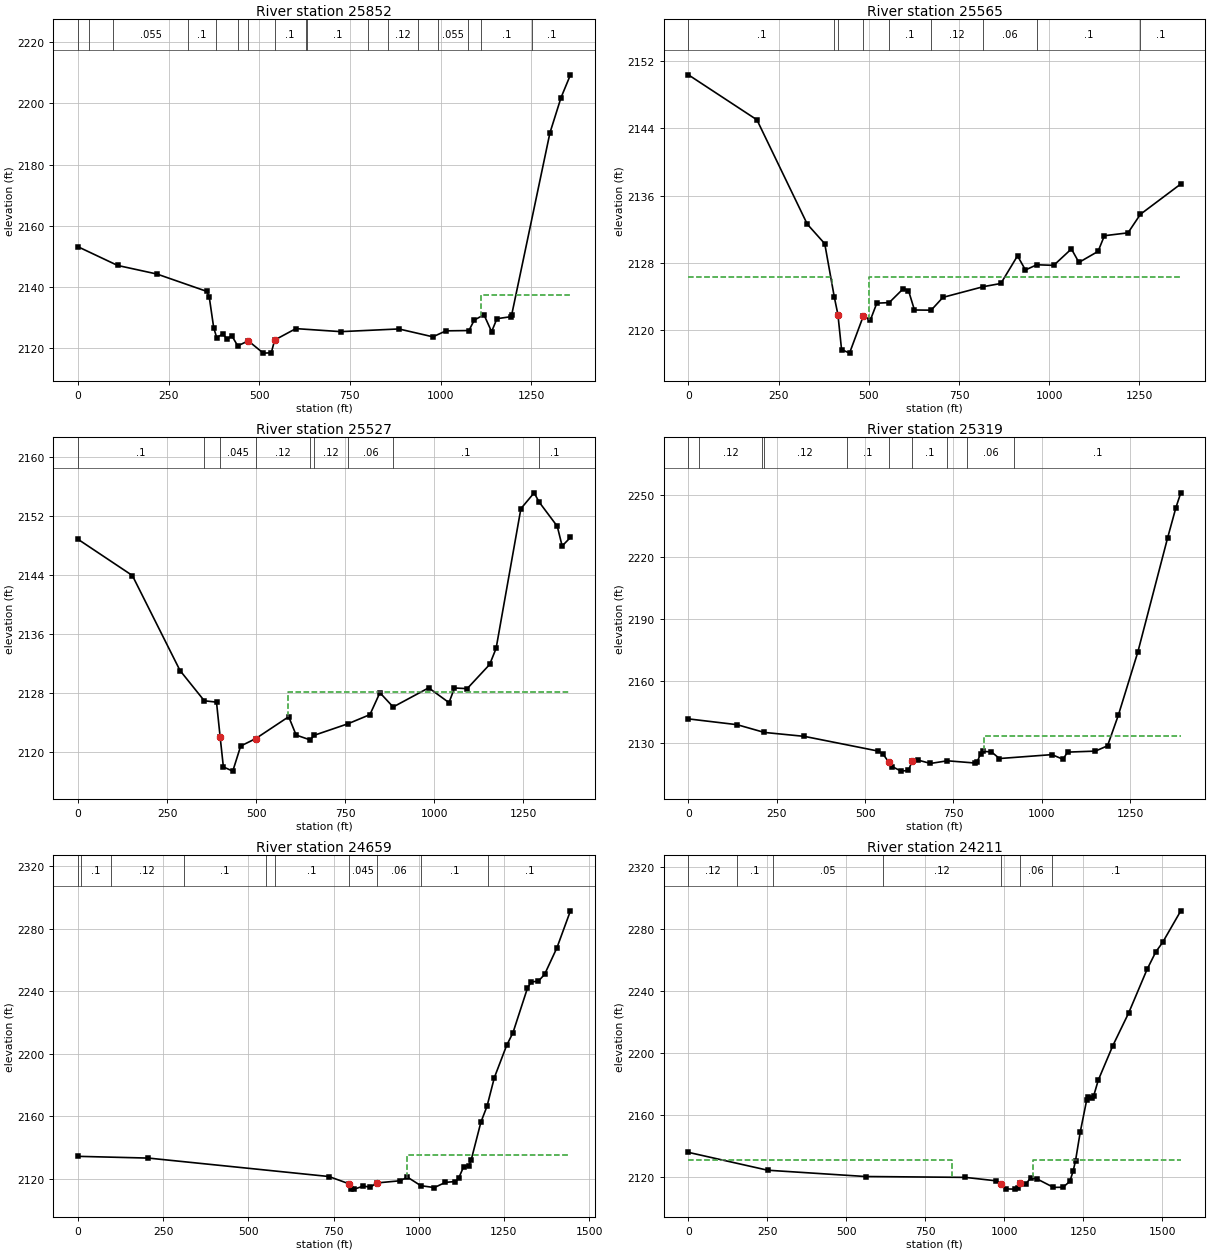
Type RM Length L Ch R = 1 ,25852   ,281.3,287.3,286.5
XS GIS Cut Line= 3
2236204.19416888365306.6549479812235811.83307697365815.335361063
2235389.95826456366393.460517138
#Sta/Elev= 30
       0 2153.14   109.1 2147.04   217.7 2144.23   355.2 2138.56   361.8 2136.79
   374.2 2126.68   382.5 2123.46   399.1 2124.65   411.5 2122.93     424 2124.09
   440.5 2120.76   469.5  2122.4     511 2118.39     533 2118.49   542.3 2122.67
   600.8  2126.4   724.8 2125.41   884.8 2126.29   978.7 2123.72  1014.9 2125.67
  1078.1 2125.77  1092.9 2129.19  1119.6 2130.93  1140.7 2125.39  1155.3 2129.64
  1193.1 2130.28  1195.9  2130.8  1301.5 2190.34  1332.2  2201.9  1358.1 2209.32
#Mann= 17 ,-1 , 0
       0    .055       0    31.6      .1       0   96.36    .055       0
  303.85      .1       0  379.65      .1       0  439.97     .12       0
   469.5    .045       0   542.3      .1       0  627.95     .05       0
  632.79      .1       0  800.21     .05       0  853.69     .12       0
  938.04      .1       0  993.35    .055       0 1075.87     .06       0
 1111.81      .1       0 1252.87      .1       0
#XS Ineff= 2 , 0
                         1110.81         2137.39
Permanent Ineff=
       F       F
Bank Sta=469.5,542.3
XS Rating Curve= 0 ,0
Exp/Cntr=0.5,0.3

Type RM Length L Ch R = 1 ,25565   ,34.8,38.6,54.7
XS GIS Cut Line= 3
2236005.86254455365206.832312971 2235737.8069783365459.610022649
2235071.14033264366199.888069645
#Sta/Elev= 30
       0 2150.34   189.9    2145   329.5 2132.61   377.9 2130.29   404.6 2123.91
   414.4 2121.88   424.5 2117.73   446.6  2117.3   484.8  2121.7     504 2121.19
   522.2 2123.23   556.6  2123.3   595.8 2124.96     610 2124.73   626.5 2122.42
   672.9  2122.4   705.5 2123.92   817.5 2125.19     866 2125.57   912.2 2128.85
   934.1 2127.17   965.6 2127.79  1012.5 2127.72  1061.5 2129.67  1082.4 2128.07
  1135.4 2129.38    1153 2131.24  1218.4 2131.58  1252.7 2133.78  1364.7 2137.38
#Mann= 9 ,-1 , 0
       0      .1       0   404.6     .12       0   414.4    .045       0
   484.8     .12       0   556.6      .1       0   672.9     .12       0
   817.5     .06       0   965.6      .1       0  1252.7      .1       0
#XS Ineff= 2 , 0
           398.4  2126.3   500.8          2126.3
Permanent Ineff=
       F       F
Bank Sta=414.4,484.8
XS Rating Curve= 0 ,0
Exp/Cntr=0.5,0.3

Type RM Length L Ch R = 1 ,25527   ,204.6,207.8,194.7
XS GIS Cut Line= 3
2235972.52927789365206.8323129712235632.25141513365516.554462567
2234982.25140281366170.721133232
#Sta/Elev= 30
       0 2148.84   152.5 2143.92   286.3 2131.02   354.5 2126.91   388.7 2126.73
   398.9 2122.01     408 2117.93   434.4 2117.36   456.6 2120.77   498.3 2121.76
   591.4 2124.75   612.2 2122.26   651.6  2121.6   663.2 2122.23   757.7 2123.79
   819.4 2125.03   847.4 2128.01   884.6 2126.07   984.4 2128.67  1041.4 2126.66
  1056.8 2128.65  1092.4 2128.56  1155.5 2131.84  1173.6 2134.03  1243.2    2153
  1280.4 2155.15  1294.2 2153.91  1345.3 2150.61    1359 2147.93  1382.3 2149.09
#Mann= 9 ,-1 , 0
       0      .1       0   354.5     .12       0   398.9    .045       0
   498.3     .12       0   651.6      .1       0   663.2     .12       0
   757.7     .06       0   884.6      .1       0  1294.2      .1       0
#XS Ineff= 2 , 0
           382.9  2126.3  589.34         2128.17
Permanent Ineff=
       F       F
Bank Sta=398.9,498.3
XS Rating Curve= 0 ,0
Exp/Cntr=0.5,0.3

Type RM Length L Ch R = 1 ,25319   ,643.6,659.5,660.6
XS GIS Cut Line= 3
2235902.11078355 364999.363239722235292.73601805365579.224284723
2234889.95828031 365957.69662489
#Sta/Elev= 30
       0 2141.72   137.9 2138.91   214.9 2135.16   328.2 2133.25   536.4 2126.15
     551 2124.69  566.662120.855   576.5 2118.64     602  2116.4   622.9 2116.74
   632.9  2121.1   649.7 2121.76   685.3 2120.12   732.9 2121.41   812.7 2120.31
   817.9 2121.02   827.1 2124.82   835.3 2125.94   857.9 2125.74   880.5  2122.5
  1029.2  2124.4  1060.5 2122.14  1073.2 2125.61  1152.1  2126.1  1186.5 2128.67
  1217.1  2143.5  1272.1 2174.02  1356.3 2229.28  1380.1 2244.14  1393.9 2251.29
#Mann= 10 ,-1 , 0
       0      .1       0   31.14     .12       0   208.7      .1       0
  213.73     .12       0  448.27      .1       0  566.66    .045       0
   632.9      .1       0  730.94     .12       0  788.97     .06       0
   922.4      .1       0
#XS Ineff= 2 , 0
                          836.67         2133.57
Permanent Ineff=
       F       F
Bank Sta=566.66,632.9
XS Rating Curve= 0 ,0
Exp/Cntr=0.3,0.1

Type RM Length L Ch R = 1 ,24659   ,444.7,447.8,444.4
XS GIS Cut Line= 3
2235969.81930955364653.8770540652235409.05533922364806.654963732
2234620.86104947365160.821578234
#Sta/Elev= 30
       0 2134.38   206.8 2133.26   736.5 2121.47   795.1 2116.84   801.2 2113.57
   811.1 2113.41   837.2 2115.36   858.4 2114.67   876.2 2117.35   945.1 2118.75
   966.7 2121.09  1006.2 2115.61  1045.8 2114.41  1078.2 2117.72    1107 2118.28
    1117 2120.33  1132.1 2127.86  1146.8 2128.27  1153.7 2131.85  1182.5 2156.27
  1200.5 2166.44    1222 2184.76    1258 2205.32  1276.5 2213.39  1319.1 2241.94
  1329.9 2245.86  1351.5 2246.49  1369.5 2250.78  1405.5  2267.7  1445.3  2291.4
#Mann= 10 ,-1 , 0
       0     .12       0    7.38      .1       0   95.42     .12       0
  310.95      .1       0  550.78     .12       0  579.27      .1       0
   795.1    .045       0   876.2     .06       0 1006.49      .1       0
  1203.7      .1       0
#XS Ineff= 2 , 0
                          964.35         2135.43
Permanent Ineff=
       F       F
Bank Sta=795.1,876.2
XS Rating Curve= 0 ,0
Exp/Cntr=0.3,0.1

Type RM Length L Ch R = 1 ,24211   ,622.4,623.9,624.8
XS GIS Cut Line= 3
 2235888.2220318364166.0299326482234874.33298346364563.599347472
2234443.77741414364752.835517555
#Sta/Elev= 30
       0  2135.8   251.1 2124.28   561.1 2120.22   876.7 2119.67   972.6 2117.49
   988.5 2115.33  1005.5 2112.22  1033.4 2112.09  1042.4 2112.56  1050.6 2115.76
  1068.8  2115.5    1084 2119.29  1103.8  2118.7  1156.2 2113.22  1186.5 2113.29
    1208 2117.07  1218.5 2123.75  1226.1 2130.52  1240.9 2148.85  1261.7 2169.88
  1265.3 2171.29  1279.6 2170.91  1283.3 2172.07  1298.1 2182.39  1344.1 2204.58
  1394.3 2225.69  1452.5 2253.74  1480.3 2265.08  1501.8 2271.16  1559.4 2291.54
#Mann= 7 ,-1 , 0
       0     .12       0  153.71      .1       0  266.81     .05       0
  615.78     .12       0   988.5    .045       0  1050.6     .06       0
 1150.45      .1       0
#XS Ineff= 2 , 0
          833.96 2131.16 1090.21         2131.16
Permanent Ineff=
       F       F
Bank Sta=988.5,1050.6
XS Rating Curve= 0 ,0
Exp/Cntr=0.5,0.3

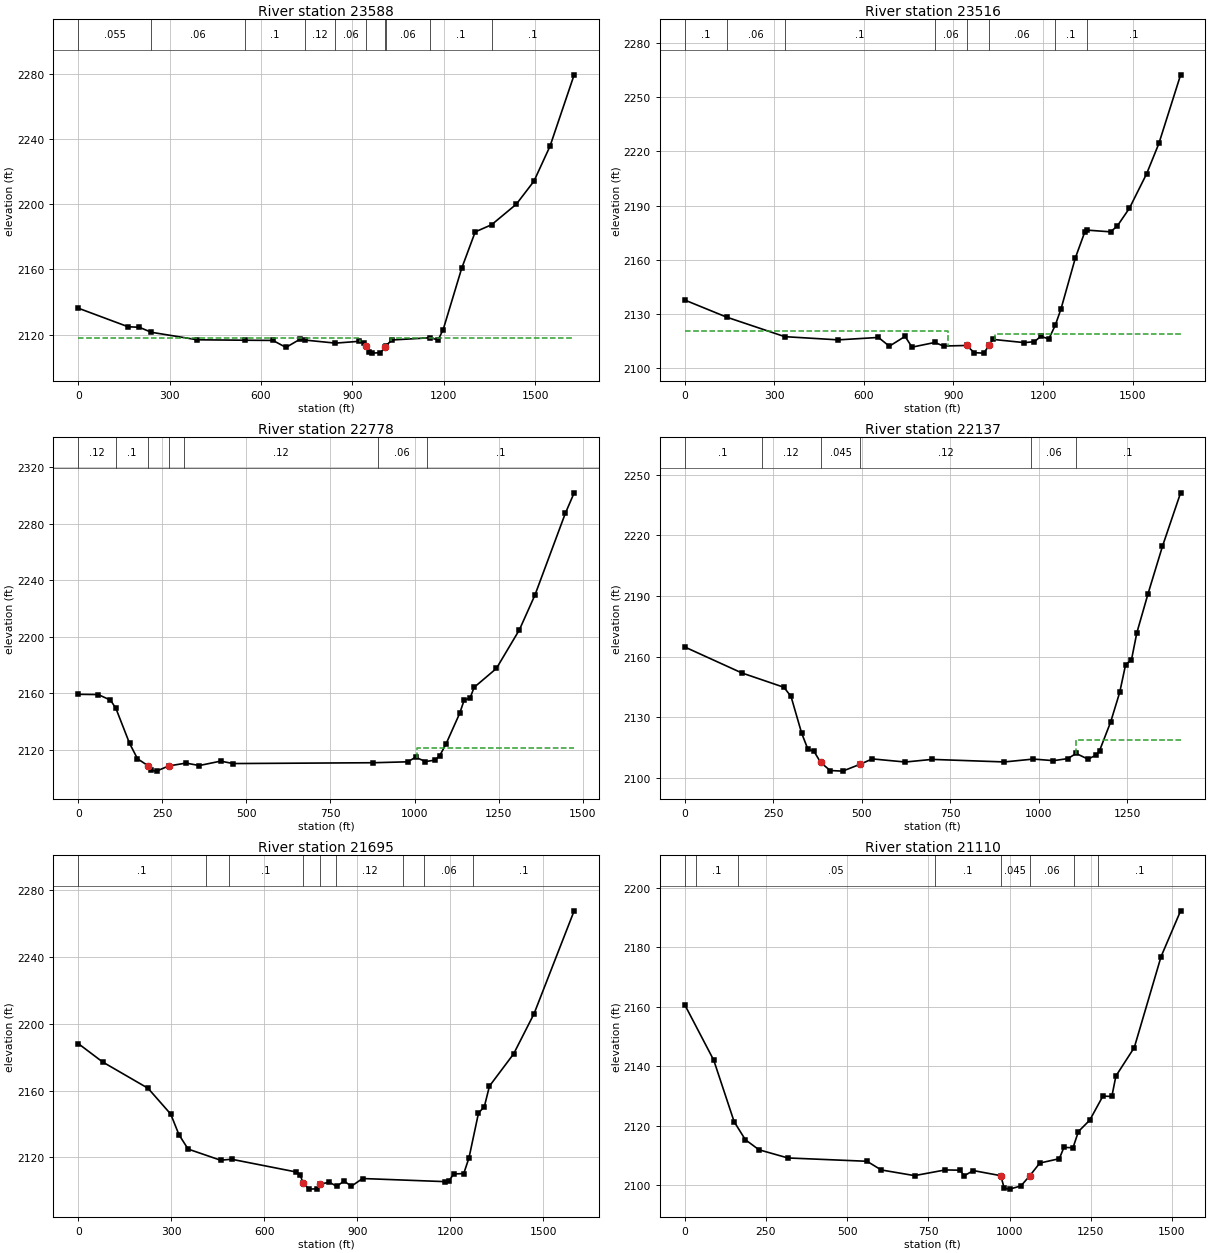
Type RM Length L Ch R = 1 ,23588   ,71.2,71.9,70.8
XS GIS Cut Line= 5
2235672.94424714363808.3908841462234954.19437231363888.252272978
 2234759.7498793363943.8076080532234650.37476997363982.002085477
2234185.09715723364339.641133979
#Sta/Elev= 30
       0 2136.22   163.7 2124.82   200.8 2124.48   239.9 2121.43   391.5 2116.82
   548.1 2116.55   639.1 2116.43     682 2112.15   728.4 2117.19   744.9 2116.64
   844.4 2114.78   922.1 2115.88   936.7 2115.15   944.3 2112.79   954.1 2109.12
     964 2108.64   992.3 2108.91  1008.4 2112.43  1010.3 2113.31  1030.5 2116.71
  1154.7 2118.06  1181.6 2116.75  1198.2 2123.11  1258.8 2160.62  1303.3    2183
  1357.1 2187.39  1438.2 2199.98  1496.1 2214.09    1549 2235.64  1628.1 2279.33
#Mann= 10 ,-1 , 0
       0    .055       0   239.9     .06       0   548.1      .1       0
   744.9     .12       0   844.4     .06       0   944.3    .045       0
  1008.4    .045       0  1010.3     .06       0  1154.7      .1       0
  1357.1      .1       0
#XS Ineff= 2 , 0
           924.3    2118  1028.4            2118
Permanent Ineff=
       F       F
Bank Sta=944.3,1008.4
XS Rating Curve= 0 ,0
Exp/Cntr=0.5,0.3

Type RM Length L Ch R = 1 ,23516   ,730.5,738.1,710.6
XS GIS Cut Line= 4
 2235662.5276013363758.0438719842234775.37484805363863.946547315
2234629.54147831363914.2938875562234094.81912255364214.641055897
#Sta/Elev= 30
       0 2137.79   140.2 2128.34   335.1 2117.52   514.3 2115.75     649 2117.08
   685.4 2112.23   738.2 2117.69   761.3 2111.71   837.6  2114.3     867 2112.34
   944.3 2112.64   969.9 2108.65  1001.1 2108.41  1020.1 2112.66  1032.4    2116
  1137.6 2114.22  1171.3 2114.74  1192.9 2117.72  1219.5 2116.24  1241.2 2123.84
  1260.5 2132.93  1308.6 2161.16  1339.6 2175.22    1347 2176.46  1426.2  2175.5
  1448.4 2178.62  1489.4 2188.53  1547.2 2207.63  1588.2 2224.38    1661 2262.35
#Mann= 8 ,-1 , 0
       0      .1       0   140.2     .06       0   335.1      .1       0
   837.6     .06       0   944.3    .045       0  1020.1     .06       0
  1241.2      .1       0    1347      .1       0
#XS Ineff= 2 , 0
          882.68 2120.69 1037.85         2119.24
Permanent Ineff=
       F       F
Bank Sta=944.3,1020.1
XS Rating Curve= 0 ,0
Exp/Cntr=0.5,0.3

Type RM Length L Ch R = 1 ,22778   ,641.9,640.3,630.3
XS GIS Cut Line= 2
2234896.90249214363020.1965943872233834.40264864364042.766071558
#Sta/Elev= 30
       0 2159.37    59.5 2159.19    95.9 2155.28   112.1 2149.42   152.5 2124.82
   176.2 2113.88   207.2 2108.98   216.5 2105.69     233 2105.12   268.9 2108.79
   320.9 2110.79     360 2109.06   423.7  2112.2   460.1 2110.47   877.8 2111.05
   979.9  2111.7  1003.1 2114.95  1032.5 2111.87  1060.9  2112.9    1075 2116.08
  1093.6 2124.28  1134.1 2145.86  1147.7 2155.37    1165 2156.61  1177.1 2164.27
  1243.4 2177.64  1311.7  2204.9  1358.1 2229.53  1448.3 2287.15  1474.6 2301.68
#Mann= 7 ,-1 , 0
       0     .12       0  111.93      .1       0   207.2    .045       0
   268.9      .1       0  315.53     .12       0  891.37     .06       0
 1035.79      .1       0
#XS Ineff= 2 , 0
                         1007.81         2121.36
Permanent Ineff=
       F       F
Bank Sta=207.2,268.9
XS Rating Curve= 0 ,0
Exp/Cntr=0.3,0.1

Type RM Length L Ch R = 1 ,22137   ,454.6,442.6,429
XS GIS Cut Line= 3
2234422.94412246362522.1063832342234125.02772355363013.773050815
 2233668.7776518363701.272988141
#Sta/Elev= 30
       0 2164.84   161.3    2152   280.2  2144.9   300.2 2140.36   330.1 2122.27
   347.9 2114.25   364.7 2113.34   383.6  2107.8   410.7 2103.76   445.9 2103.46
     496 2106.91   529.6  2109.5   622.9 2107.96   698.3 2109.26   902.5    2108
   984.3 2109.42  1041.1 2108.64  1081.4 2109.64    1105 2112.18  1138.7 2109.38
  1162.3  2111.5  1171.3 2113.64  1202.6  2127.8  1228.1 2142.43  1244.7  2156.1
  1261.2 2158.43  1276.5  2171.9    1308 2191.14  1348.8 2214.64    1400 2241.03
#Mann= 6 ,-1 , 0
       0      .1       0  217.19     .12       0   383.6    .045       0
     496     .12       0  978.57     .06       0 1104.06      .1       0
#XS Ineff= 2 , 0
                         1104.47         2118.69
Permanent Ineff=
       F       F
Bank Sta=383.6,496
XS Rating Curve= 0 ,0
Exp/Cntr=0.3,0.1

Type RM Length L Ch R = 1 ,21695   ,570.4,584.2,618.3
XS GIS Cut Line= 4
2234104.19410381362145.0228198172233795.86105905362742.939602971
2233737.52751431362867.9396810532233291.69408838363517.939693391
#Sta/Elev= 30
       0 2188.15      79 2177.09   225.1 2161.38   298.2 2145.94   324.8 2133.58
   354.3 2124.99   458.9 2118.33   494.6  2118.9   700.8 2111.35   715.3 2109.58
   725.1 2104.64   744.2 2101.02   769.6 2101.22   780.4 2103.94   809.4 2105.21
   833.1  2102.7     857 2105.81   880.9 2102.78   916.7 2107.37  1183.2  2105.5
  1195.2 2105.88  1210.3 2110.09  1242.9 2110.33  1259.8 2119.71  1290.5 2146.52
  1309.4 2150.44  1325.9 2162.71  1403.8 2181.97  1469.7 2206.04  1598.9 2267.58
#Mann= 9 ,-1 , 0
       0      .1       0  410.79     .05       0  486.34      .1       0
   725.1    .045       0   780.4      .1       0  831.83     .12       0
 1048.11      .1       0 1116.36     .06       0 1271.58      .1       0
Bank Sta=725.1,780.4
XS Rating Curve= 0 ,0
Exp/Cntr=0.3,0.1

Type RM Length L Ch R = 1 ,21110   ,668.1,672.9,671.9
XS GIS Cut Line= 4
2233918.77747989362115.8562114832233252.11083423362738.772944644
2233050.02757697362920.0229102222232854.19430722363201.273003891
#Sta/Elev= 30
       0 2160.73    89.5 2142.03   152.3 2121.35   186.8 2115.31   228.7 2111.93
   317.6 2109.18   561.3 2108.06   604.9 2105.15   707.5 2103.24   801.9 2105.15
   846.8 2105.07   860.7  2103.2   888.4 2104.94   972.9 2103.22   983.8 2098.95
  1000.1  2098.7  1034.9 2099.77  1062.8 2103.25    1093 2107.46  1153.2 2108.93
  1167.4 2112.72  1195.4 2112.62  1211.9 2118.05  1246.9 2121.88  1287.3 2129.97
  1314.9 2129.85  1327.4 2136.72    1384  2146.3  1466.4 2176.86  1526.6 2192.25
#Mann= 8 ,-1 , 0
       0      .1       0   35.14      .1       0  162.59     .05       0
  769.83      .1       0   972.9    .045       0  1062.8     .06       0
 1198.55      .1       0 1272.72      .1       0
Bank Sta=972.9,1062.8
XS Rating Curve= 0 ,0
Exp/Cntr=0.3,0.1

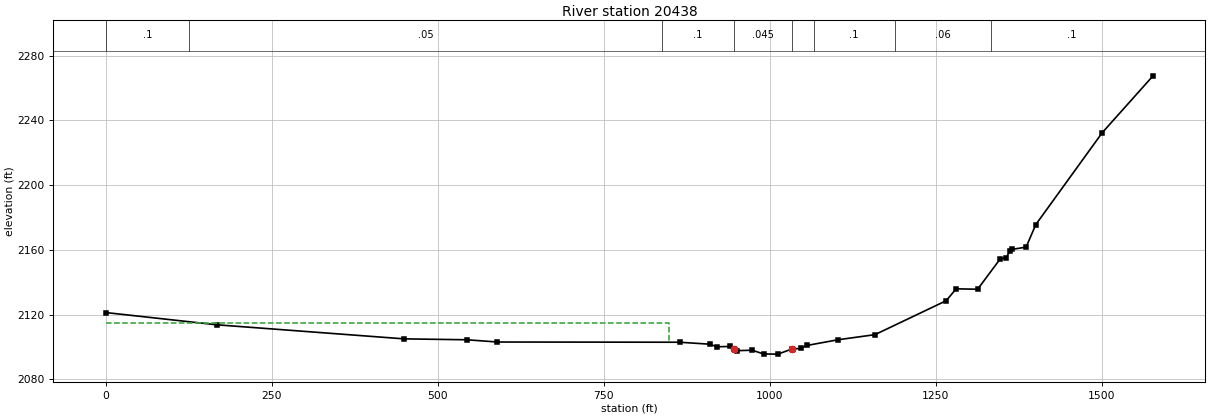
Type RM Length L Ch R = 1 ,20438   ,687.7,678.5,672.1
XS GIS Cut Line= 2
2233527.11094038361672.1064428092232322.94438547362690.856373817
#Sta/Elev= 30
       0 2121.22   166.9 2113.67   449.3 2104.97   543.8 2104.41   589.9 2103.02
   864.2 2102.89   909.9 2101.67   920.1 2100.08   939.8 2100.28   946.7 2099.01
   951.4 2097.69   973.6 2097.95   990.8 2095.62  1012.3 2095.54  1033.7 2098.76
  1046.8 2099.05  1056.2 2100.91    1103 2104.43  1158.4 2107.56  1265.7 2128.53
  1280.8 2135.88  1313.1 2135.62  1346.8  2154.2  1356.5 2155.21  1361.1 2158.97
  1364.6 2160.21  1386.1 2161.65  1400.7 2175.56  1500.8 2232.34  1577.3 2267.45
#Mann= 8 ,-1 , 0
       0      .1       0  125.06     .05       0  837.76      .1       0
   946.7    .045       0  1033.7     .05       0 1066.07      .1       0
 1187.99     .06       0 1333.12      .1       0
#XS Ineff= 2 , 0
          847.54 2114.92
Permanent Ineff=
       F       F
Bank Sta=946.7,1033.7
XS Rating Curve= 0 ,0
Exp/Cntr=0.3,0.1