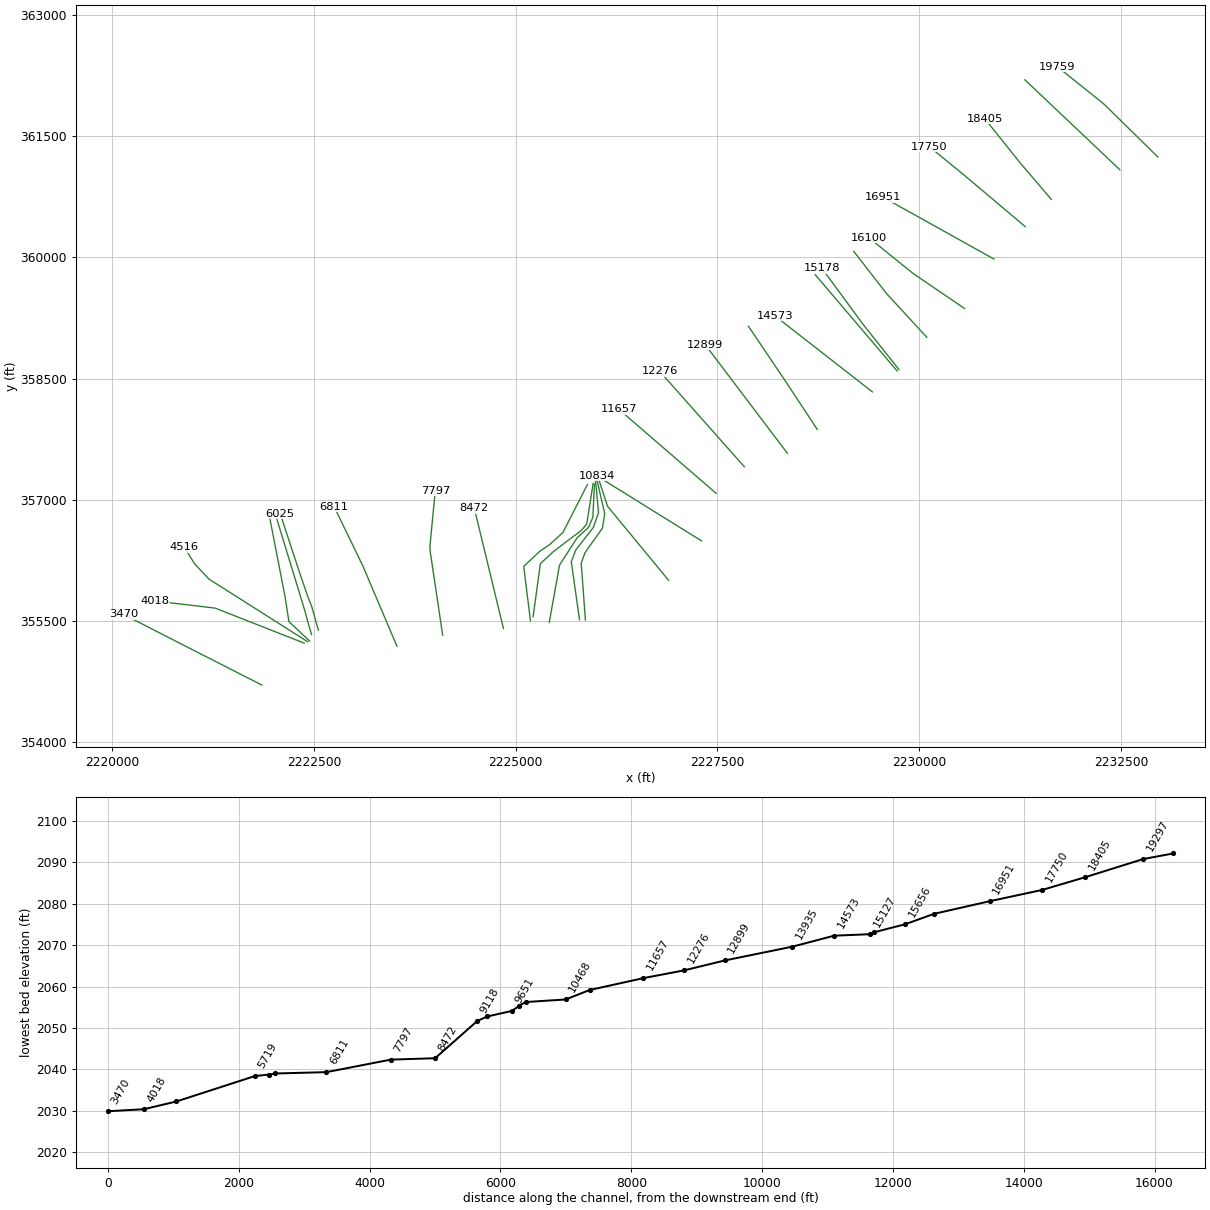
HEC-RAS study MFANTNYCK.prj: MFANTNYCK

--- MFANTNYCK.g01 (geometry) --- (continued)

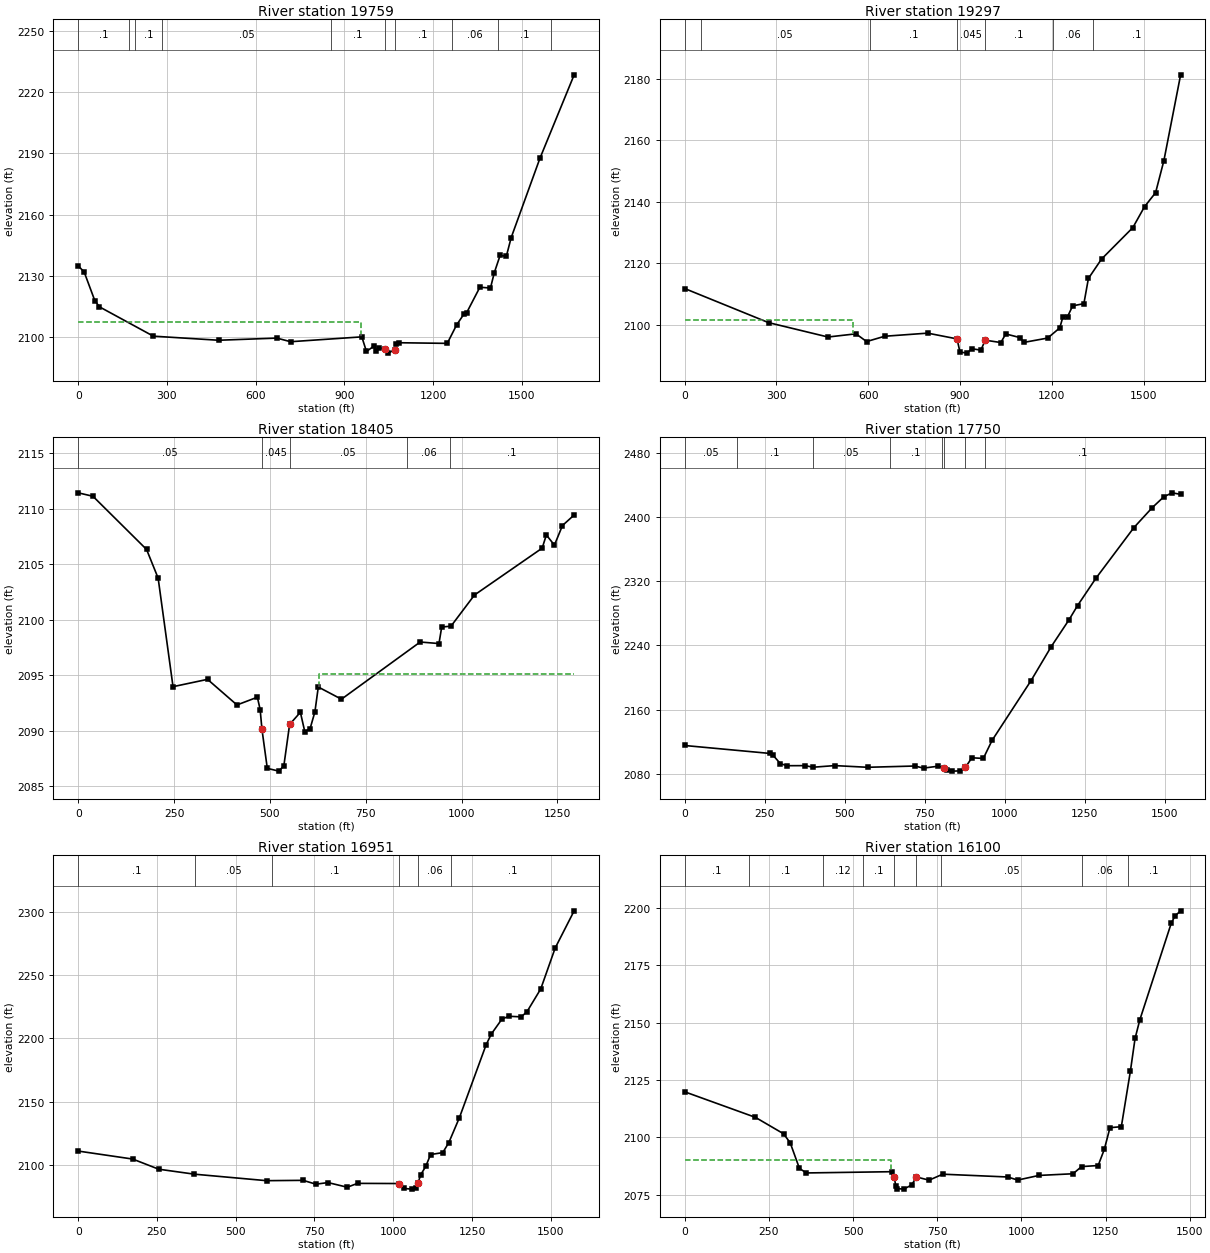
Type RM Length L Ch R = 1 ,19759   ,460.7,461.9,472.3
XS GIS Cut Line= 3
2232958.36076555361245.0229793942232285.44413239361905.439637557
 2231712.5276273362363.773038477
#Sta/Elev= 30
       0 2134.88    20.2 2131.82      56 2117.86    71.7 2114.79     254 2100.41
   474.4 2098.41   671.6 2099.46     718 2097.69   958.7 2100.07   974.4  2092.9
   999.1 2095.49  1006.1 2093.27  1017.8 2094.73  1037.5 2093.99    1048  2092.1
  1069.3 2093.73  1074.2 2096.69  1084.7 2097.19  1247.5 2096.88  1279.2 2105.92
  1304.5 2111.36  1312.9 2111.84  1357.8 2124.38  1393.6    2124  1406.5 2131.48
  1426.1 2139.94  1447.3 2139.57  1463.6 2148.68  1560.8 2187.55  1676.5 2228.45
#Mann= 10 ,-1 , 0
       0      .1       0  172.99     .05       0   191.8      .1       0
  284.63     .05       0  852.91      .1       0  1037.5    .045       0
  1069.3      .1       0    1262     .06       0 1418.61      .1       0
 1597.81      .1       0
#XS Ineff= 2 , 0
          955.52 2107.54
Permanent Ineff=
       F       F
Bank Sta=1037.5,1069.3
XS Rating Curve= 0 ,0
Exp/Cntr=0.3,0.1

Type RM Length L Ch R = 1 ,19297   ,895.4,891.8,886.7
XS GIS Cut Line= 2
2232487.52771772361086.6896346512231310.44411388362201.273035392
#Sta/Elev= 30
       0 2111.75   274.2 2100.66   468.5 2095.98   559.9 2097.02   594.7  2094.5
   653.7 2096.23   794.3 2097.24   890.3 2095.37   899.8 2091.09   923.7 2090.74
     938 2092.19   968.3  2091.7   982.3 2094.96  1033.4 2094.18  1049.6 2096.98
  1096.5 2095.78  1107.6 2094.21  1186.5 2095.64    1226 2098.94  1236.6 2102.61
  1251.5 2102.61  1268.2 2106.11  1304.9 2106.84  1319.7 2115.03  1362.6 2121.33
    1465 2131.58  1503.2 2138.38  1539.3 2142.93  1566.4 2153.35  1621.1 2181.26
#Mann= 7 ,-1 , 0
       0      .1       0   51.86     .05       0  605.04      .1       0
   890.3    .045       0   982.3      .1       0 1204.69     .06       0
 1335.52      .1       0
#XS Ineff= 2 , 0
          550.08 2101.41
Permanent Ineff=
       F       F
Bank Sta=890.3,982.3
XS Rating Curve= 0 ,0
Exp/Cntr=0.3,0.1

Type RM Length L Ch R = 1 ,18405   ,657.7,655,664.7
XS GIS Cut Line= 3
2231637.52744922360720.0230451382231260.44421388361161.689484641
2230814.61078797 361717.93968448
#Sta/Elev= 30
       0 2111.45    38.4 2111.14   178.3 2106.34   208.5 2103.75   247.3 2093.96
   337.3 2094.62   414.1 2092.31   467.3 2093.01   474.6 2091.89   479.2 2090.13
   493.2 2086.59   523.4 2086.34   536.4 2086.83   551.4 2090.55   579.5 2091.65
     591  2089.9   604.8 2090.17   617.4 2091.69   626.2 2093.93   686.6 2092.83
     892 2097.99     941 2097.85   948.1 2099.34   972.4 2099.42  1033.6 2102.23
  1210.2 2106.46  1221.1 2107.65  1242.1 2106.73  1263.1  2108.5  1293.6 2109.45
#Mann= 5 ,-1 , 0
       0     .05       0   479.2    .045       0   551.4     .05       0
  857.17     .06       0  970.59      .1       0
#XS Ineff= 2 , 0
                           627.5          2095.1
Permanent Ineff=
       F       F
Bank Sta=479.2,551.4
XS Rating Curve= 0 ,0
Exp/Cntr=0.3,0.1

Type RM Length L Ch R = 1 ,17750   ,792.1,798.9,802.1
XS GIS Cut Line= 3
2231314.61077222360382.5230639732230558.36097239361020.023101315
2230125.02752148361374.189715818
#Sta/Elev= 30
       0  2115.2   265.7 2105.34   275.4 2103.32   298.9 2092.58   319.9 2090.03
   375.7 2090.13   401.3 2088.15   468.5 2090.17   571.3 2088.06   718.8 2089.65
   745.9 2087.04     790 2089.34   810.4 2087.74   820.4 2084.23   835.8 2083.28
   861.3 2083.57   876.6 2087.92   896.9 2099.91   932.6 2099.07   960.1 2121.64
  1081.9 2196.15  1144.5 2238.22  1200.3 2271.77    1227  2289.5    1284 2323.34
  1403.1 2386.67  1460.3  2411.5  1496.6 2425.06  1522.5 2429.89  1548.8 2427.98
#Mann= 8 ,-1 , 0
       0     .05       0  163.89      .1       0  399.65     .05       0
  639.97      .1       0  802.12     .06       0   810.4    .045       0
   876.6     .06       0  938.21      .1       0
Bank Sta=810.4,876.6
XS Rating Curve= 0 ,0
Exp/Cntr=0.3,0.1

Type RM Length L Ch R = 1 ,16951   ,841.7,851.7,830.4
XS GIS Cut Line= 2
2230927.11089106359980.4395505642229552.11101639360747.106324315
#Sta/Elev= 30
       0 2110.74     173 2104.41   255.7 2096.36   368.9 2092.42   597.7 2087.28
     714 2087.54   754.4  2084.5     793 2085.77     854 2082.09   886.7 2085.14
  1017.3 2085.01  1033.2 2081.12  1059.5 2080.58  1070.8 2081.35  1078.3  2085.2
  1087.2 2091.95  1103.2 2098.61  1118.6 2107.99  1157.2 2109.51  1176.5 2117.48
  1210.2  2137.3  1294.6  2194.8  1311.2 2203.43    1345  2215.3    1367 2217.56
  1406.4 2217.08  1424.9 2221.31  1468.3 2239.25  1514.1 2271.66  1574.3 2301.11
#Mann= 6 ,-1 , 0
       0      .1       0  371.54     .05       0  613.73      .1       0
  1017.3    .045       0  1078.3     .06       0 1183.87      .1       0
Bank Sta=1017.3,1078.3
XS Rating Curve= 0 ,0
Exp/Cntr=0.3,0.1

Type RM Length L Ch R = 1 ,16100   ,447.1,444.1,433
XS GIS Cut Line= 3
2230562.52763072359367.9394632282229922.94426422359803.356243312
2229379.19436747360242.939681724
#Sta/Elev= 30
       0 2119.88   210.1 2108.76   293.5 2101.63   313.3 2097.72   340.7  2086.6
   360.9 2084.57   617.2 2085.12   622.9 2082.61   626.9 2078.76   630.8 2077.76
   650.7 2077.53   674.5 2079.37   688.1 2082.82   726.1 2081.43   766.3 2084.03
   959.7 2082.81   988.9 2081.47  1052.2 2083.49  1153.4 2084.22  1178.7 2087.34
    1228  2087.8  1246.2 2094.81  1263.1 2104.27  1296.8  2104.7  1323.7 2128.84
  1337.6 2143.09  1351.6 2151.13  1445.5 2193.42  1456.6 2196.46  1472.9 2198.63
#Mann= 9 ,-1 , 0
       0      .1       0  190.77      .1       0  410.02     .12       0
  529.41      .1       0   622.9    .045       0   688.1      .1       0
  761.91     .05       0  1180.1     .06       0 1316.26      .1       0
#XS Ineff= 2 , 0
          613.92 2090.08
Permanent Ineff=
       F       F
Bank Sta=622.9,688.1
XS Rating Curve= 0 ,0
Exp/Cntr=0.3,0.1

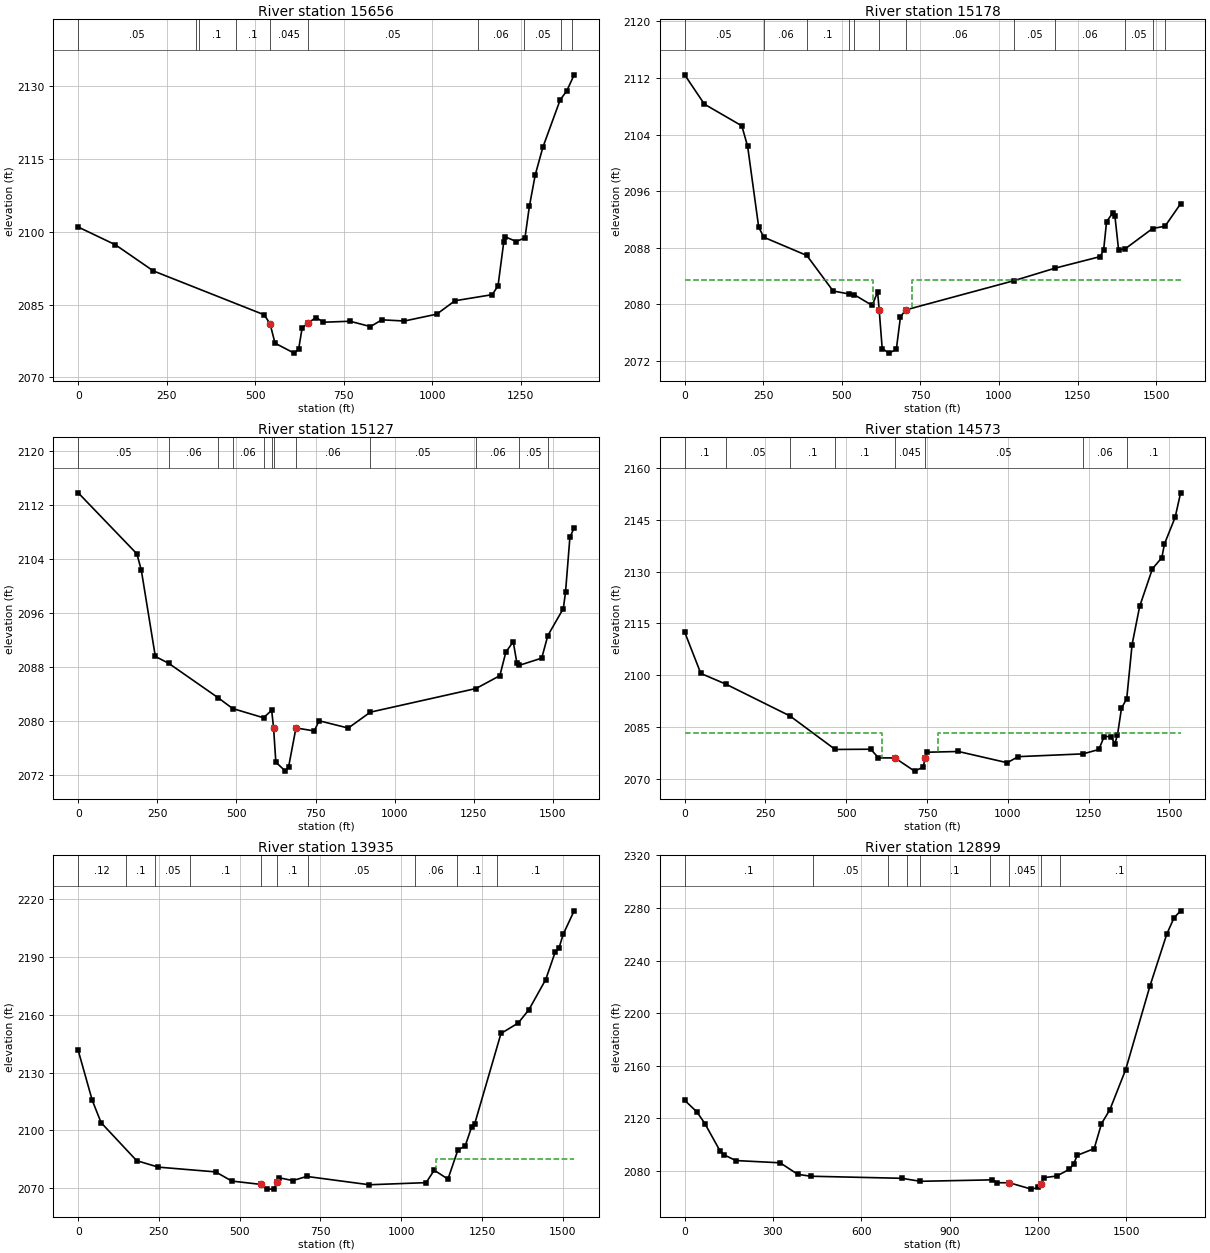
Type RM Length L Ch R = 1 ,15656   ,479.6,477.6,473.1
XS GIS Cut Line= 3
2230095.86091314359009.6061903982229593.77759972359555.439744398
2229189.61075714360076.273020312
#Sta/Elev= 30
       0 2100.96   105.2  2097.3   212.1 2091.93   525.6 2082.89   541.9 2081.04
   555.9 2077.06   609.9 2075.01   622.6 2075.82   632.4 2080.13   649.3 2081.26
   672.2 2082.32   692.8 2081.37   767.8 2081.57   825.5 2080.47   857.6 2081.86
   921.4 2081.62  1012.8 2083.03  1064.2 2085.79  1169.5 2087.04  1185.8 2088.85
  1202.2 2097.95  1205.4 2098.98  1237.3 2097.97    1262 2098.75  1274.4 2105.21
    1291 2111.69  1312.5 2117.37  1361.6 2127.16  1379.9 2128.95  1400.9 2132.28
#Mann= 10 ,-1 , 0
       0     .05       0  331.89      .1       0  340.63      .1       0
   444.8      .1       0   541.9    .045       0   649.3     .05       0
 1129.57     .06       0 1258.94     .05       0 1364.23      .1       0
  1394.7      .1       0
Bank Sta=541.9,649.3
XS Rating Curve= 0 ,0
Exp/Cntr=0.5,0.3

Type RM Length L Ch R = 1 ,15178   ,49.7,50.6,54.5
XS GIS Cut Line= 3
2229749.19592406358612.1102662242229301.97372139359175.998902231
2228793.64042047359867.665825978
#Sta/Elev= 30
       0 2112.45    62.7  2108.3   181.8 2105.23   200.3 2102.33   235.5 2090.89
   251.9 2089.46   388.7 2086.88   472.4 2081.85   522.7 2081.44   538.7 2081.35
   596.8 2079.81   613.9 2081.73     619 2079.14   628.5 2073.71   649.6 2073.06
   673.4 2073.58   686.6 2078.17   702.8 2079.17  1047.5 2083.31  1178.9 2085.09
  1322.1 2086.72  1333.1 2087.65  1342.5 2091.67  1362.8 2092.94    1369 2092.46
  1380.7 2087.69  1401.9 2087.83  1488.7 2090.69  1528.6 2091.03  1578.1  2094.2
#Mann= 12 ,-1 , 0
       0     .05       0   251.9     .06       0   388.7      .1       0
   522.7     .06       0   538.7      .1       0     619    .045       0
   702.8     .06       0  1047.5     .05       0  1178.9     .06       0
  1401.9     .05       0  1488.7      .1       0  1528.6     .05       0
#XS Ineff= 2 , 0
             599  2083.4   722.8          2083.4
Permanent Ineff=
       F       F
Bank Sta=619,702.8
XS Rating Curve= 0 ,0
Exp/Cntr=0.5,0.3

Type RM Length L Ch R = 1 ,15127   ,537.4,554.7,558.8
XS GIS Cut Line= 2
2229727.34852681358594.0492787212228711.48572914 359787.73127456
#Sta/Elev= 30
       0 2113.78   185.5 2104.75   199.5 2102.32   243.7 2089.58   285.8 2088.57
   442.3 2083.47   487.9 2081.88   585.8 2080.51   611.4 2081.62   617.5    2079
   624.6 2073.94   654.9 2072.62   664.9 2073.24   688.2 2079.01   746.1 2078.56
   761.2 2080.07   853.5 2078.99   923.2 2081.34  1257.3 2084.84  1332.6 2086.74
  1351.5 2090.22  1374.8 2091.76  1386.4 2088.62    1394 2088.27  1464.9 2089.33
  1484.2 2092.67  1533.1 2096.66  1540.1 2099.07    1554 2107.22  1567.4 2108.59
#Mann= 12 ,-1 , 0
       0     .05       0   285.8     .06       0   442.3      .1       0
   487.9     .06       0   585.8      .1       0   611.4     .06       0
   617.5    .045       0   688.2     .06       0   923.2     .05       0
  1257.3     .06       0    1394     .05       0  1484.2      .1       0
Bank Sta=617.5,688.2
XS Rating Curve= 0 ,0
Exp/Cntr=0.5,0.3

Type RM Length L Ch R = 1 ,14573   ,649.3,637.6,625
XS GIS Cut Line= 2
 2229420.8609508358334.6062280542228210.44408031359278.356309056
#Sta/Elev= 30
       0 2112.49    49.9 2100.53   127.1 2097.45   325.8 2088.23   465.8 2078.53
   575.9  2078.6   599.8 2076.09   650.7 2076.08   711.5 2072.26   738.5 2073.44
   743.8 2076.04   748.9 2077.73   847.1 2077.94   998.3 2074.69    1032 2076.45
  1232.8 2077.25  1281.9 2078.52  1298.2 2082.28  1319.3 2082.26  1331.1 2080.19
  1339.4 2082.64  1351.9 2090.46  1368.1 2093.22  1384.7 2108.89  1408.1 2119.91
  1447.6 2130.81  1476.7 2134.03    1485 2138.03    1518 2145.71  1534.9 2152.79
#Mann= 8 ,-1 , 0
       0      .1       0   127.1     .05       0   325.8      .1       0
   465.8      .1       0   650.7    .045       0   743.8     .05       0
  1232.8     .06       0  1368.1      .1       0
#XS Ineff= 2 , 0
           610.7  2083.4   784.8          2083.4
Permanent Ineff=
       F       F
Bank Sta=650.7,743.8
XS Rating Curve= 0 ,0
Exp/Cntr=0.3,0.1

Type RM Length L Ch R = 1 ,13935   ,967.9,1035.9,1026.4
XS GIS Cut Line= 3
 2228737.5276718357870.0228396512228345.86080422358463.772964478
2227885.44440222359147.106243476
#Sta/Elev= 30
       0  2141.4    43.3 2115.68    70.8 2104.04   180.8 2084.37   247.9 2081.01
   425.5 2078.54   475.6 2073.79   565.3 2072.07   584.2 2069.62   605.5 2069.64
     615 2073.11     621 2075.54   664.3 2074.05   707.5 2076.19   901.3 2071.88
  1077.1 2072.98  1102.1 2079.43  1144.6  2074.8  1175.3 2089.85    1198    2092
  1217.8 2101.74  1227.3 2103.39  1308.8 2150.23  1362.1 2155.62  1395.2 2162.51
  1447.3 2178.15  1476.3 2192.21  1488.1 2194.31  1501.5 2201.63  1535.3 2213.72
#Mann= 10 ,-1 , 0
       0     .12       0  149.39      .1       0  238.52     .05       0
  347.37      .1       0   565.3    .045       0     615      .1       0
  710.96     .05       0 1041.99     .06       0 1171.23      .1       0
 1297.83      .1       0
#XS Ineff= 2 , 0
                         1107.41         2085.33
Permanent Ineff=
       F       F
Bank Sta=565.3,615
XS Rating Curve= 0 ,0
Exp/Cntr=0.3,0.1

Type RM Length L Ch R = 1 ,12899   ,630.2,622.8,626.2
XS GIS Cut Line= 2
2228366.69409589357574.1897698942227350.02749406358917.939707056
#Sta/Elev= 30
       0 2133.77    41.8 2124.88    68.8 2116.02   120.1 2095.31   133.1 2092.43
   173.5    2088   324.4 2086.28   384.2 2077.51   428.2 2076.08   737.4 2074.51
   800.6 2072.23  1045.7 2073.33  1062.2 2071.13  1102.7 2071.14  1177.7 2066.28
  1202.1 2067.53    1209 2070.46  1219.8 2074.96  1263.8 2076.22  1306.5 2081.27
  1321.4 2085.27  1333.7 2091.98  1391.3 2097.03    1416 2115.93  1444.7 2126.68
  1498.3 2157.07  1580.5 2220.43  1638.1 2260.13  1662.8 2272.54    1685 2277.76
#Mann= 9 ,-1 , 0
       0      .1       0  437.06     .05       0  692.05      .1       0
  756.48     .12       0  797.91      .1       0 1037.03      .1       0
  1102.7    .045       0    1209     .06       0 1273.81      .1       0
Bank Sta=1102.7,1209
XS Rating Curve= 0 ,0
Exp/Cntr=0.3,0.1

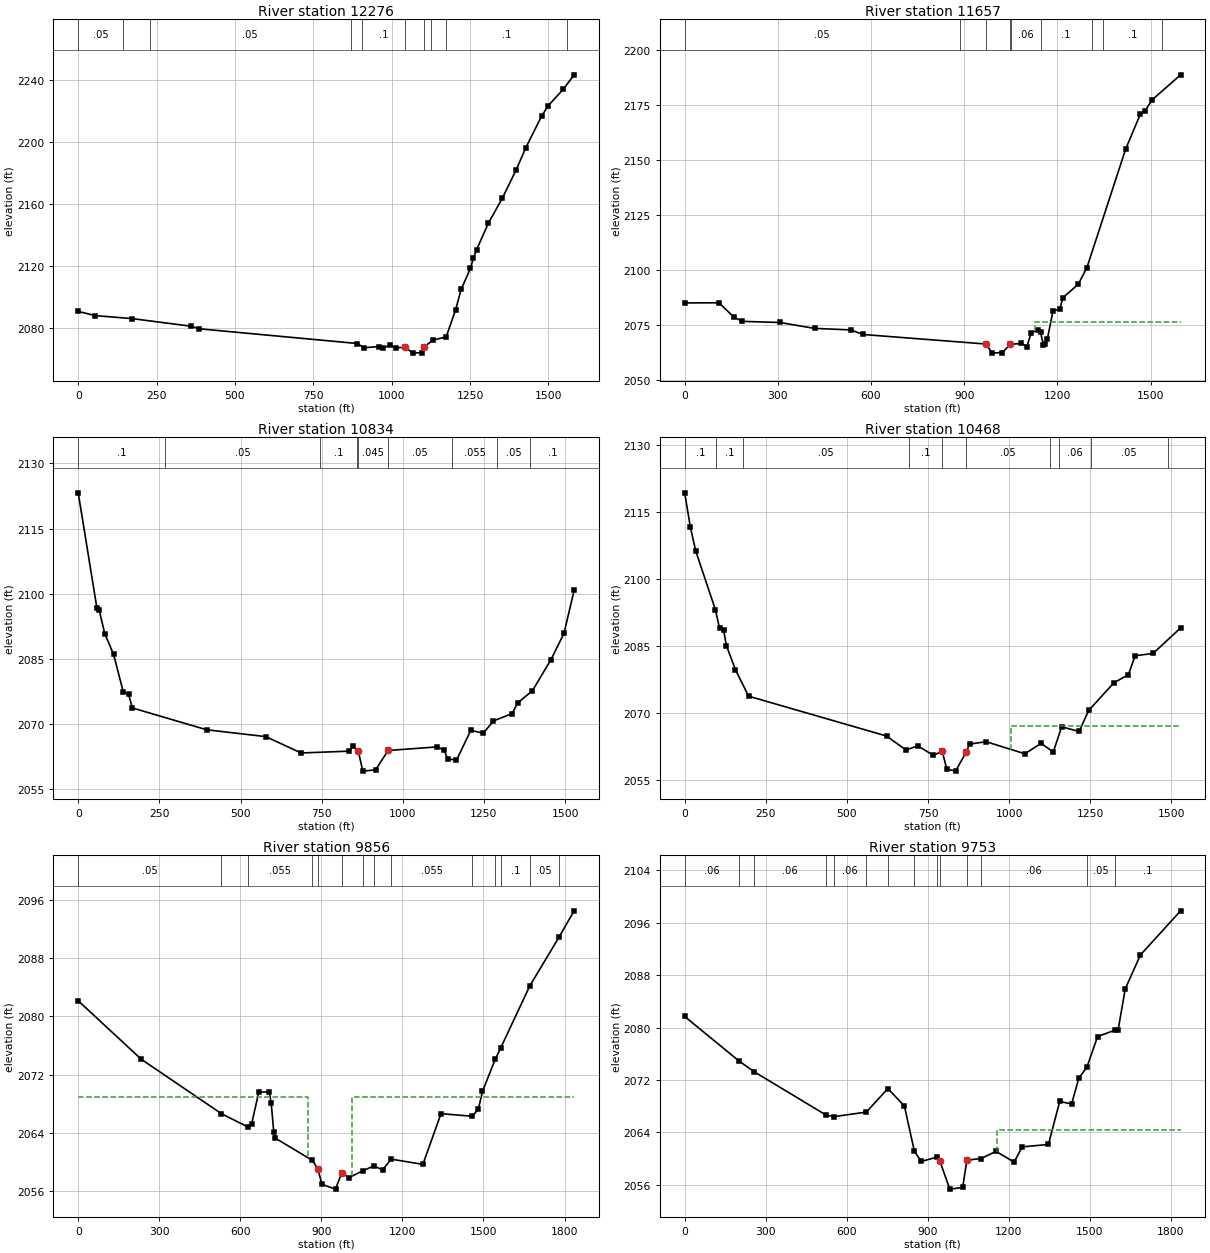
Type RM Length L Ch R = 1 ,12276   ,616.4,619.2,624
XS GIS Cut Line= 2
2227833.36084497357407.5231084822226783.36097647358590.856371731
#Sta/Elev= 30
       0 2090.78    54.8 2088.09   172.1 2086.16   359.6 2081.25     386 2079.59
   890.3  2070.1   911.2 2067.34     960 2068.15   973.7 2067.21     994 2069.04
  1013.8 2067.42  1043.5 2067.55  1068.2 2063.89  1096.5 2064.24  1104.1  2068.1
  1132.4 2072.33  1173.8 2074.36    1204 2091.93  1221.4 2104.95  1251.1 2118.53
  1260.9 2125.39  1270.8  2130.6  1308.6 2147.81  1352.8 2163.78  1397.3 2182.26
  1427.1 2196.07  1478.4 2216.86  1499.2 2223.48  1547.7 2234.22    1582 2243.42
#Mann= 10 ,-1 , 0
       0     .05       0  141.27      .1       0  227.99     .05       0
  868.87      .1       0   906.7      .1       0  1043.5    .045       0
  1104.1    .055       0 1125.22     .06       0 1174.02      .1       0
 1559.96      .1       0
Bank Sta=1043.5,1104.1
XS Rating Curve= 0 ,0
Exp/Cntr=0.3,0.1

Type RM Length L Ch R = 1 ,11657   ,818.4,823.4,823.8
XS GIS Cut Line= 2
2227483.36088881357078.3564439712226275.02767555358122.106324971
#Sta/Elev= 30
       0 2084.86   110.2 2084.92   157.8  2078.5   185.4 2076.48   306.4 2075.96
   418.1 2073.28     535 2072.59   573.7 2070.51   970.2 2066.17   990.2 2062.03
  1022.8 2062.31  1048.4 2066.01  1083.3 2066.44  1101.9 2065.03  1115.9  2071.4
  1137.6 2072.48  1145.9 2071.43    1155 2065.75    1161 2066.11    1168 2068.67
    1186 2081.35    1207 2081.91  1218.2 2087.29  1267.1 2093.36    1295 2100.91
  1419.4 2154.67  1467.1 2170.72  1482.2 2172.29  1506.1 2177.36  1596.7 2188.58
#Mann= 9 ,-1 , 0
       0     .05       0  886.13      .1       0   970.2    .045       0
  1048.4      .1       0 1051.91     .06       0 1146.56      .1       0
 1310.04      .1       0 1346.38      .1       0 1537.17      .1       0
#XS Ineff= 2 , 0
                         1127.33         2076.01
Permanent Ineff=
       F       F
Bank Sta=970.2,1048.4
XS Rating Curve= 0 ,0
Exp/Cntr=0.3,0.1

Type RM Length L Ch R = 1 ,10834   ,377.9,365.4,356.2
XS GIS Cut Line= 2
2227302.11092322356488.7729774712226004.19422773357295.023005396
#Sta/Elev= 30
       0 2123.24    57.6 2096.71    64.8 2096.19    81.7 2090.84   108.8 2086.08
   138.6 2077.48   155.1 2076.86   166.7 2073.71   395.9 2068.68   578.4  2067.1
   686.6 2063.34   834.9 2063.76   846.5 2064.86   862.9 2063.77   876.8 2059.16
     916 2059.44   954.6 2063.91  1105.9 2064.74  1127.3    2064  1137.9 2062.01
  1165.4 2061.68  1209.5 2068.56  1248.2  2067.9  1279.1 2070.72    1337 2072.41
  1353.6 2074.86  1399.1 2077.65  1456.1 2084.77  1496.6 2090.89  1527.9 2100.83
#Mann= 9 ,-1 , 0
       0      .1       0  266.44     .05       0  744.83      .1       0
  858.81      .1       0   862.9    .045       0   954.6     .05       0
 1152.38    .055       0 1289.27     .05       0 1393.12      .1       0
Bank Sta=862.9,954.6
XS Rating Curve= 0 ,0
Exp/Cntr=0.3,0.1

Type RM Length L Ch R = 1 ,10468   ,663.3,612.5,542.5
XS GIS Cut Line= 3
2226895.86075147355999.1896390622226139.61095163356915.856440887
2226033.36083606357238.772789806
#Sta/Elev= 30
       0  2119.2    17.2 2111.64      34 2106.19    94.6 2093.03   107.4 2088.89
   120.1 2088.39   128.6    2085   156.4 2079.58   197.1 2073.66     622 2064.74
   681.9 2061.62   718.4 2062.54   765.8 2060.44   793.7 2061.29   807.7 2057.35
   834.7 2056.88   868.3 2061.24   878.2 2062.94   928.9 2063.47  1048.3 2060.77
  1098.4 2063.09  1135.9 2061.17  1161.7  2066.8  1215.4 2065.76    1245 2070.46
  1322.5 2076.65  1367.4 2078.48  1388.1 2082.72  1443.4 2083.23  1528.3 2088.95
#Mann= 10 ,-1 , 0
       0      .1       0   96.79      .1       0  181.04     .05       0
  689.94      .1       0   793.7    .045       0   868.3     .05       0
 1126.17    .055       0 1153.89     .06       0 1251.47     .05       0
 1488.44      .1       0
#XS Ineff= 2 , 0
                          1006.9         2067.06
Permanent Ineff=
       F       F
Bank Sta=793.7,868.3
XS Rating Curve= 0 ,0
Exp/Cntr=0.5,0.3

Type RM Length L Ch R = 1 ,9856    ,105.2,102.8,106.4
XS GIS Cut Line= 6
2225864.61084548355507.5229714812225812.52761631356211.689542145
2225860.44418713356342.9396077252226075.02741939356645.022993058
 2226104.1943558356826.2729586362226006.27755688357249.189763725
#Sta/Elev= 30
       0 2082.14   233.9 2074.09     530 2066.63   629.1 2064.78   641.9 2065.23
   668.2 2069.56     707 2069.65   714.3 2068.08   723.9 2064.05     730 2063.25
   867.1  2060.2     887 2059.03     902 2056.92   952.3 2056.26   975.4 2058.51
    1002 2057.84  1053.2 2058.77  1093.7 2059.45  1126.6  2058.9  1158.4 2060.38
  1275.7 2059.66  1342.8 2066.63  1458.9 2066.27  1481.3 2067.29  1496.3 2069.68
  1543.4 2074.09  1564.1 2075.69  1671.4 2084.18  1778.8 2090.84  1835.6  2094.5
#Mann= 14 ,-1 , 0
       0     .05       0     530     .06       0   629.1    .055       0
   867.1     .05       0     887    .045       0   975.4    .035       0
  1053.2     .06       0  1093.7     .05       0  1158.4    .055       0
  1458.9     .06       0  1543.4     .05       0  1564.1      .1       0
  1671.4     .05       0  1778.8      .1       0
#XS Ineff= 2 , 0
             849 2068.96  1013.4         2068.96
Permanent Ineff=
       F       F
Bank Sta=887,975.4
XS Rating Curve= 0 ,0
Exp/Cntr=0.5,0.3

Type RM Length L Ch R = 1 ,9753    ,76.4,102.2,99.6
XS GIS Cut Line= 6
2225791.69432464355511.6896298082225689.61086738356228.356175482
2225745.86075489  356376.27287442225962.52764438356653.356309727
2226027.11084856356838.7729336472225989.61092356357240.856447056
#Sta/Elev= 30
       0  2081.7   201.6 2074.89   257.9 2073.25   523.1 2066.66   552.8 2066.41
   672.6  2067.1   752.7 2070.69     814 2068.02   850.9 2061.11   876.3 2059.57
   935.3 2060.23   944.6  2059.7   981.9 2055.34  1029.7 2055.59  1045.3 2059.76
  1097.6 2060.01    1153  2061.1  1220.4 2059.47  1250.2 2061.79  1347.3 2062.16
  1389.2 2068.73  1433.2 2068.34  1459.9 2072.28  1490.1 2073.97  1529.3 2078.63
  1592.6 2079.59  1605.6 2079.67    1632 2085.92    1688 2091.09    1837 2097.83
#Mann= 14 ,-1 , 0
       0     .06       0   201.6      .1       0   257.9     .06       0
   523.1     .05       0   552.8     .06       0   672.6    .055       0
   752.7     .06       0   850.9      .1       0   935.3    .055       0
   944.6    .045       0  1045.3    .055       0  1097.6     .06       0
  1490.1     .05       0  1592.6      .1       0
#XS Ineff= 2 , 0
                         1155.13         2064.32
Permanent Ineff=
       F       F
Bank Sta=944.6,1045.3
XS Rating Curve= 0 ,0
Exp/Cntr=0.5,0.3

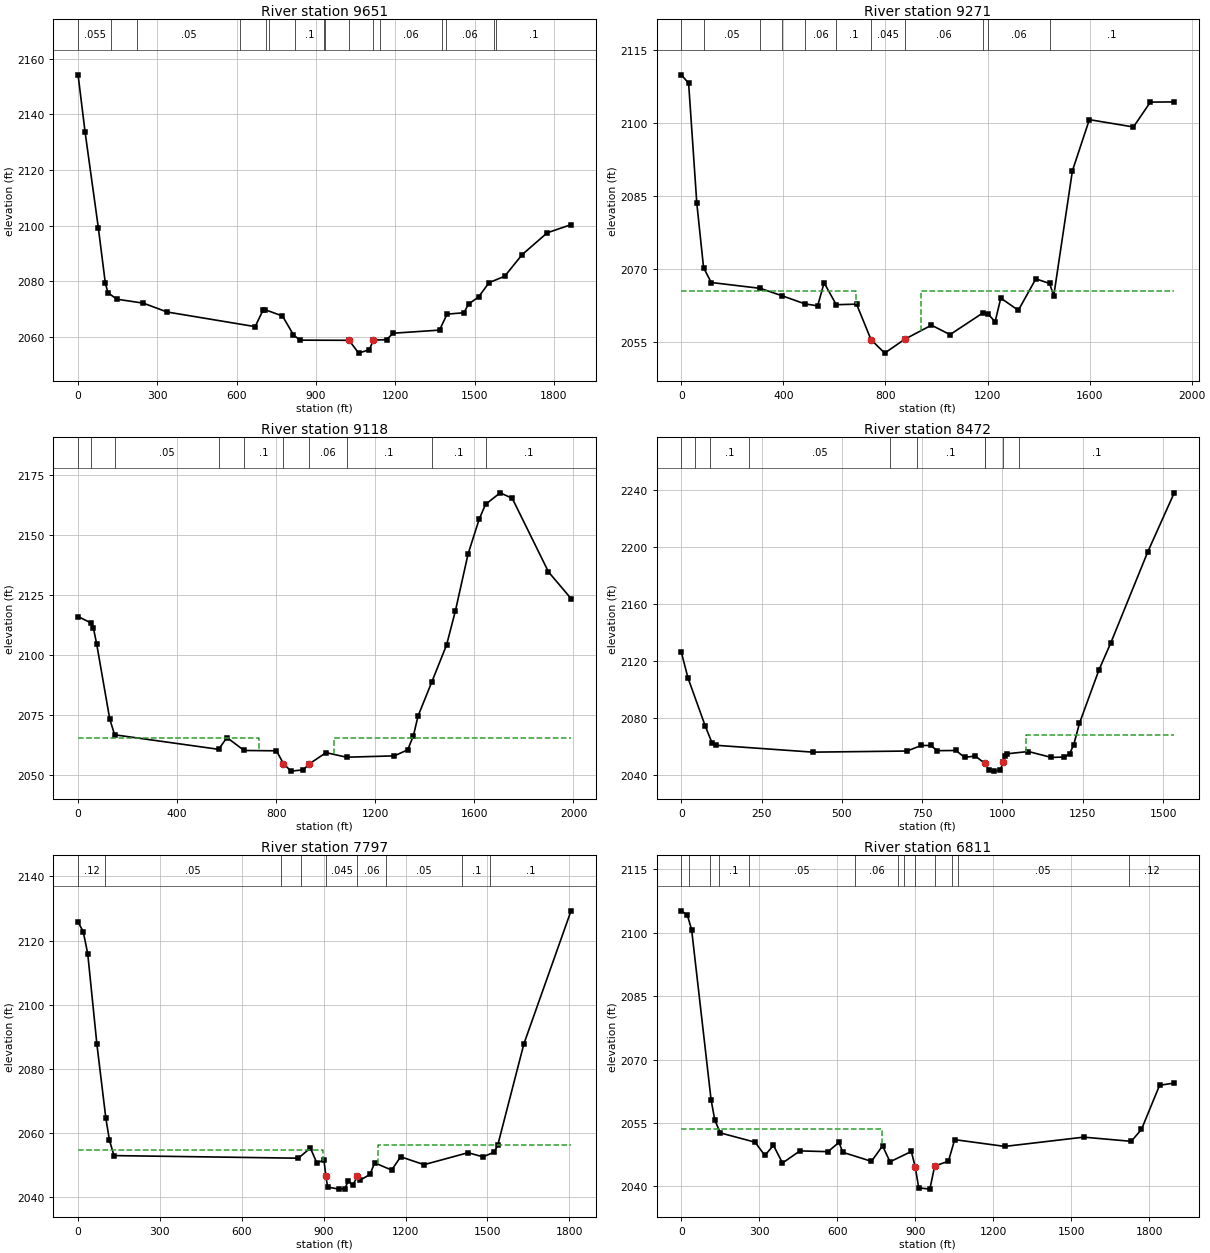
Type RM Length L Ch R = 1 ,9651    ,402.4,379.7,344.2
XS GIS Cut Line= 6
2225416.69409038355478.3563631482225543.77749763356186.689592138
2225760.44438714356524.189573318 2225903.5864893356655.786751062
2225957.40593547356780.7868291442225976.50333822357192.245323807
#Sta/Elev= 30
       0 2154.26    26.6 2133.65    76.6 2099.29   103.3 2079.21   113.3 2075.85
   146.6 2073.55   247.3 2072.11   336.6 2068.94     670 2063.67     700 2069.65
   706.6  2069.8   773.4 2067.49   814.5 2060.78   838.5 2058.81  1025.3 2058.75
  1061.6 2054.14  1101.6 2055.36  1117.6 2058.82  1167.3 2058.98  1191.5  2061.3
  1367.4 2062.42    1396 2068.17  1459.7 2068.66  1477.3 2071.78  1515.6 2074.39
    1555  2079.5  1614.1  2081.8  1679.8 2089.55    1775 2097.43    1865 2100.35
#Mann= 16 ,-1 , 0
       0    .055       0  125.08      .1       0  222.63     .05       0
  612.79    .055       0  710.34      .1       0  721.05     .06       0
  819.66      .1       0  930.22     .06       0  934.38      .1       0
  1025.3    .045       0  1117.6    .055       0 1140.43     .06       0
 1375.82      .1       0 1393.44     .06       0    1574     .05       0
 1580.26      .1       0
Bank Sta=1025.3,1117.6
XS Rating Curve= 0 ,0
Exp/Cntr=0.5,0.3

Type RM Length L Ch R = 1 ,9271    ,151.2,152.6,176.8
XS GIS Cut Line= 6
2225216.69416231355549.1895548112225306.27764456356205.439554647
 2225470.8609768356357.5229118912225816.69427463356620.023043066
 2225881.2774788356697.1062222272225960.44431522357201.272864804
#Sta/Elev= 30
       0 2109.92    28.8 2108.21    60.9 2083.54    87.4 2070.33   117.2 2067.28
   309.3 2066.08   395.4 2064.55   484.8 2062.89   534.5 2062.49   559.6 2067.23
   607.3 2062.72   686.8 2062.84   743.5 2055.54   797.1 2052.78   874.9 2055.61
   980.3 2058.52    1053 2056.58  1181.4 2061.02  1202.7  2060.8  1229.6  2059.2
  1251.9 2064.08  1320.7 2061.57  1389.2 2068.03  1443.3 2067.08  1459.4 2064.53
  1532.5 2090.21  1598.9 2100.72  1771.6 2099.21    1838 2104.32  1931.5 2104.36
#Mann= 11 ,-1 , 0
       0    .055       0    87.4     .05       0   309.3    .055       0
   395.4     .05       0   484.8     .06       0   607.3      .1       0
   743.5    .045       0   874.9     .06       0  1181.4    .055       0
  1202.7     .06       0  1443.3      .1       0
#XS Ineff= 2 , 0
           683.5  2065.5   939.5          2065.5
Permanent Ineff=
       F       F
Bank Sta=743.5,874.9
XS Rating Curve= 0 ,0
Exp/Cntr=0.5,0.3

Type RM Length L Ch R = 1 ,9118    ,598,646.6,680.8
XS GIS Cut Line= 6
2225183.36089563355499.1896548122225100.02772897356172.106287971
2225302.11098622356361.6895702332225422.94407789356442.939735815
2225585.44408096356590.8564347332225889.61079547357186.689560637
#Sta/Elev= 30
       0 2116.15      53 2113.42    61.8 2111.36    74.9 2104.85   127.8 2073.48
   147.6 2066.86   567.4 2060.81     601  2065.7   670.7 2060.32     801 2060.19
   829.3 2054.81   859.8 2051.72   909.5 2052.26   932.1 2054.64  1001.2 2059.42
  1084.1 2057.52  1276.9 2058.08  1330.9 2060.61    1354 2066.54  1372.6 2074.69
  1427.7 2088.78  1487.8 2104.31  1523.5 2118.56  1574.3 2142.11  1619.2 2156.67
    1645 2162.88  1704.1 2167.69  1752.8 2165.41  1899.2 2134.73  1990.2 2123.64
#Mann= 10 ,-1 , 0
       0      .1       0      53    .055       0   147.6     .05       0
   567.4     .06       0   670.7      .1       0   829.3    .045       0
   932.1     .06       0  1084.1      .1       0  1427.7      .1       0
    1645      .1       0
#XS Ineff= 2 , 0
           729.3  2065.5  1032.1          2065.5
Permanent Ineff=
       F       F
Bank Sta=829.3,932.1
XS Rating Curve= 0 ,0
Exp/Cntr=0.5,0.3

Type RM Length L Ch R = 1 ,8472    ,676.6,674.5,671.7
XS GIS Cut Line= 2
2224848.78348081355401.9674083142224487.67232639356893.634044394
#Sta/Elev= 30
       0 2126.32    20.8 2108.18    75.1  2074.1    95.5 2062.69     109 2060.83
   409.5 2056.03     703 2056.81   746.9 2060.71   776.4 2060.71   797.6 2057.06
     855  2057.2     882 2052.38   915.7 2053.29   944.8 2048.16   959.6 2043.32
   973.1 2042.71   993.4 2043.41  1001.6 2048.96  1006.9 2053.21  1013.6 2054.87
  1080.7 2056.47    1152 2052.34  1192.5 2052.59  1209.4 2055.02  1222.1 2061.38
  1239.8 2076.34  1300.5 2113.76  1337.7 2132.92  1452.4 2196.57  1534.8 2237.99
#Mann= 10 ,-1 , 0
       0      .1       0   43.66      .1       0   90.27      .1       0
   209.5     .05       0  651.39     .06       0  733.59      .1       0
  944.62     .06       0   944.8    .045       0  1001.6     .06       0
 1050.14      .1       0
#XS Ineff= 2 , 0
                         1073.01         2068.15
Permanent Ineff=
       F       F
Bank Sta=944.8,1001.6
XS Rating Curve= 0 ,0
Exp/Cntr=0.3,0.1

Type RM Length L Ch R = 1 ,7797    ,953.8,986.7,984
XS GIS Cut Line= 4
 2224096.0054588355318.6339135622223940.44999564356363.078346983
2223937.67211406356418.6340101512224004.33897547357110.300605804
#Sta/Elev= 30
       0 2125.75    18.8 2122.82    35.4  2115.9    69.1 2087.55   101.8  2064.5
     115 2057.66   131.6 2052.85   807.3 2052.04   851.4 2055.22   874.6 2050.62
   901.2 2051.39   907.8 2046.63   914.4 2043.01   957.8 2042.38   977.5 2042.53
   990.7 2045.01  1007.3 2043.57  1023.2  2046.5  1033.8  2045.2  1070.2 2046.99
  1086.6  2050.6  1149.2 2048.33  1182.1 2052.48  1267.8 2050.02  1429.2 2053.75
  1483.5 2052.47  1524.9  2053.9  1538.1 2056.18  1633.8 2087.75  1806.5 2129.28
#Mann= 9 ,-1 , 0
       0     .12       0  100.52     .05       0   742.5     .06       0
  815.55      .1       0   907.8    .045       0  1023.2     .06       0
 1129.03     .05       0 1407.67      .1       0  1510.9      .1       0
#XS Ineff= 2 , 0
          896.43 2054.45 1100.17         2056.08
Permanent Ineff=
       F       F
Bank Sta=907.8,1023.2
XS Rating Curve= 0 ,0
Exp/Cntr=0.3,0.1

Type RM Length L Ch R = 1 ,6811    ,786.2,786.1,784.7
XS GIS Cut Line= 3
2223529.33894122355182.5229653122223107.11668855 356176.96749872
 2222751.5612973356910.300677732
#Sta/Elev= 30
       0 2105.16    23.5 2104.14    39.8  2100.7   114.6 2060.52   128.9 2055.68
   150.3 2052.65   283.7 2050.46   321.4 2047.32   354.4 2049.72   389.1 2045.53
   456.3  2048.4   563.9 2048.22   606.5 2050.41   620.8 2048.07   731.3 2045.93
   773.9 2049.59   802.6 2045.82   884.5 2048.26   899.2 2044.68     913 2039.66
   955.8 2039.36   974.2 2044.82  1027.1 2045.96  1051.2 2051.06  1243.9 2049.46
  1547.3 2051.65  1730.1 2050.66  1769.4 2053.49    1839 2063.92  1895.3 2064.43
#Mann= 13 ,-1 , 0
       0      .1       0   29.51      .1       0   110.5      .1       0
  144.32      .1       0  259.13     .05       0  669.38     .06       0
  833.16      .1       0  855.68      .1       0   899.2    .045       0
   974.2      .1       0 1041.97      .1       0 1062.77     .05       0
 1720.13     .12       0
#XS Ineff= 2 , 0
          771.93 2053.62
Permanent Ineff=
       F       F
Bank Sta=899.2,974.2
XS Rating Curve= 0 ,0
Exp/Cntr=0.3,0.1

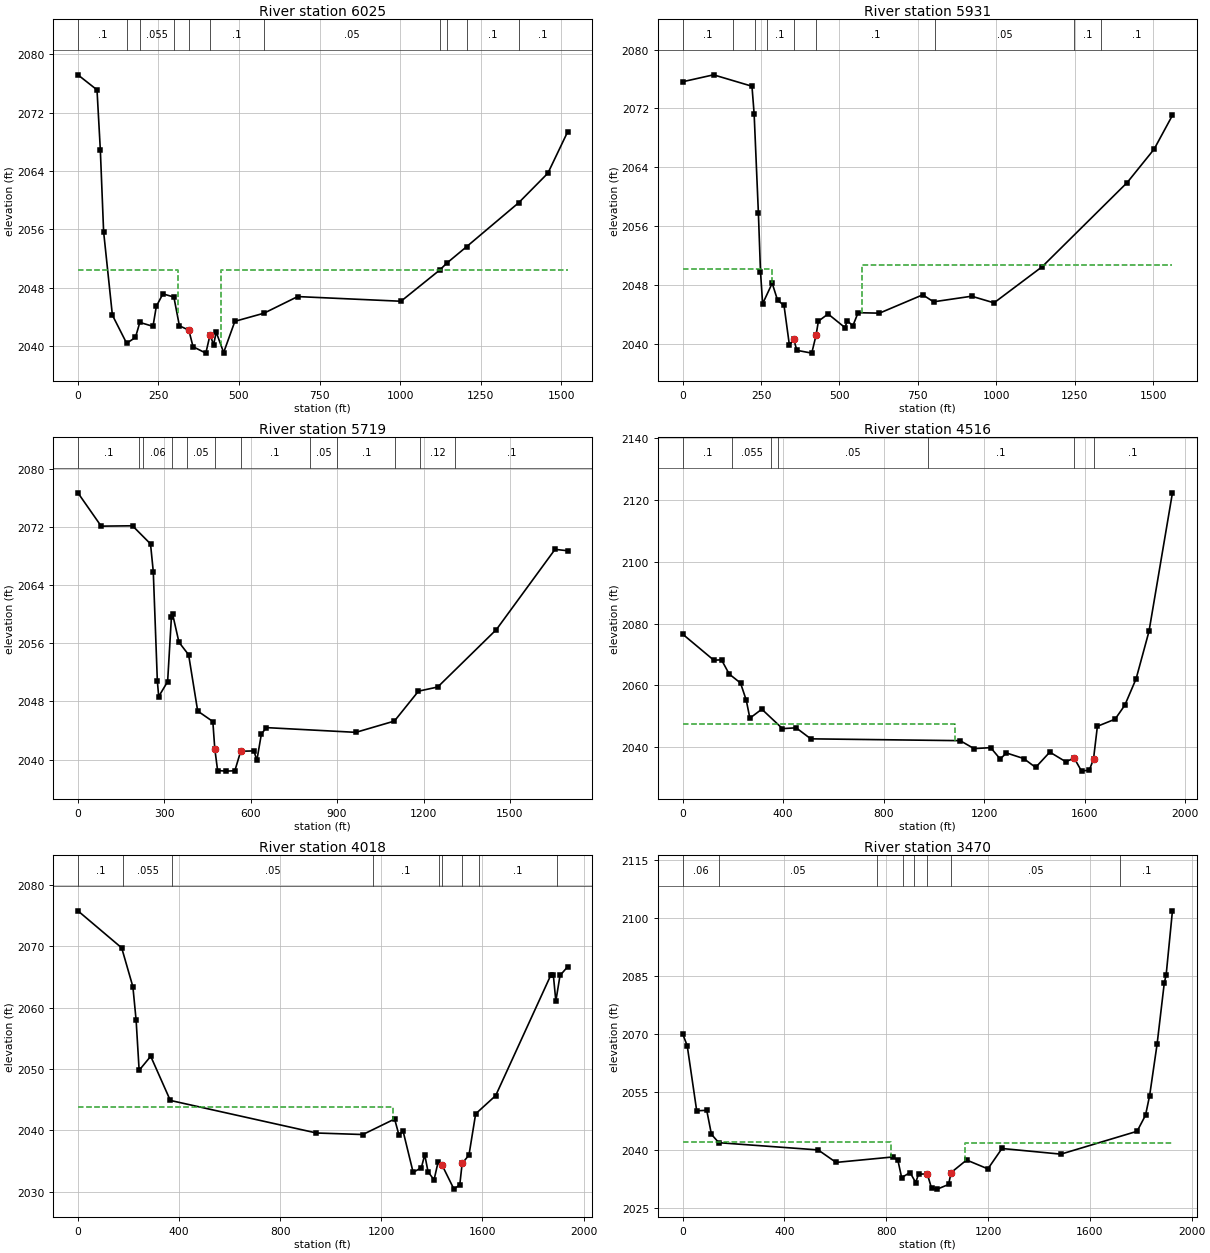
Type RM Length L Ch R = 1 ,6025    ,101,93.1,88.9
XS GIS Cut Line= 5
2222555.42291005355381.8509787322222470.70063855355683.239811644
2222424.52714538355798.2247866342222333.33567635356063.573965637
2222082.29101899356826.184838725
#Sta/Elev= 30
       0 2077.17    59.3 2075.11    69.6  2066.9    79.8 2055.67     107 2044.24
   151.3 2040.38   178.6 2041.18   192.2 2043.24   233.1  2042.7   243.4 2045.44
   263.8 2047.15   297.9 2046.72     315 2042.78   344.42042.172   357.4 2039.91
   397.1 2039.03   410.42041.573   421.1 2040.15   429.3 2041.91   452.4 2039.11
   487.3 2043.39   577.5  2044.5   682.2 2046.78  1002.9 2046.14  1123.8 2050.44
  1144.5 2051.34  1206.4 2053.61    1368 2059.63  1458.9 2063.69  1520.4 2069.37
#Mann= 11 ,-1 , 0
       0      .1       0   151.3     .06       0   192.2    .055       0
   297.9      .1       0   344.4    .045       0   410.4      .1       0
   577.5     .05       0  1123.8      .1       0  1144.5     .05       0
  1206.4      .1       0    1368      .1       0
#XS Ineff= 2 , 0
           309.4 2050.37   445.4         2050.37
Permanent Ineff=
       F       F
Bank Sta=344.4,410.4
XS Rating Curve= 0 ,0
Exp/Cntr=0.3,0.1

Type RM Length L Ch R = 1 ,5931    ,216.7,213,204.4
XS GIS Cut Line= 6
2222471.00329553355328.2445111632222451.67962258355392.270301676
2222429.67874142355465.6065722182222393.22769639 355603.35644123
2222354.33899464355733.9119543882222021.07096039356823.610234305
#Sta/Elev= 30
       0 2075.62    98.5 2076.56     221 2075.01   227.9 2071.27   241.5 2057.76
   248.2 2049.81     255 2045.47   285.5 2048.25   302.7 2045.94   323.2 2045.23
   340.3 2039.86     354 2040.63   364.3 2039.14   411.6 2038.76   425.3 2041.18
   432.8  2043.1   463.7 2044.08   517.2 2042.24   525.4 2043.15   542.6 2042.46
   559.3 2044.25   627.6 2044.19   765.6 2046.68   799.9 2045.73   921.4 2046.49
   992.8 2045.59  1146.4  2050.5  1417.4 2061.93  1503.2 2066.46  1561.7 2071.06
#Mann= 9 ,-1 , 0
       0      .1       0   159.8     .06       0   230.7    .055       0
   268.1      .1       0     354    .045       0   425.3      .1       0
   804.8     .05       0  1247.3      .1       0    1334      .1       0
#XS Ineff= 2 , 0
          284.49  2050.2  570.88          2050.7
Permanent Ineff=
       F       F
Bank Sta=354,425.3
XS Rating Curve= 0 ,0
Exp/Cntr=0.3,0.1

Type RM Length L Ch R = 1 ,5719    ,1173,1202.2,1208.2
XS GIS Cut Line= 4
2222447.08946531355247.1288072322222190.83964972355486.711989477
2222140.83942163355805.4620081482221945.00615188356813.795293316
#Sta/Elev= 30
       0 2076.67    80.8 2072.09   189.6 2072.14   252.1 2069.65   261.7 2065.85
   275.8 2050.83   280.5 2048.67   311.5 2050.72   324.6 2059.55   328.9 2059.99
   350.8 2056.14   384.4 2054.41   415.9 2046.68   468.5 2045.24   475.2 2041.52
   485.1  2038.5     515 2038.42   544.9 2038.47   565.2 2041.15   611.2  2041.2
   621.3 2039.89     637 2043.52   654.5  2044.4   965.2 2043.75  1098.9  2045.3
  1182.4 2049.41  1249.3 2049.98  1453.1 2057.88  1656.6  2068.9  1700.6 2068.71
#Mann= 12 ,-1 , 0
       0      .1       0  212.44    .055       0  227.05     .06       0
  326.99      .1       0  380.11     .05       0   475.2    .045       0
   565.2      .1       0  804.71     .05       0  900.68      .1       0
 1102.15     .05       0 1188.25     .12       0 1309.49      .1       0
Bank Sta=475.2,565.2
XS Rating Curve= 0 ,0
Exp/Cntr=0.3,0.1

Type RM Length L Ch R = 1 ,4516    ,448.7,498.7,508.1
XS GIS Cut Line= 4
2222423.78340955 355238.078628482221201.56111647356013.078390807
 2221021.0057033356204.7453303042220896.00562522 356407.52281189
#Sta/Elev= 30
       0 2076.57   123.9 2068.15   154.6 2068.26   185.2 2063.67   230.2 2060.77
   253.1  2055.2   267.4 2049.39   314.9 2052.31   397.2 2046.02   451.6 2046.28
   509.8 2042.72  1104.2 2042.13  1159.3 2039.56  1225.5 2039.87  1263.5 2036.19
    1288 2038.16  1356.8 2036.35  1404.4 2033.48  1460.8 2038.43  1523.9 2035.33
    1558 2036.46    1587 2032.28  1618.1 2032.62  1634.6 2036.17  1650.1 2046.78
  1720.5 2049.08  1759.1 2053.58  1804.2 2062.16  1855.4 2077.48  1948.7 2122.26
#Mann= 7 ,-1 , 0
       0      .1       0  197.88    .055       0  351.27      .1       0
  379.94     .05       0  976.47      .1       0    1558    .045       0
  1634.6      .1       0
#XS Ineff= 2 , 0
         1083.19 2047.59
Permanent Ineff=
       F       F
Bank Sta=1558,1634.6
XS Rating Curve= 0 ,0
Exp/Cntr=0.3,0.1

Type RM Length L Ch R = 1 ,4018    ,552.9,547.7,518.9
XS GIS Cut Line= 3
2222379.33894464355221.4119951432221276.56129456355654.745117977
2220529.33903572355743.634047806
#Sta/Elev= 30
       0 2075.78   173.2 2069.74   217.5  2063.4   230.3 2057.93   242.2 2049.78
     288 2052.07   365.5 2044.87   943.7 2039.56    1127 2039.31  1252.8 2041.84
  1269.9 2039.23  1285.9 2039.93    1326 2033.15  1358.6  2033.9  1371.8 2036.03
    1385 2033.25  1408.7 2031.91  1424.6  2034.8  1441.1 2034.28  1487.4 2030.41
  1510.5 2031.11  1519.9 2034.59  1546.9 2035.97  1573.3 2042.68  1652.6 2045.66
  1870.7  2065.3  1880.6 2065.31  1890.5 2061.06    1907 2065.24  1937.4 2066.67
#Mann= 9 ,-1 , 0
       0      .1       0  177.26    .055       0  373.85     .05       0
 1167.28      .1       0 1427.85      .1       0  1441.1    .045       0
  1519.9      .1       0 1585.86      .1       0 1895.21      .1       0
#XS Ineff= 2 , 0
         1246.18 2043.76
Permanent Ineff=
       F       F
Bank Sta=1441.1,1519.9
XS Rating Curve= 0 ,0
Exp/Cntr=0.3,0.1

Type RM Length L Ch R = 1 ,3470    ,599.8,603.4,602.6
XS GIS Cut Line= 3
2221854.33901039354701.9674959782220818.22789364355229.745311812
2220140.45004971355576.967386395
#Sta/Elev= 30
       0  2070.1    17.9 2067.03    55.2 2050.19    94.6 2050.32     113 2044.12
     142 2041.94   532.3 2040.07   602.7 2036.84   827.3 2038.26   845.7 2037.36
   860.4 2032.92   893.5 2034.22   915.5 2031.64   926.7 2033.78   960.9  2033.9
   978.2  2030.1  1000.3 2029.93  1044.8 2031.14  1054.6 2034.21  1115.6 2037.46
  1199.2 2035.17  1254.5 2040.44  1486.1 2038.98  1785.3 2044.89  1818.5 2049.04
  1834.7 2054.14  1863.9 2067.39  1892.2 2083.24  1899.6 2085.37  1924.3 2101.92
#Mann= 8 ,-1 , 0
       0     .06       0  143.38     .05       0  764.31      .1       0
  866.94      .1       0  909.78     .05       0   960.9    .045       0
  1054.6     .05       0 1718.62      .1       0
#XS Ineff= 2 , 0
          819.47 2042.16 1109.22         2041.93
Permanent Ineff=
       F       F
Bank Sta=960.9,1054.6
XS Rating Curve= 0 ,0
Exp/Cntr=0.3,0.1