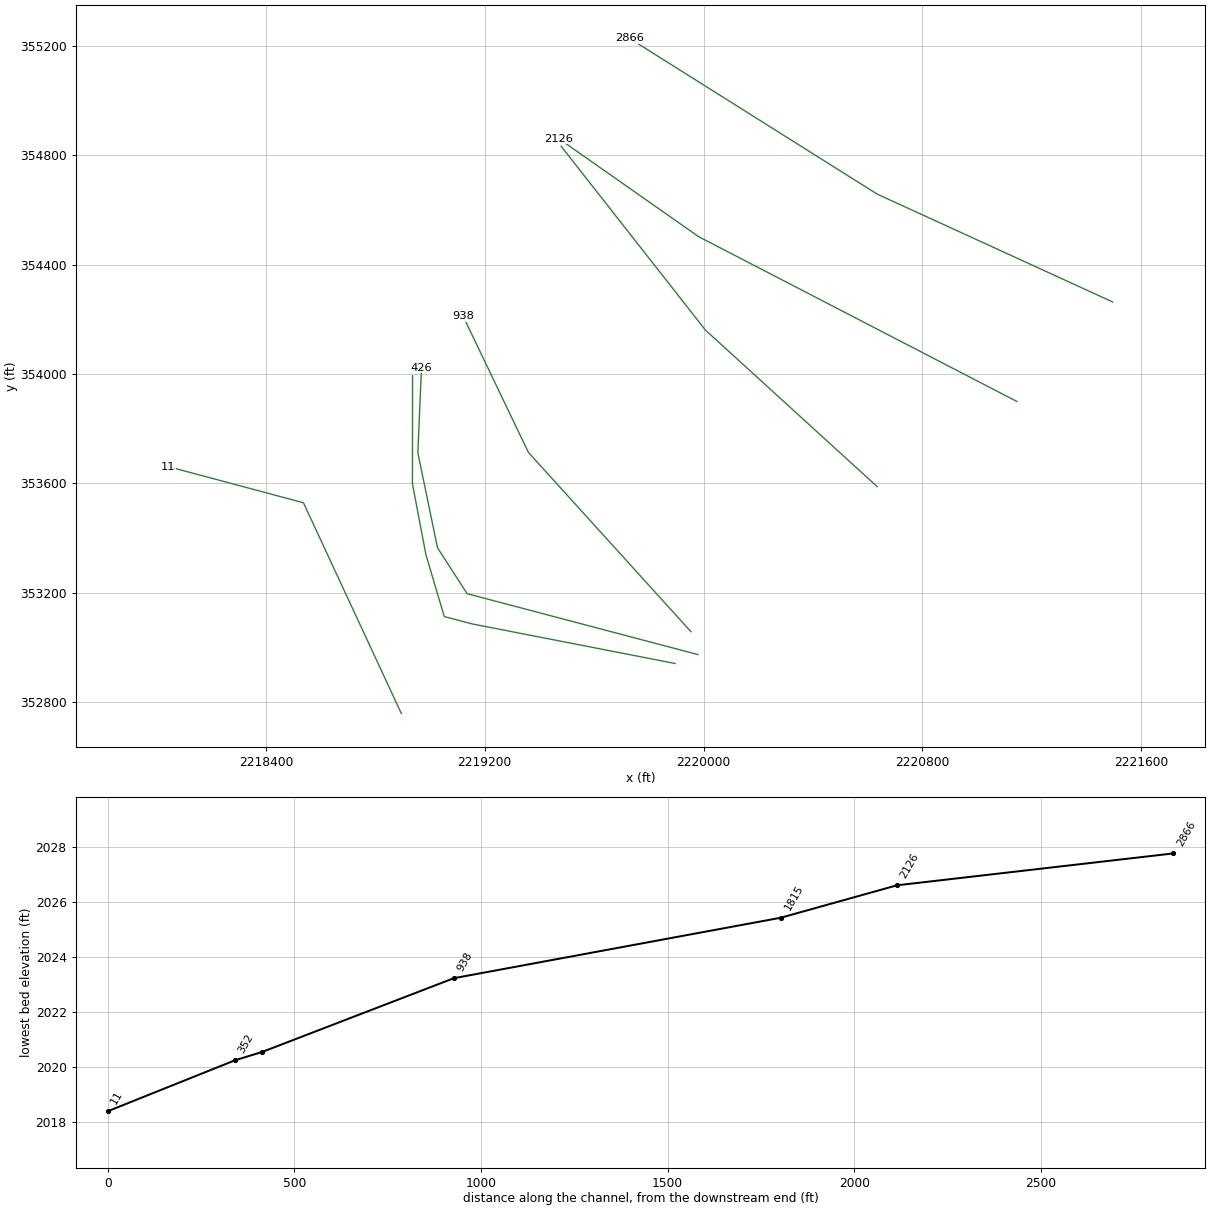
HEC-RAS study MFANTNYCK.prj: MFANTNYCK

--- MFANTNYCK.g01 (geometry) --- (continued)

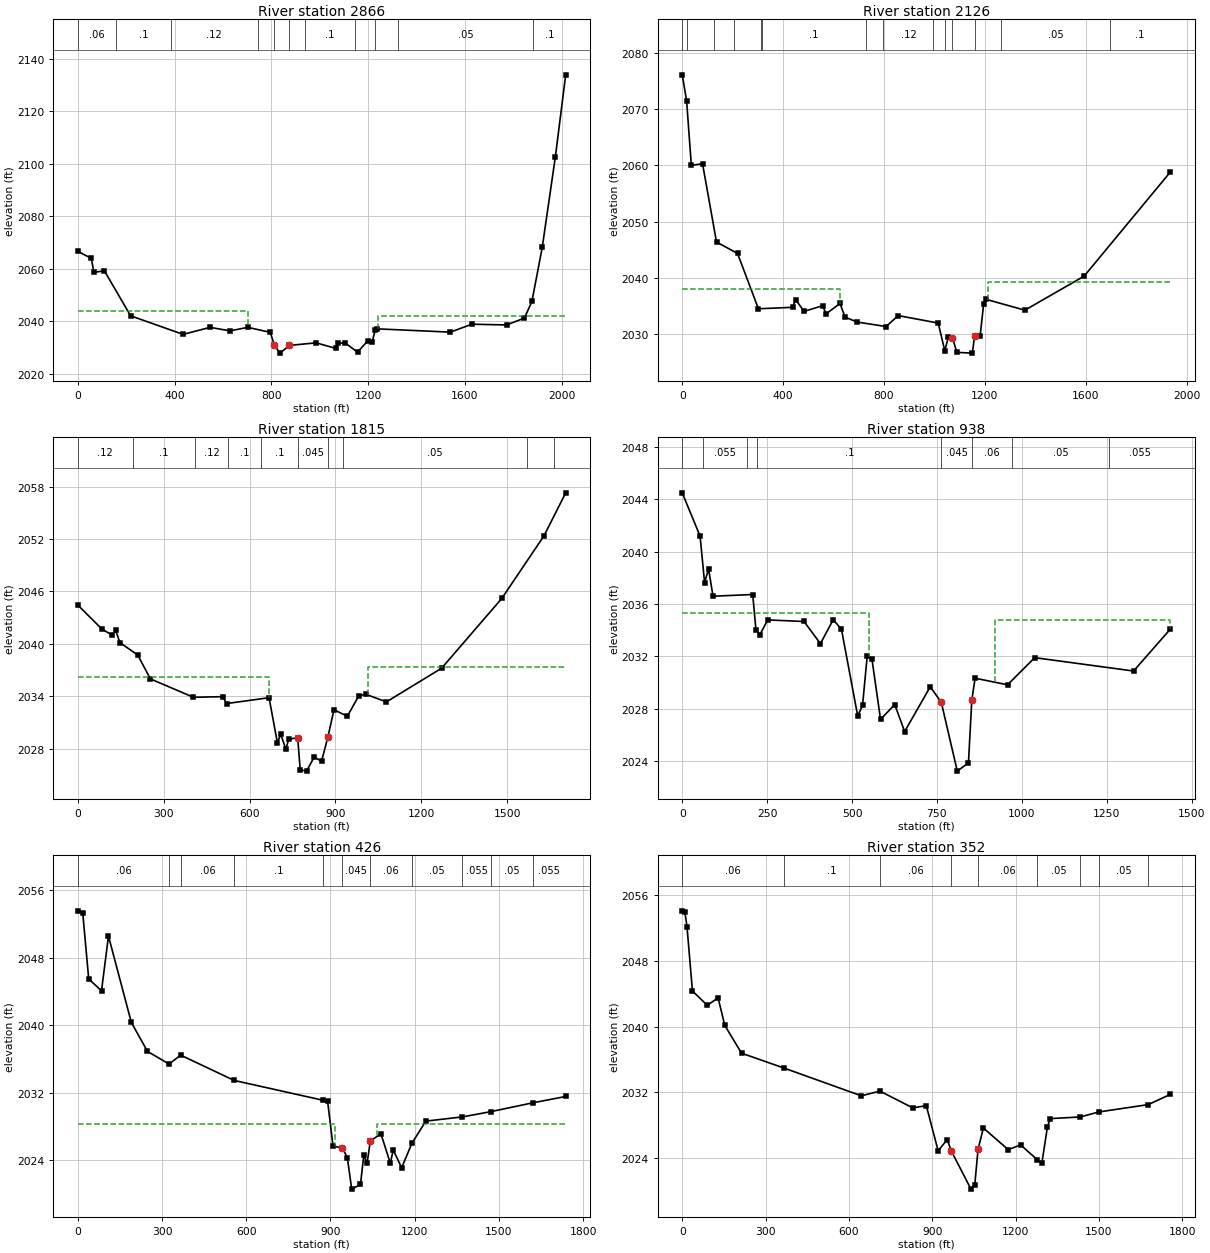
Type RM Length L Ch R = 1 ,2866    ,717,740.6,738.5
XS GIS Cut Line= 3
2221496.00573756354263.0786099732220634.89459889354657.523031056
2219729.33899531355226.967430234
#Sta/Elev= 30
       0 2066.61    55.8 2063.86    66.6 2058.55   109.9 2059.15   218.2 2042.01
   435.3 2034.92   546.3 2037.59   629.6 2036.27   702.6  2037.6   795.6 2035.71
   812.7 2030.78   835.3 2027.78     875 2030.73   985.3  2031.7  1066.5 2029.59
  1076.1 2031.52  1104.6 2031.72  1156.4 2028.15    1199 2032.51  1216.6  2031.9
    1230 2036.76  1237.9 2037.03  1540.1 2035.78  1629.2  2038.8  1772.6 2038.52
  1846.3 2041.14  1877.3 2047.51  1919.9 2068.06  1974.2 2102.63  2016.9 2133.83
#Mann= 11 ,-1 , 0
       0     .06       0  158.66      .1       0  383.74     .12       0
  743.42      .1       0   812.7    .045       0     875      .1       0
  938.53      .1       0 1145.93     .06       0 1228.67    .055       0
 1322.72     .05       0 1882.87      .1       0
#XS Ineff= 2 , 0
          704.58 2043.82  1240.8         2041.86
Permanent Ineff=
       F       F
Bank Sta=812.7,875
XS Rating Curve= 0 ,0
Exp/Cntr=0.3,0.1

Type RM Length L Ch R = 1 ,2126    ,315.5,311.3,282.6
XS GIS Cut Line= 3
 2221146.0054533353899.1895739732219982.11670497354501.967239812
2219471.00552247354860.300840721
#Sta/Elev= 30
       0 2076.06    17.3 2071.49    36.1 2059.97    80.5 2060.27   135.9 2046.36
   219.3 2044.33   302.1  2034.5   437.5 2034.76   449.9 2036.13   483.2 2034.03
   557.7 2035.06   569.8 2033.57   625.8 2035.44   645.8    2033   694.3 2032.14
   808.5 2031.34   856.4 2033.29  1015.3 2031.96  1041.1 2027.05  1055.9 2029.53
  1071.3 2029.39  1089.1 2026.75  1150.9 2026.62  1159.3 2029.67  1181.5 2029.72
  1195.4 2035.36  1203.7 2036.19  1358.9 2034.25  1594.2 2040.31  1934.9 2058.75
#Mann= 14 ,-1 , 0
       0      .1       0    20.4     .06       0  125.99     .12       0
  206.66      .1       0   311.2     .12       0  315.72      .1       0
  729.35      .1       0   797.9     .12       0  996.18      .1       0
 1042.96     .06       0  1071.3    .045       0  1159.3    .055       0
 1264.76     .05       0 1697.12      .1       0
#XS Ineff= 2 , 0
          625.92 2037.94 1212.22          2039.3
Permanent Ineff=
       F       F
Bank Sta=1071.3,1159.3
XS Rating Curve= 0 ,0
Exp/Cntr=0.3,0.1

Type RM Length L Ch R = 1 ,1815    ,870.9,876.1,860.8
XS GIS Cut Line= 3
2220634.89459889353588.0786476432220007.11665498354160.300600305
2219479.33883914354832.523009136
#Sta/Elev= 30
       0 2044.44    84.3 2041.69   119.8 2041.01   132.2 2041.55   146.8 2040.15
   209.4 2038.72   253.5 2035.99   403.9 2033.89   506.6 2033.96   519.4 2033.17
     668 2033.84   697.1 2028.68   708.7 2029.66   726.4 2027.96   736.9  2029.1
     768 2029.26   776.8 2025.58   799.2 2025.44   825.7 2027.07   851.3 2026.55
   873.7 2029.38   894.7 2032.46   941.5 2031.72   981.8 2034.09  1006.9 2034.22
  1077.8 2033.36  1270.9 2037.22  1481.2 2045.21  1628.4 2052.37  1704.1 2057.28
#Mann= 10 ,-1 , 0
       0     .12       0  192.39      .1       0  409.67     .12       0
   526.3      .1       0  640.42      .1       0     768    .045       0
   873.7     .06       0  925.04     .05       0 1569.01      .1       0
 1662.72      .1       0
#XS Ineff= 2 , 0
          666.21 2036.17 1012.56         2037.31
Permanent Ineff=
       F       F
Bank Sta=768,873.7
XS Rating Curve= 0 ,0
Exp/Cntr=0.3,0.1

Type RM Length L Ch R = 1 ,938     ,517.4,512.8,500.2
XS GIS Cut Line= 3
2219954.33887339353057.5229502322219359.89452422353713.078397647
2219121.38688193 354210.50248843
#Sta/Elev= 30
       0 2044.48    52.6 2041.17    65.8 2037.63    77.6 2038.67    90.6 2036.59
   207.6 2036.72     217 2034.03   228.6 2033.65   251.8 2034.78   358.7 2034.66
   406.9 2032.97   444.6  2034.8   468.9 2034.06   516.6 2027.46   530.9 2028.25
   544.5 2031.99   558.4 2031.83   583.9 2027.19   625.8 2028.32   654.9 2026.26
   730.3 2029.68   762.8 2028.49   809.9 2023.24   842.8 2023.87   852.6 2028.64
   862.3 2030.33   957.9 2029.83  1037.9  2031.9    1329 2030.88  1436.6 2034.06
#Mann= 8 ,-1 , 0
       0      .1       0   62.43    .055       0   189.5     .06       0
  221.57      .1       0   762.8    .045       0   852.6     .06       0
  972.14     .05       0 1258.04    .055       0
#XS Ineff= 2 , 0
          549.07 2035.28  920.88         2034.77
Permanent Ineff=
       F       F
Bank Sta=762.8,852.6
XS Rating Curve= 0 ,0
Exp/Cntr=0.5,0.3

Type RM Length L Ch R = 1 ,426     ,85.9,74.1,58.4
XS GIS Cut Line= 5
2219979.33882339352974.1894554792219135.89169139353196.607973889
2219027.55824664  353364.31629992218955.64861356353711.781484231
2218969.07095764 354022.60083244
#Sta/Elev= 30
       0 2053.54    17.6 2053.29    38.8 2045.47    84.4 2044.06   109.2 2050.55
   190.6 2040.32   248.2 2036.88   325.1 2035.38   366.3 2036.44     557 2033.44
   873.6 2031.09   889.8 2030.97   909.1 2025.64   942.4 2025.46   960.1 2024.28
   975.6 2020.56  1006.9 2021.11  1018.6 2024.59  1030.4 2023.64  1042.1 2026.28
  1079.8 2027.11  1113.3 2023.61  1123.4 2025.21  1153.5 2023.09  1190.4 2026.02
  1239.7 2028.62  1370.1 2029.12  1470.9 2029.74    1621 2030.79  1737.9 2031.54
#Mann= 11 ,-1 , 0
       0     .06       0   325.1      .1       0   366.3     .06       0
     557      .1       0   873.6     .06       0   942.4    .045       0
  1042.1     .06       0  1190.4     .05       0  1370.1    .055       0
  1470.9     .05       0    1621    .055       0
#XS Ineff= 2 , 0
             917 2028.28    1067         2028.28
Permanent Ineff=
       F       F
Bank Sta=942.4,1042.1
XS Rating Curve= 0 ,0
Exp/Cntr=0.5,0.3

Type RM Length L Ch R = 1 ,352     ,322.6,340.2,345.9
XS GIS Cut Line= 6
2219896.30814956352941.3994948122219155.37065506353085.878536567
2219052.24586131353112.9621438092218984.84999873  353340.3576864
2218935.89143522353598.6911592332218936.37333719353993.178407184
#Sta/Elev= 30
       0 2054.07     9.6 2053.88    17.2 2052.14    36.7 2044.33    90.2 2042.59
     129 2043.49   153.3 2040.14   213.5 2036.77   367.3 2034.95   644.7 2031.59
   711.5 2032.16   829.6 2030.13   878.5 2030.39   921.1 2024.91   953.8 2026.27
   968.6 2024.88  1039.3 2020.25    1053  2020.8  1064.7 2025.07  1083.8 2027.68
  1173.7 2025.04  1217.8 2025.63  1277.6 2023.83  1294.6 2023.44  1314.6 2027.85
  1324.6 2028.82    1433 2029.02  1499.8 2029.63  1677.1 2030.52  1756.1 2031.75
#Mann= 9 ,-1 , 0
       0     .06       0   367.3      .1       0   711.5     .06       0
   968.6    .045       0  1064.7     .06       0  1277.6     .05       0
    1433    .055       0  1499.8     .05       0  1677.1    .055       0
Bank Sta=968.6,1064.7
XS Rating Curve= 0 ,0
Exp/Cntr=0.5,0.3

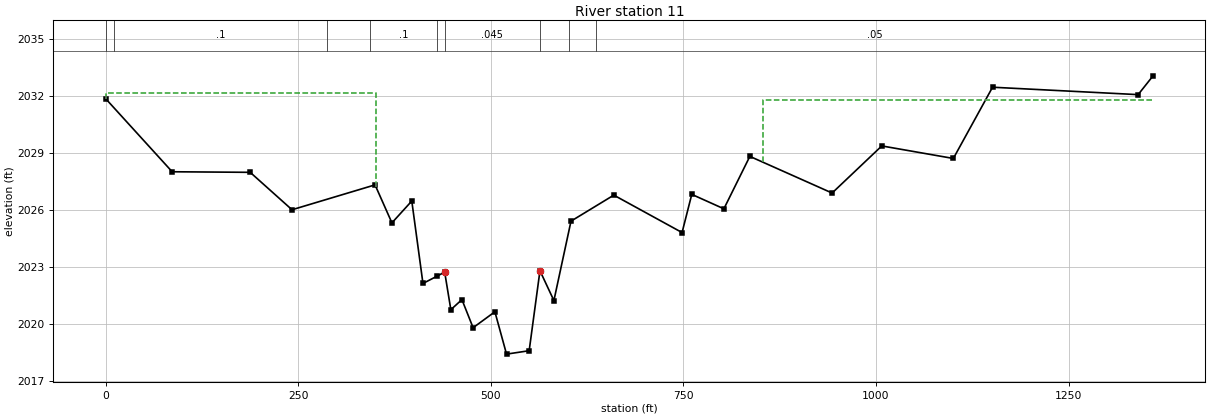
Type RM Length L Ch R = 1 ,11      ,,,
XS GIS Cut Line= 3
 2218895.1216972 352759.082086592218537.40304251353529.028905253
2218044.05738145353660.998194072
#Sta/Elev= 30
       0 2031.84    86.2    2028   187.5 2027.97   241.8    2026   349.6 2027.31
   371.5 2025.31   397.3 2026.46   411.8 2022.12   429.9  2022.5     440 2022.72
     448 2020.74   462.4 2021.27   476.9 2019.79   505.2 2020.63   520.3  2018.4
   549.7 2018.58   563.7 2022.79   581.8 2021.22     604  2025.4   659.6 2026.77
   748.2  2024.8   760.8 2026.81   802.5 2026.05   836.2 2028.81     943 2026.88
  1007.5 2029.36  1100.4  2028.7  1151.3 2032.45  1340.3 2032.06  1359.7 2033.05
#Mann= 9 ,-1 , 0
       0    .055       0    11.1      .1       0  286.88      .1       0
  343.14      .1       0   429.9      .1       0     440    .045       0
   563.7      .1       0     601      .1       0  637.04     .05       0
#XS Ineff= 2 , 0
          350.62 2032.12  852.93          2031.8
Permanent Ineff=
       F       F
Bank Sta=440,563.7
XS Rating Curve= 0 ,0
Exp/Cntr=0.3,0.1
LCMann Table=0

Chan Stop Cuts=-1
Use User Specified Reach Order=0
Composite Channel Slope=5